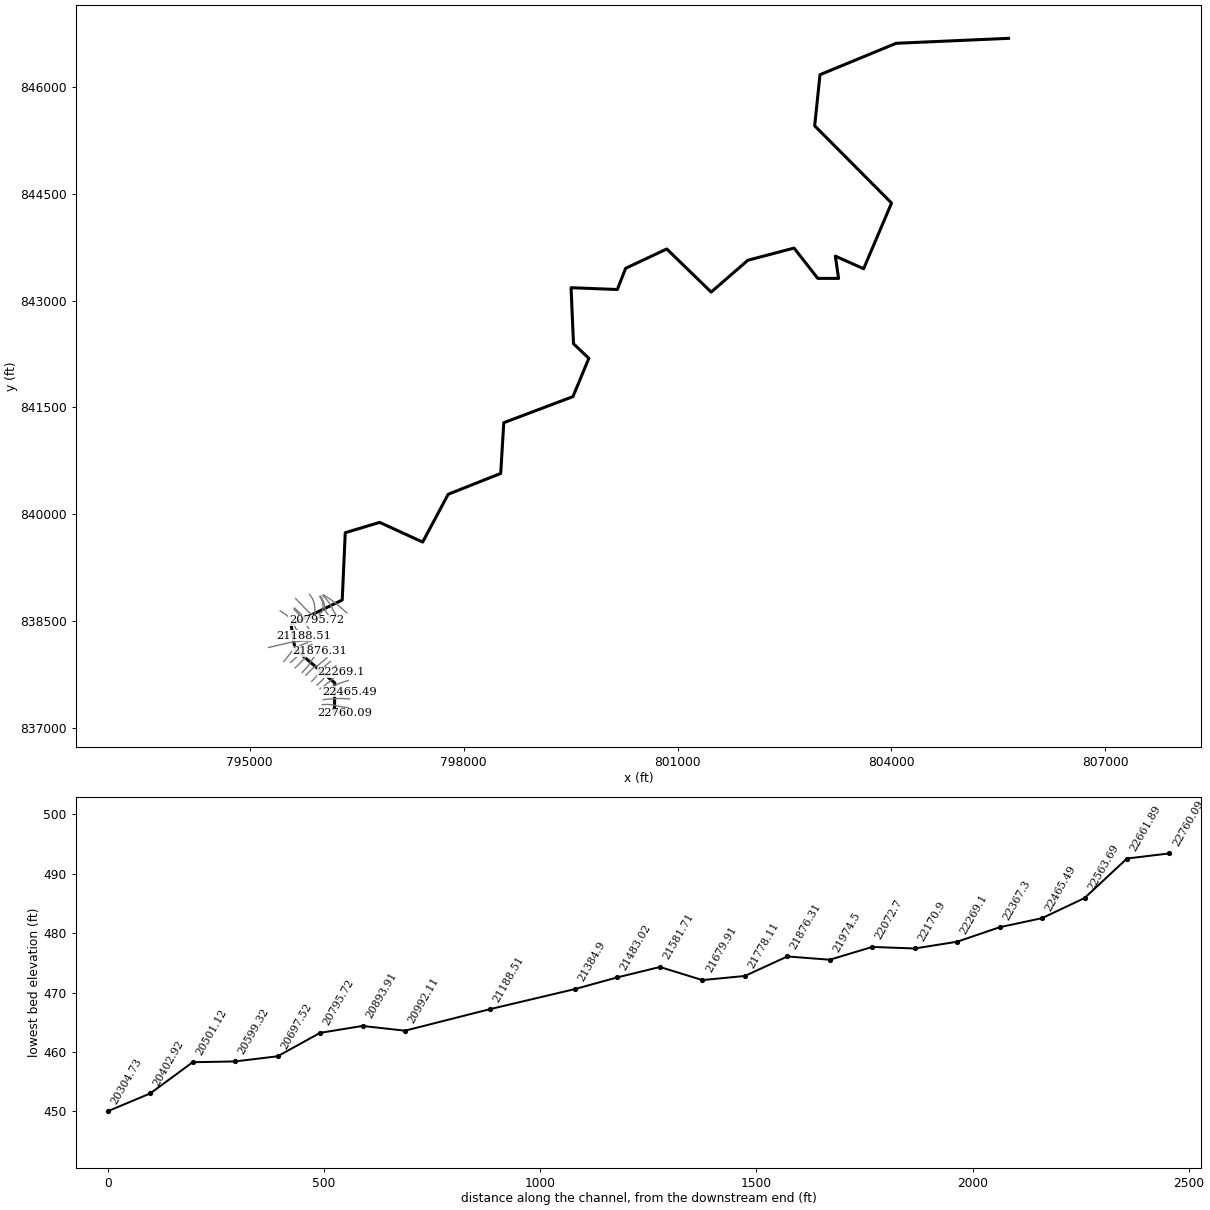
--- 18254_ras.prj (project) ---

Proj Title=18254
Current Plan=p01
Default Exp/Contr=0.3,0.1
English Units
Geom File=g01
Flow File=f01
Plan File=p01
Y Axis Title=Elevation
X Axis Title(PF)=Main Channel Distance
X Axis Title(XS)=Station
BEGIN DESCRIPTION:
RFD model 18254 exported to HEC-RAS
END DESCRIPTION:

--- 18254_ras.p01 (plan) ---

Plan Title=Plan 01
Program Version=4.10
Short Identifier=Plan 01
Geom File=g01
Flow File=f01
Subcritical Flow
Calc Critical at every XS
Secant Critical Depth

--- 18254_ras.f01 (steady flow) ---

Flow Title=Flow 01
Program Version=5.01
Number of Profiles= 6
Profile Names=10yr,25yr,50yr,100yr,100plus,500yr
River Rch & RM=18254,137,22760.09
  200.28  322.99  438.34  544.66   795.2 1359.95
River Rch & RM=18254,137,22661.89
  257.15  414.96  563.51  700.31 1022.45 1687.78
River Rch & RM=18254,137,22563.69
  258.24  416.73  565.91  703.29 1026.81 1693.95
River Rch & RM=18254,137, 22367.3
  263.32  424.95  577.09  717.19  1047.1 1722.61
River Rch & RM=18254,137, 22170.9
  265.51  428.48  581.89  723.15 1055.79 1734.84
River Rch & RM=18254,137, 22072.7
  268.77  433.74  589.05  732.04 1068.78 1753.12
River Rch & RM=18254,137, 21974.5
  272.04  439.01  596.22  740.94 1081.77 1771.33
River Rch & RM=18254,137,21876.31
  275.29  444.26  603.36   749.8 1094.71 1789.46
River Rch & RM=18254,137,21778.11
  277.46  447.76  608.11   755.7 1103.33 1801.51
River Rch & RM=18254,137,21679.91
  279.62  451.25  612.86   761.6 1111.94 1813.53
River Rch & RM=18254,137,21581.71
  282.15  455.33  618.39  768.47 1121.97 1827.51
River Rch & RM=18254,137,21483.02
  355.28  573.48  779.14  968.19 1413.56 2227.77
River Rch & RM=18254,137, 21384.9
  355.96  574.59  780.64  970.07  1416.3 2231.46
River Rch & RM=18254,137,21188.51
  360.75  582.32  791.17  983.14 1435.39 2257.21
River Rch & RM=18254,137,20992.11
  363.83  587.29  797.92  991.53 1447.64 2273.71
River Rch & RM=18254,137,20795.72
  366.55  591.69  803.91  998.98 1458.51 2288.33
River Rch & RM=18254,137,20697.52
  369.27  596.09   809.9 1006.41 1469.36 2302.92
River Rch & RM=18254,137,20501.12
  372.67  601.57  817.36 1015.69  1482.9  2321.1
River Rch & RM=18254,137,20402.92
  375.04  605.41  822.58 1022.17 1492.37 2333.79
River Rch & RM=18254,137,20304.73
  376.06  607.05  824.82 1024.94 1496.42 2339.22
River Rch & RM=18254,137,20206.53
   376.4   607.6  825.56 1025.87 1497.77 2341.03
River Rch & RM=18254,137,20108.33
  401.44  648.14  880.81 1094.59 1598.11 2475.24
River Rch & RM=18254,137,19715.54
   406.1  655.69  891.08 1107.35 1616.74 2499.97
River Rch & RM=18254,137,19420.94
     461  744.44 1011.92 1257.53 1835.99 2788.06
River Rch & RM=18254,137,19295.31
  462.29  746.53 1014.77 1261.07 1841.17 2794.81
River Rch & RM=18254,137,19126.35
  467.13  754.37 1025.45 1274.35 1860.55 2820.09
River Rch & RM=18254,137,18831.76
  579.61  936.66 1274.05 1583.68 2312.17 3399.66
River Rch & RM=18254,137,18727.76
  582.64  941.59  1280.8 1592.09 2324.45 3415.27
River Rch & RM=18254,137,18579.23
  585.05  945.51 1286.17  1598.8 2334.24 3427.74
River Rch & RM=18254,137,18456.25
  588.06  950.41 1292.87 1607.17 2346.47 3443.31
River Rch & RM=18254,137,18356.74
  588.96  951.88 1294.88 1609.68 2350.13 3447.97
River Rch & RM=18254,137,18207.47
  612.11  989.56 1346.43 1673.98 2444.02 3566.83
River Rch & RM=18254,137,18107.96
   612.7  990.53 1347.76 1675.64 2446.44  3569.9
River Rch & RM=18254,137,18008.45
  614.49  993.44 1351.75 1680.62 2453.71 3579.09
River Rch & RM=18254,137,17908.94
  617.46  998.29 1358.39 1688.91 2465.81  3594.4
River Rch & RM=18254,137, 17623.1
  628.75  1016.7 1383.58 1720.36 2511.73 3652.31
River Rch & RM=18254,137,17529.93
  632.01    1022 1390.85 1729.44 2524.98 3669.01
River Rch & RM=18254,137,17436.76
  637.92 1031.64 1404.05 1745.91 2549.03 3699.29
River Rch & RM=18254,137,17250.42
  639.98 1035.01 1408.66 1751.67 2557.44 3709.87
River Rch & RM=18254,137,17157.25
  642.05 1038.37 1413.27 1757.43 2565.84 3720.43
River Rch & RM=18254,137,16970.92
  666.94    1079 1468.93 1826.96 2667.36 3847.79
River Rch & RM=18254,137,16877.75
  669.85 1083.75 1475.44  1835.1 2679.24 3862.66
River Rch & RM=18254,137,16784.58
   671.9 1087.08 1480.01  1840.8 2687.56 3873.06
River Rch & RM=18254,137,16691.41
  674.51 1091.35 1485.87 1848.11 2698.25 3886.42
River Rch & RM=18254,137,16481.74
  679.11 1098.88  1496.2 1861.05 2717.13 3910.11
River Rch & RM=18254,137,16388.43
  682.55 1104.51 1503.94 1870.73 2731.27 3927.85
River Rch & RM=18254,137,16150.91
  693.58 1122.63 1528.87    1902 2776.92 3985.27
River Rch & RM=18254,137, 16006.7
  696.68 1127.73 1535.89 1910.81 2789.78  4001.4
River Rch & RM=18254,137,15862.48
  701.19 1135.14 1546.08 1923.58 2808.43 4024.83
River Rch & RM=18254,137,15718.27
  706.21 1143.41 1557.48  1937.9 2829.34 4051.12
River Rch & RM=18254,137,15574.05
  707.88 1146.16 1561.28 1942.67 2836.29 4059.87
River Rch & RM=18254,137,15429.84
  709.55 1148.91 1565.07 1947.43 2843.25 4068.61
River Rch & RM=18254,137,15285.62
  831.34 1347.94 1838.08 2288.72 3341.53 4680.18
River Rch & RM=18254,137,15141.41
  837.52 1358.13 1852.13 2306.37 3367.31 4711.84
River Rch & RM=18254,137,14997.19
  839.13 1360.79 1855.79 2310.98 3374.02 4720.09
River Rch & RM=18254,137,14852.98
  842.62 1366.54 1863.73 2320.94 3388.57 4737.93
River Rch & RM=18254,137,14708.76
   844.5 1369.63 1867.99  2326.3  3396.4 4747.53
River Rch & RM=18254,137,14564.55
  930.27 1510.98 2062.96  2571.2 3753.96 5182.55
River Rch & RM=18254,137,14420.33
  934.44 1517.87 2072.48 2583.17 3771.43 5203.72
River Rch & RM=18254,137, 14131.9
  937.31 1522.61 2079.02  2591.4 3783.44 5218.26
River Rch & RM=18254,137,13987.69
  953.87 1550.12 2117.15  2639.5 3853.68 5303.83
River Rch & RM=18254,137,13843.47
  955.67 1553.09 2121.26 2644.69 3861.24 5313.01
River Rch & RM=18254,137,13699.25
  961.82 1563.28 2135.36 2662.46 3887.18 5344.44
River Rch & RM=18254,137,13555.04
  963.32 1565.79 2138.85 2666.86 3893.62 5352.29
River Rch & RM=18254,137,13266.61
  964.86 1568.33 2142.37  2671.3 3900.09 5360.13
River Rch & RM=18254,137,13122.39
  974.53 1584.38  2164.6 2699.32 3941.01  5409.7
River Rch & RM=18254,137,12978.18
  980.66 1594.53 2178.65 2717.02 3966.85 5440.92
River Rch & RM=18254,137,12833.96
  982.19 1597.07 2182.16 2721.44 3973.31 5448.71
River Rch & RM=18254,137, 12592.1
  984.21 1600.42  2186.8 2727.31 3981.87  5459.1
River Rch & RM=18254,137,12350.23
  984.97 1601.68 2188.56 2729.52  3985.1 5462.99
River Rch & RM=18254,137,12108.36
 1048.63 1706.76 2333.66 2911.93 4251.41 5781.07
River Rch & RM=18254,137,11866.49
 1052.32 1712.91  2342.2 2922.72 4267.18 5800.09
River Rch & RM=18254,137,11624.62
 1070.24 1742.77  2383.7 2975.19 4343.78 5892.29
River Rch & RM=18254,137,11382.75
 1071.95 1745.63 2387.67 2980.21 4351.11  5901.1
River Rch & RM=18254,137,11140.88
  1077.8 1755.39 2401.24 2997.39 4376.18 5931.27
River Rch & RM=18254,137,10833.22
 1079.98 1759.04 2406.32 3003.81 4385.57 5942.57
River Rch & RM=18254,137,10777.11
 1081.92 1762.28 2410.83 3009.52  4393.9 5952.61
River Rch & RM=18254,137,10634.62
 1082.88 1763.89 2413.07 3012.37 4398.06 5957.62
River Rch & RM=18254,137,10587.12
 1084.09  1765.9 2415.88 3015.92 4403.25 5963.89
River Rch & RM=18254,137,10444.63
 1086.51 1769.95 2421.51 3023.05 4413.65 5976.42
River Rch & RM=18254,137,10320.75
 1087.92 1772.33 2424.84 3027.28 4419.84 5983.93
River Rch & RM=18254,137,10196.88
 1089.12 1774.34 2427.64 3030.83 4425.02 5990.18
River Rch & RM=18254,137,10073.01
 1090.78 1777.13 2431.54 3035.78 4432.24 5998.94
River Rch & RM=18254,137,9949.132
 1123.94 1832.48 2508.52 3133.17 4574.43 6169.28
River Rch & RM=18254,137,9853.603
 1125.37 1834.87 2511.85  3137.4  4580.6  6176.7
River Rch & RM=18254,137,9419.391
  1140.3  1859.9 2546.77 3181.69 4645.27 6254.38
River Rch & RM=18254,137,9197.952
 1144.32 1866.64 2556.17 3193.62 4662.68 6275.27
River Rch & RM=18254,137,8976.513
 1148.55 1873.75 2566.09 3206.21 4681.07 6297.37
River Rch & RM=18254,137,8528.855
 1171.12 1911.62 2618.94 3273.28 4778.98  6414.7
River Rch & RM=18254,137,8200.408
 1179.22 1925.27 2638.03 3297.55 4814.42 6457.27
River Rch & RM=18254,137, 7735.99
 1187.54 1939.28 2657.63 3322.46  4850.8 6500.94
River Rch & RM=18254,137,7585.554
  1197.3 1955.68 2680.53 3351.56 4893.28 6551.74
River Rch & RM=18254,137,7282.891
 1204.25 1967.36 2696.86  3372.3 4923.56 6587.94
River Rch & RM=18254,137,6733.961
 1208.61 1974.71 2707.14 3385.38 4942.66 6610.82
River Rch & RM=18254,137, 6324.82
 1213.92 1983.64 2719.63 3401.25 4965.82 6638.48
River Rch & RM=18254,137, 6185.03
 1214.84 1985.19  2721.8    3404 4969.84 6643.28
River Rch & RM=18254,137,6003.202
 1232.81 2015.41 2764.04 3457.68 5048.21 6736.71
River Rch & RM=18254,137,5821.373
 1234.17 2017.72 2767.27 3461.79 5054.21 6743.88
River Rch & RM=18254,137,5730.459
 1235.31 2019.64 2769.96 3465.21  5059.2 6749.85
River Rch & RM=18254,137,5639.545
 1236.22 2021.17 2772.11 3467.94  5063.2 6754.63
River Rch & RM=18254,137, 5548.63
 1237.13 2022.71 2774.26 3470.68 5067.19  6759.4
River Rch & RM=18254,137,5366.802
 1239.41 2026.55 2779.63 3477.52 5077.17 6771.32
River Rch & RM=18254,137,5184.973
 1241.23 2029.61 2783.93 3482.98 5085.16 6780.86
River Rch & RM=18254,137,4942.956
 1241.68 2030.38    2785 3484.35 5087.15 6783.24
Boundary for River Rch & Prof#=18254,137,1
Up Type= 0
Dn Type= 2
Boundary for River Rch & Prof#=18254,137,2
Up Type= 0
Dn Type= 2
Boundary for River Rch & Prof#=18254,137,2
Up Type= 0
Dn Type= 2
Boundary for River Rch & Prof#=18254,137,2
Up Type= 0
Dn Type= 2
Boundary for River Rch & Prof#=18254,137,2
Up Type= 0
Dn Type= 2
Boundary for River Rch & Prof#=18254,137,2
Up Type= 0
Dn Type= 2

--- 18254_ras.g01 (geometry) ---

Geom Title=18254
Program Version=4.10

River Reach=18254,137
Reach XY= 30
796188.954284848837221.985587368796192.796837898837636.981319253
795635.336583049838110.319044754795580.870261015 838451.60257078
796297.544373067838799.642837386796340.243090304839743.667653253
796822.684424819839888.294707083797425.817813308839612.181561451
 797783.40404275840282.498062244798520.316065225840574.711918302
 798563.26254046841286.295411385799533.564333619841652.297637239
799756.178331792842188.877800527799541.121677339842394.099698848
799506.852392885843179.510000695800155.984475883843154.399550761
800272.422839074843451.863993549800849.322479191843722.667416416
801471.919081959 843118.44542515801986.680724266843564.614045953
 802634.38068059843735.466197286802967.085600378843310.396161789
803258.838403196843310.279395773803213.250873894843622.746307835
803610.078196913843445.849709814804001.747254997844367.234602467
802923.630475342845450.240024084802998.273107648846166.809293947
804065.662749233846607.200824425805643.110378088846676.867281219

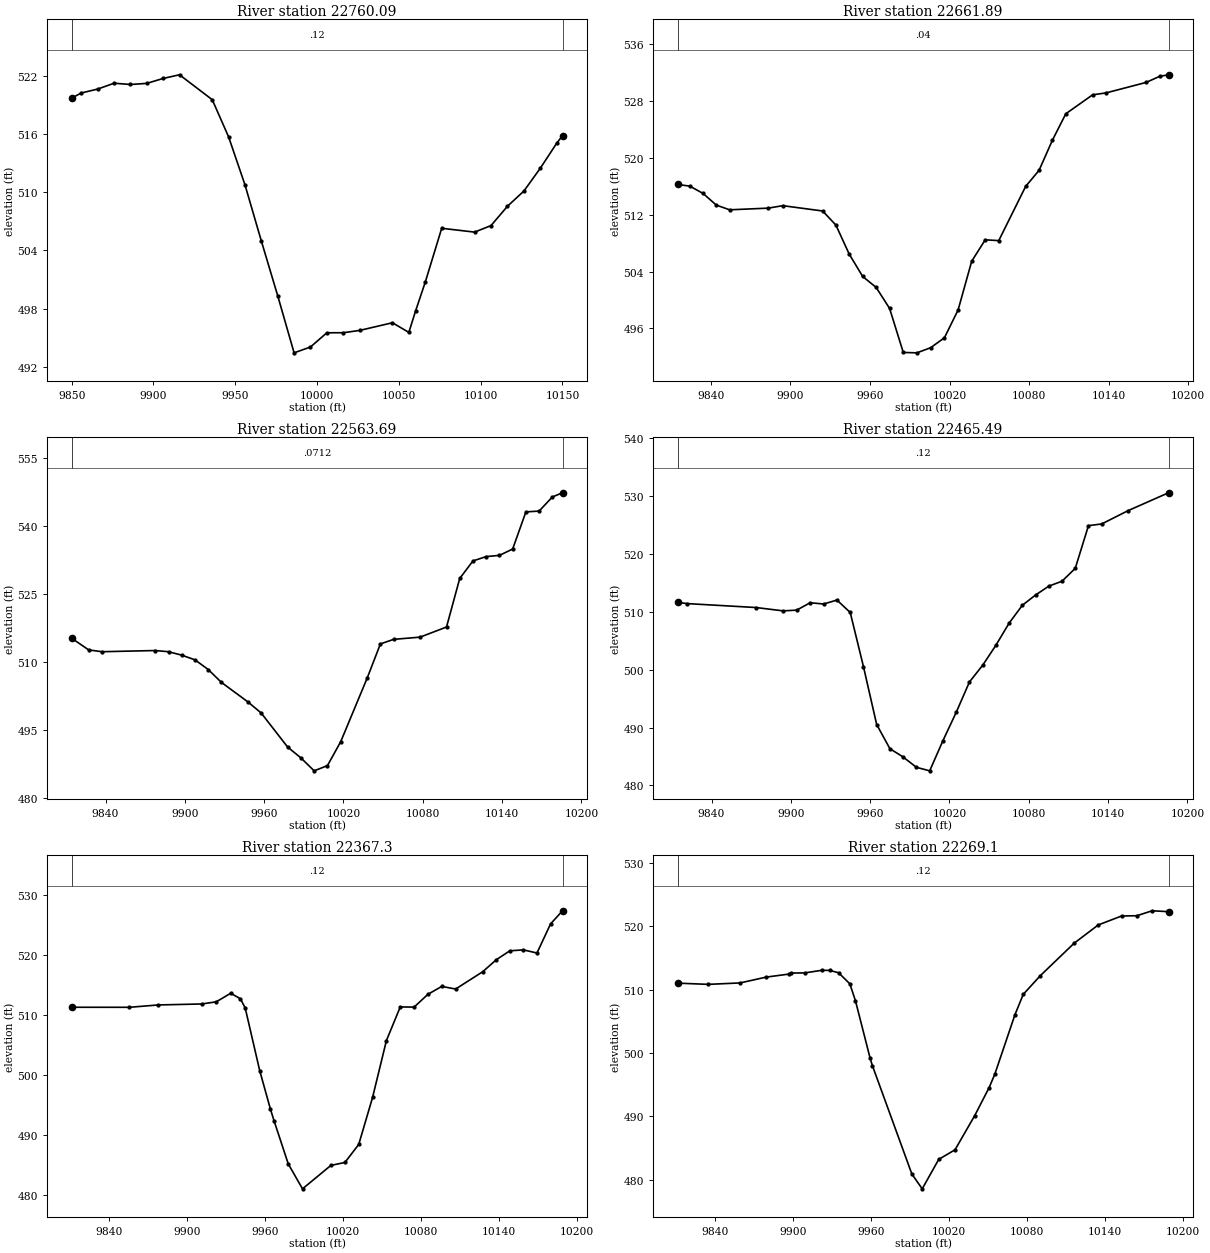
Type RM Length L Ch R = 1 ,22760.09,98.198000,98.198000,98.198000
XS GIS Cut Line= 6
796038.991088864837224.813997634796109.078558423837225.623813029
796187.193821564837223.076567815796190.004187263 837222.93306028
796249.194156618837218.835221636796338.471344441837209.742591457
#Sta/Elev= 30
9849.937519.72419855.946 520.2579865.947  520.669875.948521.26329885.948521.1324
9895.949521.2454 9905.95521.7573 9915.95522.13459935.959519.56079945.964515.7196
 9955.97510.76849965.975504.9714 9975.98499.32049985.986493.43139995.991494.0337
10006.01495.501410016.03 495.50710026.06495.7448 10046.1496.537910056.13495.5406
10060.33497.792210066.17 500.72910076.22506.289910096.32505.892610106.37 506.569
10116.43508.564810126.48510.136610136.53512.497710146.58515.084310150.07515.8452
#Mann= 3 , 0 , 0
9849.937    0.12       09849.937    0.12       010150.07    0.12       0
#XS Ineff= 2 , 0
       0                               0
Bank Sta=9849.937,10150.07
Exp/Cntr=0.3,0.1

Type RM Length L Ch R = 1 ,22661.89,98.198100,98.198100,98.198100
XS GIS Cut Line= 6
 796015.79579246837331.465229955796084.154884606837335.249723664
796140.331593177837332.162511845796174.041159067837326.646250411
796263.782619639837305.496694145796381.710109215837289.407513035
#Sta/Elev= 30
9814.958516.24849824.176516.02219834.191514.99099844.207513.34829854.222512.6868
9883.421512.92319894.283513.26919924.328512.52189934.343510.54019944.413506.4438
9954.546503.30969964.679501.7748 9974.83 498.8189985.149492.62249995.467492.5704
10005.81493.296210016.15 494.68810026.49498.606710036.72505.453810046.92508.4664
10057.12508.3536 10077.4515.977910087.49518.234310097.58522.479310107.68526.1957
10127.86528.858510137.95529.127410168.23530.603810178.33531.4521 10185.1531.6786
#Mann= 3 , 0 , 0
9814.958    0.04       09814.958    0.04       0 10185.1    0.04       0
#XS Ineff= 2 , 0
       0                               0
Bank Sta=9814.958,10185.1
Exp/Cntr=0.3,0.1

Type RM Length L Ch R = 1 ,22563.69,98.198000,98.198000,98.198000
XS GIS Cut Line= 6
796032.105981307837401.592328211796100.731140419837409.928087427
796202.035178039837414.715088109796240.580887242837418.334286513
796288.800853413837418.040787627796402.682850832837412.908424772
#Sta/Elev= 30
9814.259515.21599827.248512.62089837.321512.22379877.615512.48499887.662512.2217
9897.673511.46269907.684510.42269917.695508.29089927.707505.43949947.729501.1389
 9957.74 498.6939977.762491.16899987.785488.78039997.834485.9129 10007.9487.0678
10017.93492.352610037.95506.397210047.95513.941610057.95514.952810077.96515.4416
10097.98517.675110107.99528.4125   10118532.275710128.01533.236210138.02533.5015
10148.03534.904610158.04543.108610168.05543.286510178.06546.403810185.75547.3276
#Mann= 3 , 0 , 0
9814.259  0.0712       09814.259  0.0712       010185.75  0.0712       0
#XS Ineff= 2 , 0
       0                               0
Bank Sta=9814.259,10185.75
Exp/Cntr=0.3,0.1

Type RM Length L Ch R = 1 ,22465.49,98.198000,98.198000,98.198000
XS GIS Cut Line= 6
796028.445681962837483.689361354796104.655179295837506.769551892
796155.146364023837514.772151042 796186.19097472837515.155337523
796269.230430735837509.556570992796395.541664448837513.220283441
#Sta/Elev= 30
9814.264511.65619821.164511.43049873.563 510.7489894.273510.16799904.468510.3002
9914.664511.5776  9924.8511.35149934.868512.03769944.936509.88849954.938500.5447
9964.938490.53649974.939486.35999984.972484.9205 9995.01483.139210005.06482.5304
10015.11487.758710025.15492.648410035.15497.894210045.16500.775610055.16504.2295
10065.17508.057210075.17 511.13910085.18512.911910095.18514.442910105.19515.2939
10115.19 517.51310125.19524.8935 10135.2525.184410155.21527.490410185.76530.5726
#Mann= 3 , 0 , 0
9814.264    0.12       09814.264    0.12       010185.76    0.12       0
#XS Ineff= 2 , 0
       0                               0
Bank Sta=9814.264,10185.76
Exp/Cntr=0.3,0.1

Type RM Length L Ch R = 1 , 22367.3,98.198100,98.198100,98.198100
XS GIS Cut Line= 6
796035.093368299837527.742233708796167.318075439837592.687313309
 796206.10832186837610.112663763796219.102688097837615.719673898
 796304.71320635837646.988480055 796383.83420094837670.423840534
#Sta/Elev= 30
9811.162511.32639855.623511.31959877.905511.71279911.328511.8762 9922.47512.2347
9933.611513.66329941.039512.74939944.752511.20169955.893500.75169964.122 494.336
9966.896492.39599977.858485.16759988.819 481.00110010.68484.919610021.43485.4017
10032.08488.423310042.72496.271410053.37505.771310064.02511.381310074.66511.3537
10085.31513.492710095.95514.810110106.59514.369110127.45517.262510137.88519.2658
10148.31520.753510158.74520.907710169.17520.3848 10179.6525.240210188.81527.4393
#Mann= 3 , 0 , 0
9811.162    0.12       09811.162    0.12       010188.81    0.12       0
#XS Ineff= 2 , 0
       0                               0
Bank Sta=9811.162,10188.81
Exp/Cntr=0.3,0.1

Type RM Length L Ch R = 1 , 22269.1,98.198000,98.198000,98.198000
XS GIS Cut Line= 6
795985.798128175837555.430144169796056.909281274837606.069539922
796154.418167012837684.709729087796222.387819791837742.388626956
796248.777455645837761.171541791796285.740930613837783.977214899
#Sta/Elev= 30
9811.194511.00419834.767 510.8119859.319511.03829879.409511.95669896.649512.4249
9898.493512.59229909.018512.61899922.026513.02659928.091513.01669935.035512.6454
9943.726510.89199948.044508.21839959.361499.11969961.052498.00019991.406 480.901
9999.376478.5637 10012.1483.219910024.59484.718910039.73490.104710050.82494.5281
10055.18496.632710070.64505.999410077.05509.229110090.16512.174410116.17517.2937
10134.72520.178810152.67521.593610164.42521.634710176.17522.416210188.79522.2762
#Mann= 3 , 0 , 0
9811.194    0.12       09811.194    0.12       010188.79    0.12       0
#XS Ineff= 2 , 0
       0                               0
Bank Sta=9811.194,10188.79
Exp/Cntr=0.3,0.1

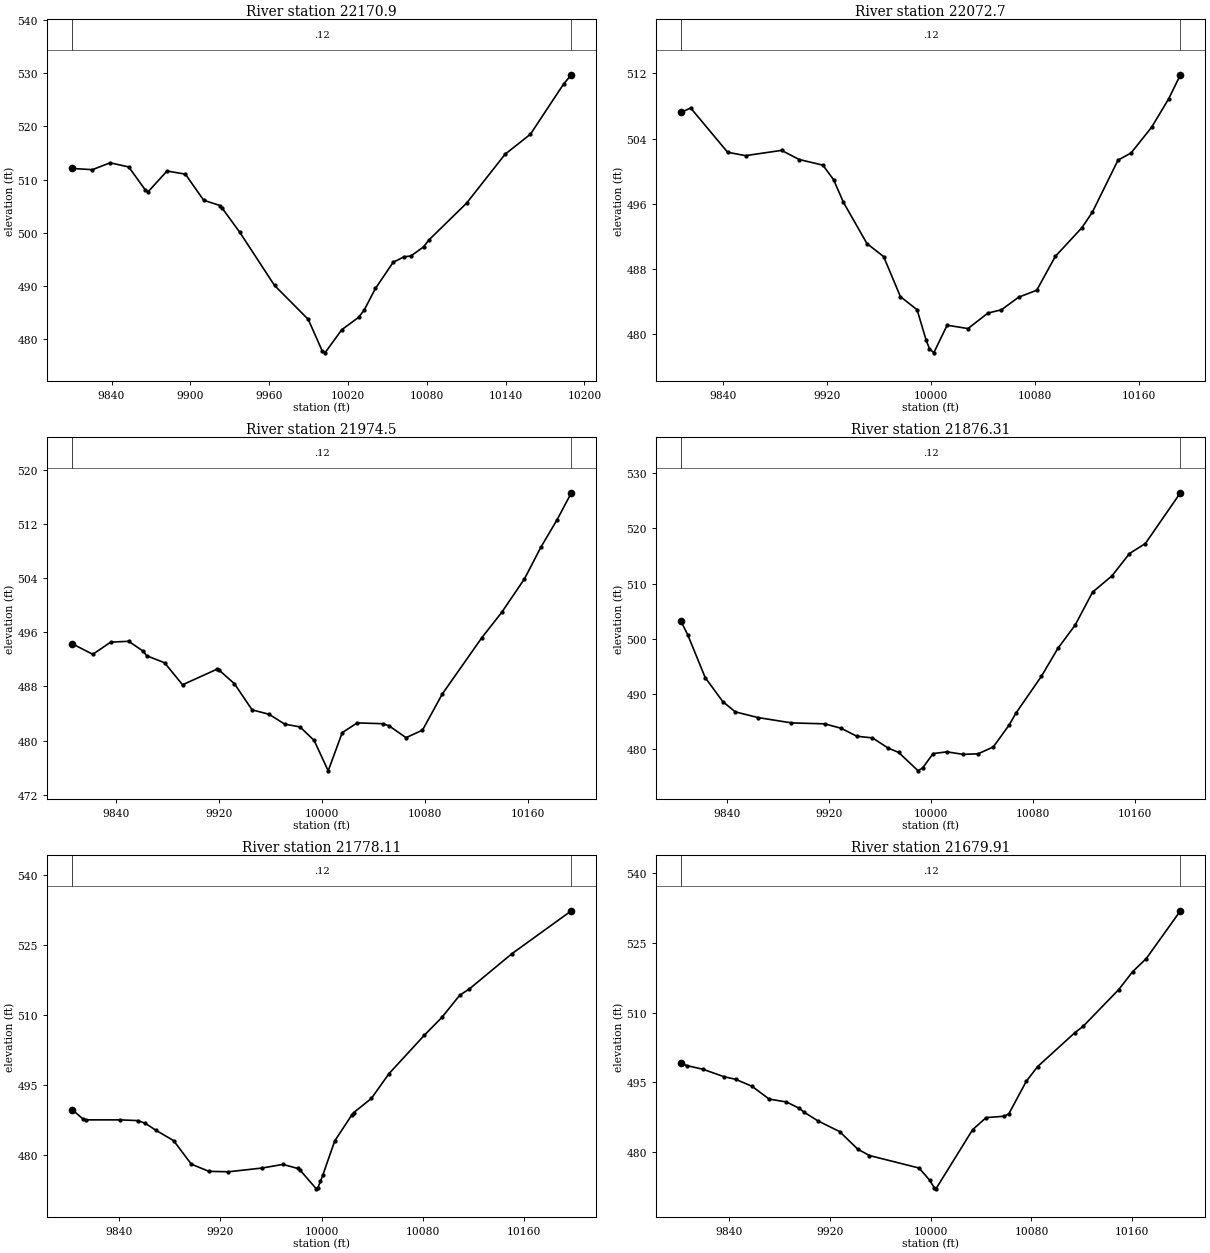
Type RM Length L Ch R = 1 , 22170.9,98.198100,98.198100,98.198100
XS GIS Cut Line= 6
795943.405274129837606.100862159795989.453362784837647.542225838
796028.142666874837687.175343673796131.886560332837809.742683089
796170.729306846837845.829219998796209.698563653837875.906248026
#Sta/Elev= 30
9809.875512.07879825.474511.85119838.927513.14339853.076512.36319865.834508.0061
9868.025507.73929882.247511.60539896.222511.00849910.197506.09869922.712505.1006
9924.171504.64769937.583500.09869964.091490.09289989.766483.713910000.35477.8095
10002.51477.422410015.31481.776210028.12484.095110032.39485.474310040.92489.5175
10054.41494.439710062.76495.477610067.93495.631510077.62497.349110081.45498.5949
10110.27505.547410139.66514.7626 10158.9518.511310184.17527.9506 10190.1529.6885
#Mann= 3 , 0 , 0
9809.875    0.12       09809.875    0.12       0 10190.1    0.12       0
#XS Ineff= 2 , 0
       0                               0
Bank Sta=9809.875,10190.1
Exp/Cntr=0.3,0.1

Type RM Length L Ch R = 1 , 22072.7,98.198000,98.198000,98.198000
XS GIS Cut Line= 6
795869.693625361 837659.77523451795907.229352024837696.904454372
  795942.1642214837735.086644605796043.977696855837858.885876581
796092.575028453837906.579329798796132.077664674837939.119679672
#Sta/Elev= 30
9807.922 507.2039815.351507.74719843.791502.30869857.583501.89689885.246 502.542
  9898.8501.42079916.983500.73389925.217498.96059932.893496.15269950.931491.1013
9963.788489.49829976.644484.59149989.501482.97449996.535479.2052    9999478.2131
10002.32477.684510012.61481.076210028.67480.6657   10044482.569110054.32482.9683
10067.62484.516910081.52485.369410095.79 489.51710116.25493.045710124.35494.9634
10144.02501.337910154.12502.228310169.85505.375110182.89 508.83910192.06511.8239
#Mann= 3 , 0 , 0
9807.922    0.12       09807.922    0.12       010192.06    0.12       0
#XS Ineff= 2 , 0
       0                               0
Bank Sta=9807.922,10192.06
Exp/Cntr=0.3,0.1

Type RM Length L Ch R = 1 , 21974.5,98.198100,98.198100,98.198100
XS GIS Cut Line= 6
795786.404326638837743.398971568795891.285100527837848.502971188
795912.214456795837863.209452685795947.016262918837878.617548983
 795966.73313174837891.063194508796083.777043363837988.756673197
#Sta/Elev= 30
9806.017494.30069822.198492.73039836.145494.52649850.093494.64949861.383493.1878
 9864.04 492.5219877.988491.47569891.935488.22899918.582490.52079920.084490.4365
 9932.26488.38239945.937484.53279959.074 483.8839971.296482.42449983.174482.0118
9994.165480.011110005.07475.530510015.98481.171510027.62482.607710047.55482.4833
10052.37482.171210065.53480.423810078.31 481.534 10093.7486.868210124.46495.1933
10139.84498.912210157.55503.870510170.21508.506610182.87512.589510193.98516.5666
#Mann= 3 , 0 , 0
9806.017    0.12       09806.017    0.12       010193.98    0.12       0
#XS Ineff= 2 , 0
       0                               0
Bank Sta=9806.017,10193.98
Exp/Cntr=0.3,0.1

Type RM Length L Ch R = 1 ,21876.31,98.198000,98.198000,98.198000
XS GIS Cut Line= 6
795735.659572598837781.231078023795818.299526327  837873.6433051
795884.825304741 837975.78963758795913.152226295838012.666164148
795954.209382714838054.041418623795986.915356234838078.870159943
#Sta/Elev= 30
9804.043 503.1639809.246500.7692 9823.05492.96279836.854488.62169846.604486.7639
9864.463485.73199890.717484.76719916.805484.59399929.742 483.7879942.005482.3449
9954.267 482.049 9966.53480.20979974.787479.41829990.119 476.0799993.822476.6624
10001.86479.209210012.76  479.5210025.48479.059810037.29479.174510049.09480.4156
10061.64484.424610066.73486.499110086.86493.220510099.71498.254810113.35502.5039
10126.98508.461110142.28511.423110155.85 515.433 10168.4517.269610195.92526.4605
#Mann= 3 , 0 , 0
9804.043    0.12       09804.043    0.12       010195.92    0.12       0
#XS Ineff= 2 , 0
       0                               0
Bank Sta=9804.043,10195.92
Exp/Cntr=0.3,0.1

Type RM Length L Ch R = 1 ,21778.11,98.198100,98.198100,98.198100
XS GIS Cut Line= 6
795637.145855973837849.227918244795679.309040207837888.873185201
  795754.5058151837966.607783788795859.635238499838070.483314364
795888.430748111838095.677623359795923.319366374838119.671579512
#Sta/Elev= 30
9802.739489.75349811.166487.8096 9813.52487.54259840.973487.53849854.699 487.386
9860.614486.81479869.138485.30459883.052483.10269896.965478.08219910.878476.5359
 9926.33476.44429952.618477.23179969.443478.02059981.077477.14989983.113 476.738
9995.744472.79479996.782472.8836    9999474.4059   10001475.827910010.31483.0436
10023.89  488.6310025.28489.095210039.23  492.1210053.18497.429510081.07505.6332
10095.02509.481910108.96514.178510116.61515.529810150.31523.083610197.22532.2474
#Mann= 3 , 0 , 0
9802.739    0.12       09802.739    0.12       010197.22    0.12       0
#XS Ineff= 2 , 0
       0                               0
Bank Sta=9802.739,10197.22
Exp/Cntr=0.3,0.1

Type RM Length L Ch R = 1 ,21679.91,98.198000,98.198000,98.198000
XS GIS Cut Line= 6
795571.593149868837923.221614591795653.226663967837995.092584901
795742.118205791838095.088890572795771.484354672838123.536717975
795813.313772987 838153.11107178795870.609158224838177.030048338
#Sta/Elev= 30
9801.461499.11199805.885 498.6319818.871497.82549835.599496.22899844.842495.6664
9857.836494.16969871.554491.40619885.273490.78599895.534489.42359898.991488.6572
9910.141486.73929927.477484.42819942.087480.6087  9951.3479.26389990.701476.5788
    9999474.003910002.95472.266710004.12472.102410033.31484.8378   10044487.4213
10058.36487.720510062.05488.235310075.97495.2482   10085498.411210114.61 505.703
10121.12 507.05810149.35514.943910160.52518.824410171.34521.638510198.49531.9128
#Mann= 3 , 0 , 0
9801.461    0.12       09801.461    0.12       010198.49    0.12       0
#XS Ineff= 2 , 0
       0                               0
Bank Sta=9801.461,10198.49
Exp/Cntr=0.3,0.1

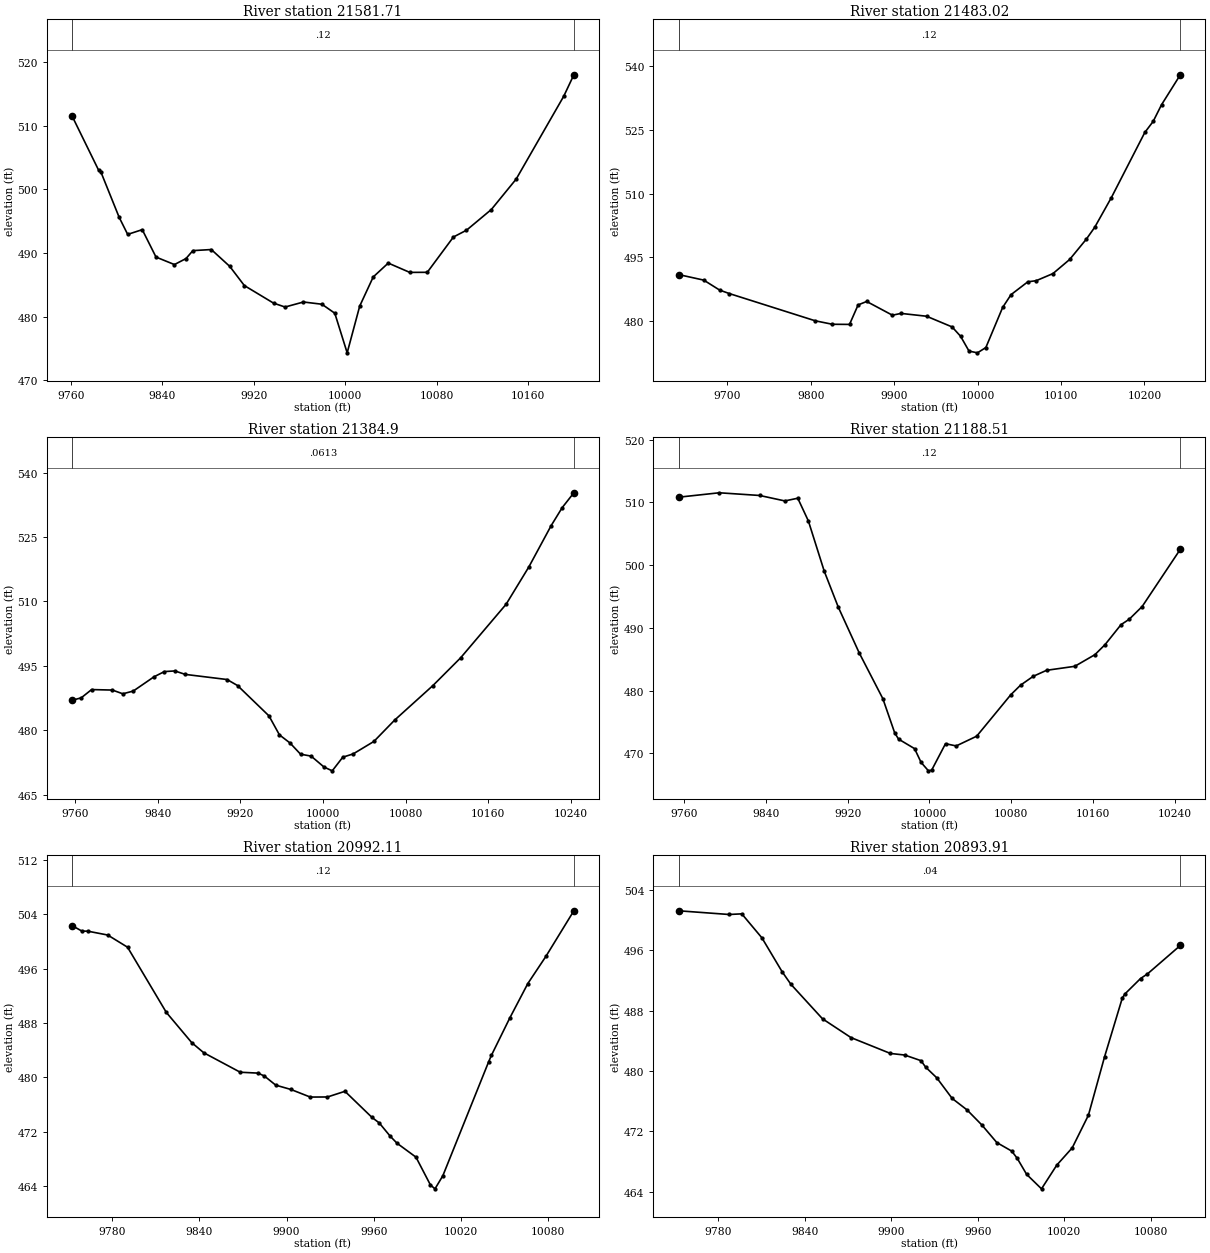
Type RM Length L Ch R = 1 ,21581.71,98.696100,98.696100,98.696100
XS GIS Cut Line= 6
795479.457454324837936.875208765795615.692127326838109.053340569
795644.087767801838121.154561694795725.007592721838169.756942663
795769.891695772838188.776123636795813.581471287 838200.04578978
#Sta/Elev= 30
9761.218511.5058 9784.33503.02979786.266502.77759802.382495.59429809.833492.9093
9822.585 493.6539834.614489.3465 9850.73488.1702 9860.84489.11619866.846490.3612
9882.963490.53039899.095487.88369911.847484.87319937.351482.11649947.427481.5021
9963.543482.29099979.659481.94119990.927480.527710001.75474.306910012.73481.6567
10024.54486.228410037.67488.403610056.46486.942210071.78486.954310094.65492.5001
10106.08 493.56510127.79496.815210149.52501.597910191.09514.601210199.95517.9776
#Mann= 3 , 0 , 0
9761.218    0.12       09761.218    0.12       010199.95    0.12       0
#XS Ineff= 2 , 0
       0                               0
Bank Sta=9761.218,10199.95
Exp/Cntr=0.3,0.1

Type RM Length L Ch R = 1 ,21483.02,98.111600,98.111600,98.111600
XS GIS Cut Line= 6
 795265.61607331838133.542800099795535.110180676838197.946904182
795614.549911529838212.738518357795755.838654965838225.430405498
795802.139163852838225.192799851795857.465788811838221.198231474
#Sta/Elev= 30
9641.403 490.9559671.614489.64729690.695487.30229702.459 486.4769805.275480.0843
9825.838479.26649846.401479.23569856.683483.81649866.965484.62629897.809 481.398
9908.091 481.8219938.753481.15699969.323478.64629979.507476.45699989.632472.9659
9999.755472.552210009.84473.800910029.97483.228310040.02486.231110060.12489.2472
10070.17489.511110090.26 491.182 10110.3494.499810130.34499.290110140.36502.0709
10160.36 509.06810200.39524.358710210.42526.956210220.45530.874910242.97537.9164
#Mann= 3 , 0 , 0
9641.403    0.12       09641.403    0.12       010242.97    0.12       0
#XS Ineff= 2 , 0
       09925.787                       0
Bank Sta=9641.403,10242.97
Exp/Cntr=0.3,0.1

Type RM Length L Ch R = 1 , 21384.9,196.396100,196.396100,196.396100
XS GIS Cut Line= 6
795366.223228619838271.957118071795491.005079118838287.750475342
795627.601378803838313.771132471795660.592232467838316.325935801
795710.268590301838305.184943067795835.511637076838249.914435358
#Sta/Elev= 30
9756.931487.00619765.778487.57179775.858489.49519796.017489.38079806.097488.5117
9816.177489.14849836.336 492.4729846.416493.68729856.496 493.8299866.576493.0266
9907.047491.8335 9917.19 490.436 9947.62483.38039957.774478.95749968.005 477.072
9978.235474.45789988.466 474.015   10001471.462910008.92470.586210019.14473.7636
10029.21474.525110049.27477.427510069.41482.401710106.44490.432110133.24 496.875
 10177.3509.340310199.33518.023110220.95527.639310231.67531.838310242.95535.2869
#Mann= 3 , 0 , 0
9756.931  0.0613       09756.931  0.0613       010242.95  0.0613       0
#XS Ineff= 2 , 0
       0                               0
Bank Sta=9756.931,10242.95
Exp/Cntr=0.3,0.1

Type RM Length L Ch R = 1 ,21188.51,196.396100,196.396100,196.396100
XS GIS Cut Line= 6
795427.397795929838645.213514223795505.916995138838596.184302254
795569.927714886838541.499011843795621.248896517838476.701829776
795644.099733697838398.878128532795755.197361999838300.068136019
#Sta/Elev= 30
9754.237510.81159794.078511.51819833.703511.08849858.346510.21899871.007510.6512
9881.387507.03079896.954499.01119910.663493.30369931.127 486.0189954.342478.7017
9965.967473.23929969.745472.25819985.388470.74329991.804468.5429    9999467.2056
10002.14467.317710015.69471.529510026.17471.174610046.21 472.726 10079.6479.3245
10089.15480.853510101.53482.263310114.68483.2269 10142.3483.863610162.02485.7194
10171.94487.319610187.57490.498810195.63491.365310208.29493.394210245.66502.5163
#Mann= 3 , 0 , 0
9754.237    0.12       09754.237    0.12       010245.66    0.12       0
#XS Ineff= 2 , 0
       0                               0
Bank Sta=9754.237,10245.66
Exp/Cntr=0.3,0.1

Type RM Length L Ch R = 1 ,20992.11,98.198100,98.198100,98.198100
XS GIS Cut Line= 6
795620.401471163838672.958290626795657.066266555838633.500270012
795687.473855384838596.077478628795751.777969746838498.635928197
795788.574886428838454.994614621795830.232198054838399.706130057
#Sta/Elev= 30
 9752.48502.33779759.236501.53259763.344 501.5189776.995500.95159790.645499.1577
9817.296489.56479834.782485.11139843.066483.61699868.158480.75019880.431480.6193
9884.792480.18499892.579478.84939903.046478.21039916.315477.09359928.183477.1067
9940.184477.94179958.754474.10289963.787473.2835 9971.34 471.3249976.058470.2876
9989.037468.2464    9999464.148610002.12463.580610007.52465.5042 10039.1482.3205
10040.94483.239410053.46488.685910065.98493.8059 10078.5497.835310097.65504.5226
#Mann= 3 , 0 , 0
 9752.48    0.12       0 9752.48    0.12       010097.65    0.12       0
#XS Ineff= 2 , 0
       0                               0
Bank Sta=9752.48,10097.65
Exp/Cntr=0.3,0.1

Type RM Length L Ch R = 1 ,20893.91,98.198000,98.198000,98.198000
XS GIS Cut Line= 6
795630.469168174838686.339412129795740.180021736838582.439148822
795773.424523865838566.825856051795853.309452486838544.371550194
795894.452313223838519.011008751795913.737848873838498.222374906
#Sta/Elev= 30
9752.479501.21859787.529500.72719796.356500.81289810.356 497.6239824.357493.1375
9830.394491.48829852.358486.90659872.141484.41599899.486482.31559909.346482.1074
9920.705481.35879923.845480.51569931.617479.09049942.294476.3592 9952.63 474.837
9962.966472.82899973.303470.50759983.639469.37869987.416  468.439993.975466.2981
10004.29464.379610014.88467.5202 10025.6469.809810036.82474.126410048.05  481.88
10060.38489.676710062.27490.220810073.01492.244310077.79492.8522 10100.6496.6234
#Mann= 3 , 0 , 0
9752.479    0.04       09752.479    0.04       0 10100.6    0.04       0
#XS Ineff= 2 , 0
       0                               0
Bank Sta=9752.479,10100.6
Exp/Cntr=0.3,0.1

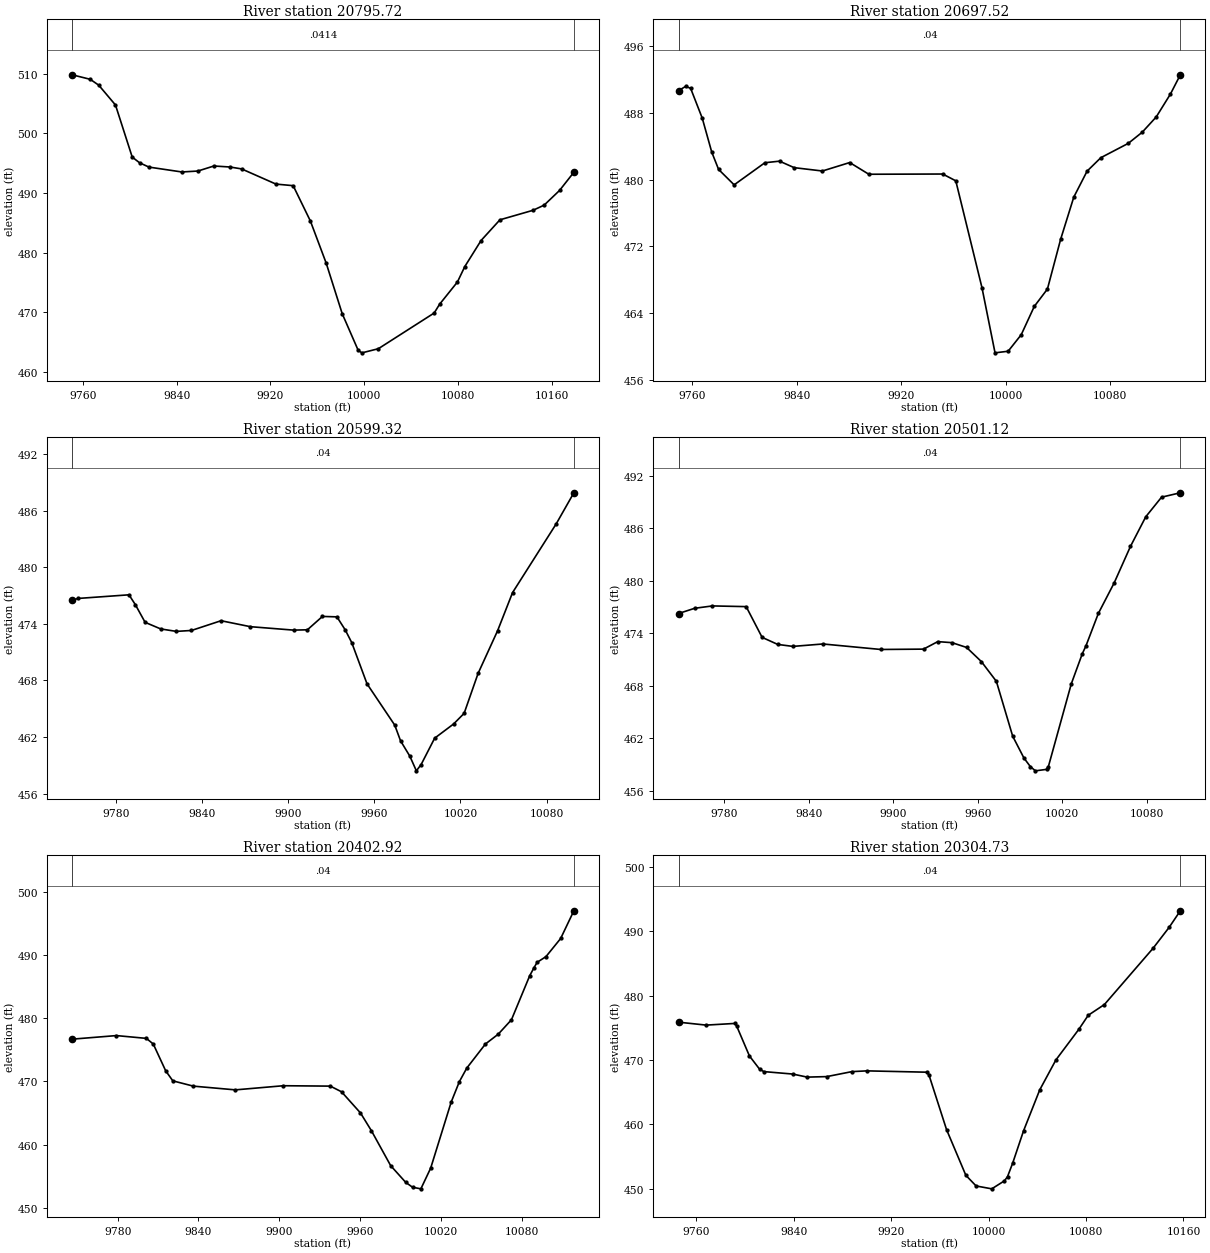
Type RM Length L Ch R = 1 ,20795.72,98.198100,98.198100,98.198100
XS GIS Cut Line= 6
795643.967775241838820.946042145795820.269758219838636.703646317
795870.391514609838604.138760397795893.856629406 838582.62019601
795922.728553033838541.249632295795936.344579378838514.080827646
#Sta/Elev= 30
9750.908509.7861 9766.38509.02839773.652508.04159787.915504.72049802.178495.9996
9808.452495.04489816.441 494.3259844.444493.50799858.115493.66329871.786494.5088
9885.458494.34049895.351 494.0239924.681491.47769939.346491.21329954.011485.2987
9967.486478.24149981.158469.76469994.829463.60779998.006 463.21510011.91463.9028
10059.51469.883910064.15471.355810079.33475.077210085.63477.668210099.49482.0288
10115.56485.494510143.77487.090210153.25487.953910166.36490.410310178.57493.4594
#Mann= 3 , 0 , 0
9750.908  0.0414       09750.908  0.0414       010178.57  0.0414       0
#XS Ineff= 2 , 0
       0                               0
Bank Sta=9750.908,10178.57
Exp/Cntr=0.3,0.1

Type RM Length L Ch R = 1 ,20697.52,98.198000,98.198000,98.198000
XS GIS Cut Line= 6
795839.273973603838879.280774452795874.831405611838828.961557874
 795897.31085653838779.457493379795912.593044251838705.630700138
795916.796879154838586.923536141795941.912093617838517.986397335
#Sta/Elev= 30
 9749.42 490.6299754.867491.1415 9758.68490.90929767.592487.33429774.851483.2795
9780.091481.2097    9792479.36389815.543482.0095 9826.76482.19779837.977  481.42
9859.575481.02019880.502482.03169895.129 480.6329951.703480.65929961.718479.8449
9981.748467.0781 9991.77459.272910001.81459.465210011.83461.439610021.84464.8302
10031.88466.900210041.98 472.84110052.08 477.90110062.26481.003710072.77482.6101
 10093.8484.325710104.52485.665210115.19487.484610126.09490.226710133.65492.5287
#Mann= 3 , 0 , 0
 9749.42    0.04       0 9749.42    0.04       010133.65    0.04       0
#XS Ineff= 2 , 0
       0                               0
Bank Sta=9749.42,10133.65
Exp/Cntr=0.3,0.1

Type RM Length L Ch R = 1 ,20599.32,98.198100,98.198100,98.198100
XS GIS Cut Line= 6
 795983.95293996838848.369490979796020.558885851838781.032871634
 796032.41075542838695.396612441796020.347339651838645.006556632
 795969.98229789838589.271113546795963.026076333838532.797698642
#Sta/Elev= 30
9749.666476.49279753.665 476.7079789.271477.09389793.713 476.0499800.515474.1711
9811.385473.47069822.256473.21099832.777473.30939853.362474.34329873.776473.7104
9903.855473.34539913.459473.37979923.938474.79919934.017474.75339939.846473.3559
 9944.33472.01999954.965467.64299974.273463.25619978.296461.5947 9984.81459.9503
9989.303 458.4069992.605459.068610002.04461.872710015.24463.382910022.55464.5103
10032.29468.757910045.85473.281510056.27477.332110086.67484.633910098.93487.9265
#Mann= 3 , 0 , 0
9749.666    0.04       09749.666    0.04       010098.93    0.04       0
#XS Ineff= 2 , 0
       0                               0
Bank Sta=9749.666,10098.93
Exp/Cntr=0.3,0.1

Type RM Length L Ch R = 1 ,20501.12,98.198000,98.198000,98.198000
XS GIS Cut Line= 6
795989.089268091838854.106573874796017.050076103838814.772351619
796037.221471422838769.615029818796063.411116804838646.670408703
796100.643334408838592.851631864796131.079047706838533.125818965
#Sta/Elev= 30
9747.539476.25359759.017476.8521 9771.62477.12169795.579477.04099806.907473.5262
9818.006472.71999828.785472.49469850.126472.7717 9891.21472.14319921.537472.1837
9931.645473.03989941.754472.92249952.115472.37569962.604470.76289973.276 468.503
9984.863462.23279992.842459.73849997.406458.7582   10001458.270510008.97458.4392
10010.19458.7388 10026.5 468.22110034.33471.666710036.89472.5491 10045.7476.2609
10056.93479.747510068.51483.923510079.38487.3105 10090.6489.551810103.93490.0543
#Mann= 3 , 0 , 0
9747.539    0.04       09747.539    0.04       010103.93    0.04       0
#XS Ineff= 2 , 0
       0                               0
Bank Sta=9747.539,10103.93
Exp/Cntr=0.3,0.1

Type RM Length L Ch R = 1 ,20402.92,98.198100,98.198100,98.198100
XS GIS Cut Line= 6
796020.967542542838862.730919452796069.660639192838817.128589456
796106.983044444838771.456546838 796136.41807107838724.557913114
796183.526216199838632.107567713796230.616354952838558.010145774
#Sta/Elev= 30
9746.116476.69549779.042477.26249801.313476.82099806.443 475.9249815.654471.6879
9820.951470.10099836.162469.2655 9867.41468.67389903.084469.32899937.929469.2666
9946.236468.37349960.341465.02049968.396462.23089982.752456.68729993.958454.0336
    9999453.269110005.19453.015710012.47456.291210027.72466.751910033.83469.9961
10039.29472.120210053.15475.931710062.66477.485910072.47479.765510086.04486.7381
10089.17487.979110091.54488.8532 10098.1489.753310109.01492.623410118.82497.0079
#Mann= 3 , 0 , 0
9746.116    0.04       09746.116    0.04       010118.82    0.04       0
#XS Ineff= 2 , 0
       0                               0
Bank Sta=9746.116,10118.82
Exp/Cntr=0.3,0.1

Type RM Length L Ch R = 1 ,20304.73,98.198000,98.198000,98.198000
XS GIS Cut Line= 6
796035.879044965838870.682616396796131.769362094838809.718370167
796174.725581204 838778.63390667796243.759819506838722.668929029
796258.268092964838710.723640579796361.943161507838620.206948726
#Sta/Elev= 30
9745.477475.86789768.135475.41129791.835475.67299793.346475.20549803.685 470.626
9811.984468.58429815.535468.20079839.234467.82179851.084467.34559867.155 467.425
9887.781468.19679900.125468.31529949.625468.10789951.125467.64249965.491459.2127
9981.356452.11649989.768 450.46610002.61450.019210013.07451.266410015.56451.9141
10019.79454.004810028.73459.0232   10042465.365110055.28470.012210074.11474.7599
10081.83476.9391 10095.1478.603510134.93487.301410148.21490.562510157.42493.1425
#Mann= 3 , 0 , 0
9745.477    0.04       09745.477    0.04       010157.42    0.04       0
#XS Ineff= 2 , 0
       0                               0
Bank Sta=9745.477,10157.42
Exp/Cntr=0.3,0.1