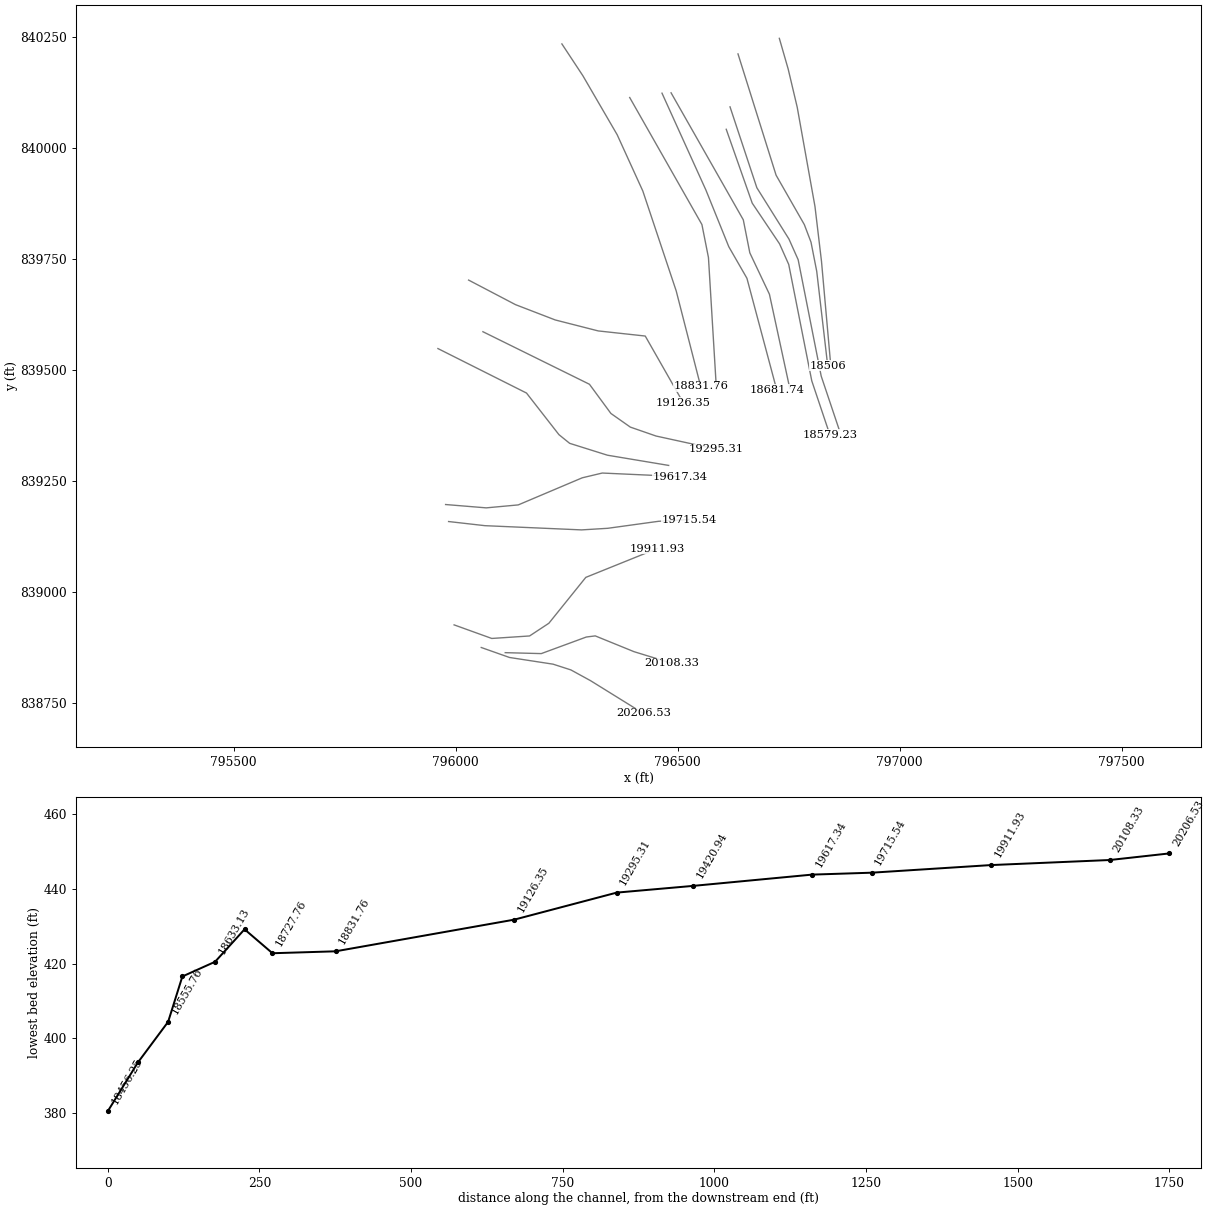
HEC-RAS study 18254_ras.prj: 18254

--- 18254_ras.g01 (geometry) --- (continued)

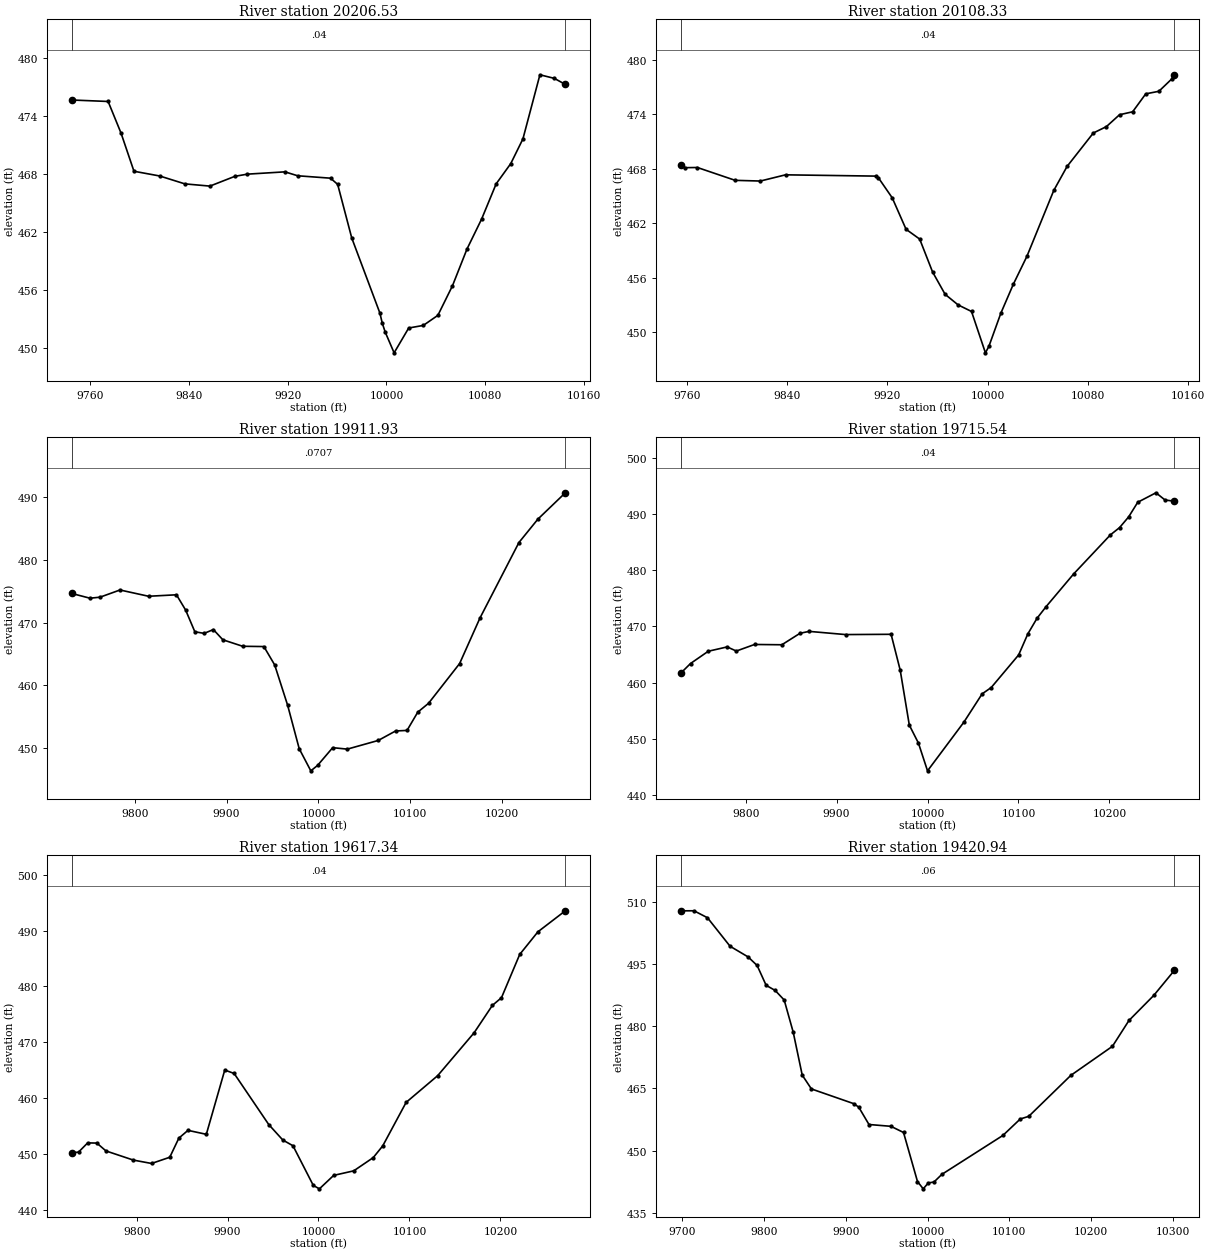
Type RM Length L Ch R = 1 ,20206.53,98.198100,98.198100,98.198100
XS GIS Cut Line= 6
796057.808622701838875.630707729796121.357769887838853.163046464
796219.495629728838838.092192816796259.654687384838825.147140878
796303.775994934838800.999487306796422.718819833838727.261319378
#Sta/Elev= 30
9745.354475.68379774.842475.53089785.294472.25519795.747468.30829816.555467.8185
9836.928467.00179857.186 466.7719877.365467.78259887.455468.00859917.855468.2463
9928.183  467.849954.749467.59099960.524 466.9499971.905461.40499994.666453.6329
9996.646452.5644    9999451.654410006.18449.513210017.98452.083210029.77452.3502
10041.57453.392410053.36456.447710065.15460.263610076.95463.355610088.74467.0083
10100.53469.098510110.37471.653610124.12478.293510135.75477.923110144.69477.2949
#Mann= 3 , 0 , 0
9745.354    0.04       09745.354    0.04       010144.69    0.04       0
#XS Ineff= 2 , 0
       0                               0
Bank Sta=9745.354,10144.69
Exp/Cntr=0.3,0.1

Type RM Length L Ch R = 1 ,20108.33,196.396100,196.396100,196.396100
XS GIS Cut Line= 6
796111.788861318838863.997975537796192.944056328838861.882826862
796294.400686905838899.212538484796314.518247203838901.762032766
796401.867855521 838866.21090522796486.798048472838840.134823058
#Sta/Elev= 30
 9755.07468.39959758.314468.14249768.414468.16079798.585466.74719818.635466.6697
9838.731 467.3549910.592467.21339912.902467.01629923.872464.81959934.911461.3549
9945.774460.27679956.044456.65829966.064 454.1929976.413453.02889987.122452.3037
9998.224447.7474   10001448.467210010.56452.122310020.49 455.30310031.35458.3864
10052.75465.633210063.38468.2819 10084.3  471.9610094.76472.666710105.22473.9729
10115.68474.296510126.14 476.27410136.61476.554510147.07477.938910148.95478.3738
#Mann= 3 , 0 , 0
 9755.07    0.04       0 9755.07    0.04       010148.95    0.04       0
#XS Ineff= 2 , 0
       0                               0
Bank Sta=9755.07,10148.95
Exp/Cntr=0.3,0.1

Type RM Length L Ch R = 1 ,19911.93,196.396100,196.396100,196.396100
XS GIS Cut Line= 6
795996.648704078838926.582696698796081.468969677 838895.99904211
796166.645671248838901.618435503796210.082453165838930.239629365
796293.246326475 839033.54186193796453.995283322839098.382543805
#Sta/Elev= 30
9731.328  474.679751.301473.90969762.185474.07369783.953475.22149815.028474.2209
9845.422474.45479855.424472.01559865.427468.56069875.517468.30349885.611  468.91
9895.929467.28089917.501466.24689940.594466.20149952.347463.27459966.432456.8524
 9979.06449.91369991.689446.3878    9999447.2457 10015.5 450.08210031.42449.8488
10065.14451.234410083.99452.743810096.43452.830510108.14 455.74610119.84457.1513
10153.68463.489410175.78470.734910218.26482.789810238.89486.516110268.79490.7189
#Mann= 3 , 0 , 0
9731.328  0.0707       09731.328  0.0707       010268.79  0.0707       0
#XS Ineff= 2 , 0
       0                               0
Bank Sta=9731.328,10268.79
Exp/Cntr=0.3,0.1

Type RM Length L Ch R = 1 ,19715.54,98.198000,98.198000,98.198000
XS GIS Cut Line= 6
795984.259474498839159.307309626796066.023959975839150.005342143
796283.675131624839140.487798159796342.677552994839144.077019307
796456.834037329839159.819394985796525.179931323839163.820718095
#Sta/Elev= 30
9728.458461.68799739.308463.42099758.846465.60159779.632466.37119789.671465.6353
9809.751466.80439839.777466.75279859.792468.79639869.799469.1296 9909.83468.5638
9959.936468.61159969.958462.2349 9979.98452.47169989.998449.2826   10000444.3516
10040.03453.009410060.06458.027910070.08459.156110100.23464.948310110.32468.6789
10120.42471.453710130.51473.5442 10160.8479.351410201.18486.281810211.21487.5654
10221.22489.471810231.24492.074410251.28493.757610261.29492.466710271.49492.2647
#Mann= 3 , 0 , 0
9728.458    0.04       09728.458    0.04       010271.49    0.04       0
#XS Ineff= 2 , 0
       0                               0
Bank Sta=9728.458,10271.49
Exp/Cntr=0.3,0.1

Type RM Length L Ch R = 1 ,19617.34,196.396100,196.396100,196.396100
XS GIS Cut Line= 6
795977.511163921839197.611230033796068.976053595839190.111237641
796141.132456752839196.766423907 796285.24949963839257.789309606
796330.322623511839268.530588169796505.025360019839260.604376652
#Sta/Elev= 30
 9728.53450.28349736.072450.39879746.144452.04889756.215452.01499766.286450.6086
9796.385448.97499816.399 448.3729836.416449.48059846.425452.89919856.445454.2885
9876.636453.58199896.914465.06879907.237 464.4529945.283455.32799960.755452.5609
9971.933 451.536 9994.29444.4479   10001443.837810016.72446.242510038.78447.0553
10060.16449.412110070.62451.504710096.38459.287510131.11464.066910171.16 471.728
10191.22476.615710201.25 477.99410221.31485.727410241.37489.775910271.49493.5259
#Mann= 3 , 0 , 0
 9728.53    0.04       0 9728.53    0.04       010271.49    0.04       0
#XS Ineff= 2 , 0
       0  9899.7                       0
Bank Sta=9728.53,10271.49
Exp/Cntr=0.3,0.1

Type RM Length L Ch R = 1 ,19420.94,125.635900,125.635900,125.635900
XS GIS Cut Line= 6
795960.221075699839548.863895956 796159.71499723839448.689578809
796232.758055882839354.988049515796256.916667193839335.428488704
796342.093608216839308.683388596796479.909593176839285.682675268
#Sta/Elev= 30
9698.017 507.8079714.323507.8208 9730.82 506.1429758.459 499.2739780.527496.7017
9791.561494.63859802.594489.85289813.628488.62199824.662486.32189835.696478.5717
 9846.73 468.2229857.946464.88989909.908461.33049915.893460.48859928.377456.3191
9955.222455.88319970.646454.39449987.715442.58319994.729440.8156   10001442.2436
10007.87442.453810017.55444.305910092.22453.686310113.46457.650510123.81458.2831
10175.32468.1601 10226.2  475.1610246.42481.383710276.75487.421310301.93493.4475
#Mann= 3 , 0 , 0
9698.017    0.06       09698.017    0.06       010301.93    0.06       0
#XS Ineff= 2 , 0
       0                               0
Bank Sta=9698.017,10301.93
Exp/Cntr=0.3,0.1

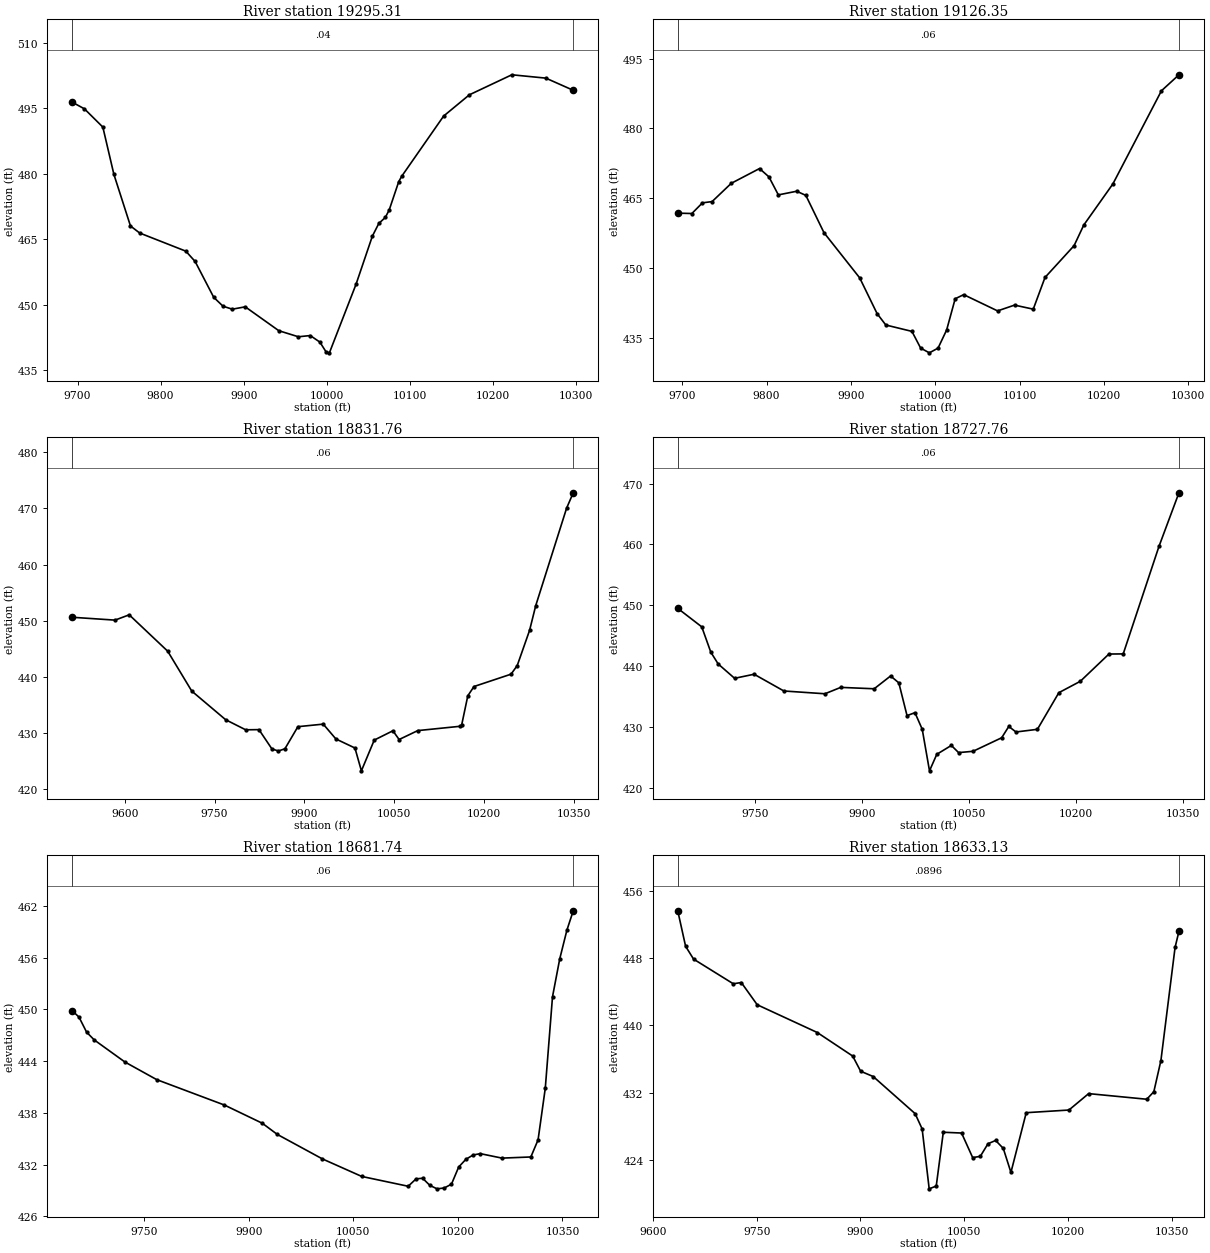
Type RM Length L Ch R = 1 ,19295.31,168.958300,168.958300,168.958300
XS GIS Cut Line= 6
796061.537660018839586.816816046796301.461151978839468.466054841
796349.832475289 839402.68323296796393.530880841839371.981759651
796451.483049987839351.884825214796587.270901367839322.201029765
#Sta/Elev= 30
9693.283496.42759708.214494.87899730.397 490.7029743.717479.86759763.672468.0692
9774.763466.45359830.354462.30129841.556459.94029863.962451.73819875.165449.6938
9886.368449.0153 9901.96449.55549942.381444.0883 9965.95442.70129980.277442.9793
9991.863441.47769999.526439.176710003.34439.0218 10035.4454.702810055.09465.7297
10062.84468.635210070.71470.024410075.38471.727610086.89478.229810090.61479.4887
10140.95493.226510171.95498.091510223.13502.678910264.08 501.91210297.11499.1271
#Mann= 3 , 0 , 0
9693.283    0.04       09693.283    0.04       010297.11    0.04       0
#XS Ineff= 2 , 0
       0                               0
Bank Sta=9693.283,10297.11
Exp/Cntr=0.3,0.1

Type RM Length L Ch R = 1 ,19126.35,294.594100,294.594100,294.594100
XS GIS Cut Line= 6
796029.336201163839703.102097027796134.870237047839647.813478183
796224.427576456839613.297527712796321.306819743839588.592659317
796427.124641328839577.078752355796512.676107675839426.946497604
#Sta/Elev= 30
9694.602 461.8059711.365461.72479723.918  464.029735.341464.28789758.097468.2171
9791.588471.38829802.752469.60229813.912465.72859835.665466.51229846.541465.6204
9868.068457.59769910.399 447.8979931.056440.21069941.384437.7647 9972.37436.3947
9982.698432.80189993.027431.783610003.34 432.79810013.53436.692510023.64443.4034
10033.75444.289410073.95440.796410094.04 442.04110116.26441.170310130.17 447.978
 10164.7 454.822 10176.2459.258110210.73468.091810268.28488.097710289.06491.5408
#Mann= 3 , 0 , 0
9694.602    0.06       09694.602    0.06       010289.06    0.06       0
#XS Ineff= 2 , 0
       0                               0
Bank Sta=9694.602,10289.06
Exp/Cntr=0.3,0.1

Type RM Length L Ch R = 1 ,18831.76,104.000000,104.000000,104.000000
XS GIS Cut Line= 6
796239.415419544840234.967664727  796286.5759117 840163.46525656
796363.926277996840030.409093771796421.660645322839903.695810556
796496.849874755839678.728852673796551.817015946839464.278956831
#Sta/Elev= 30
9511.832450.61999583.668 450.1129607.383451.05419671.649444.59329711.926437.4921
9768.601432.39929802.042430.60649824.236430.6378 9845.93427.19949856.777426.8416
9867.624427.23259889.318431.16289931.677431.61569952.839428.97679984.661427.3697
9995.434423.309210016.93428.7796 10048.1430.432110058.49428.878310089.66430.4649
10160.97431.237910162.96431.430710173.28436.650810183.61438.303510245.55440.4989
10255.87442.025710276.52448.287310286.84452.699110338.46 470.03610349.52472.7576
#Mann= 3 , 0 , 0
9511.832    0.06       09511.832    0.06       010349.52    0.06       0
#XS Ineff= 2 , 0
       09914.482        10043.39       0
Bank Sta=9511.832,10349.52
Exp/Cntr=0.3,0.1

Type RM Length L Ch R = 1 ,18727.76,46.019800,46.019800,46.019800
XS GIS Cut Line= 4
796392.119204551840114.249253064796554.781402171839828.159960806
796569.494565785839753.776744813796587.477321267839457.061278835
#Sta/Elev= 30
9642.238449.49259675.885446.45199688.531442.29969698.891 440.3529721.898437.9979
9749.227438.66599790.918435.91449848.435435.45799870.619436.50599917.455436.2777
9940.462438.38319951.965437.24959963.469431.86689974.558432.35119984.752429.6271
9994.946422.794210005.14425.507610025.53426.968410035.72425.789110055.95426.0058
10096.03428.227810106.05430.088810116.06429.177810146.12 429.61610176.17435.6372
10206.23437.5067 10246.3 441.98410266.34442.008610316.43459.673210344.42468.4814
#Mann= 3 , 0 , 0
9642.238    0.06       09642.238    0.06       010344.42    0.06       0
#XS Ineff= 2 , 0
       09949.741        10037.48       0
Bank Sta=9642.238,10344.42
Exp/Cntr=0.3,0.1

Type RM Length L Ch R = 1 ,18681.74,48.602900,48.602900,48.602900
XS GIS Cut Line= 5
796464.867624581840124.058028802796563.772779942839905.812768713
796615.268852592 839778.29868415796656.138751417839707.185060069
796723.165385634839456.243880868
#Sta/Elev= 30
9646.672449.85949656.617 449.1059667.596447.34919678.575446.45169722.491443.8967
9768.125441.85389865.217438.90859919.514436.80159941.083435.505810005.79432.6658
10062.21430.634610128.79429.496910140.16430.355610149.49430.424910159.84429.6028
10170.19429.198210180.54429.298310190.89429.737910201.24431.726110211.59432.6233
10221.94433.121210232.29433.275610263.34432.758710304.75432.8912 10315.1434.8742
10325.45440.8551 10335.8451.454210346.15455.8389 10356.5459.188910365.56461.4212
#Mann= 3 , 0 , 0
9646.672    0.06       09646.672    0.06       010365.56    0.06       0
#XS Ineff= 2 , 0
       09940.732        10043.16       0
Bank Sta=9646.672,10365.56
Exp/Cntr=0.3,0.1

Type RM Length L Ch R = 1 ,18633.13,53.902600,53.902600,53.902600
XS GIS Cut Line= 5
796485.302574039840124.875426784796647.964771688839838.786134526
796662.677935272839764.402918532796706.817426085839671.219549045
796752.591712803839459.513472766
#Sta/Elev= 30
9635.826453.68099647.186449.44479658.689447.91669716.142444.97219727.709 445.122
9750.716442.46999837.534439.15969888.756436.3495 9900.26434.53999918.462433.9045
9978.978429.48419989.171  427.669999.365420.508410009.56420.842910019.75 427.258
10046.17427.165810062.22424.234510073.28424.386710084.35425.886910095.41426.2817
10106.48425.333110117.54422.469410139.67429.594110201.38429.9098 10229.9431.8684
10313.92431.196710324.15432.097110334.38435.818510354.84449.306310360.46451.2341
#Mann= 3 , 0 , 0
9635.826  0.0896       09635.826  0.0896       010360.46  0.0896       0
#XS Ineff= 2 , 0
       09934.183        10040.53       0
Bank Sta=9635.826,10360.46
Exp/Cntr=0.3,0.1

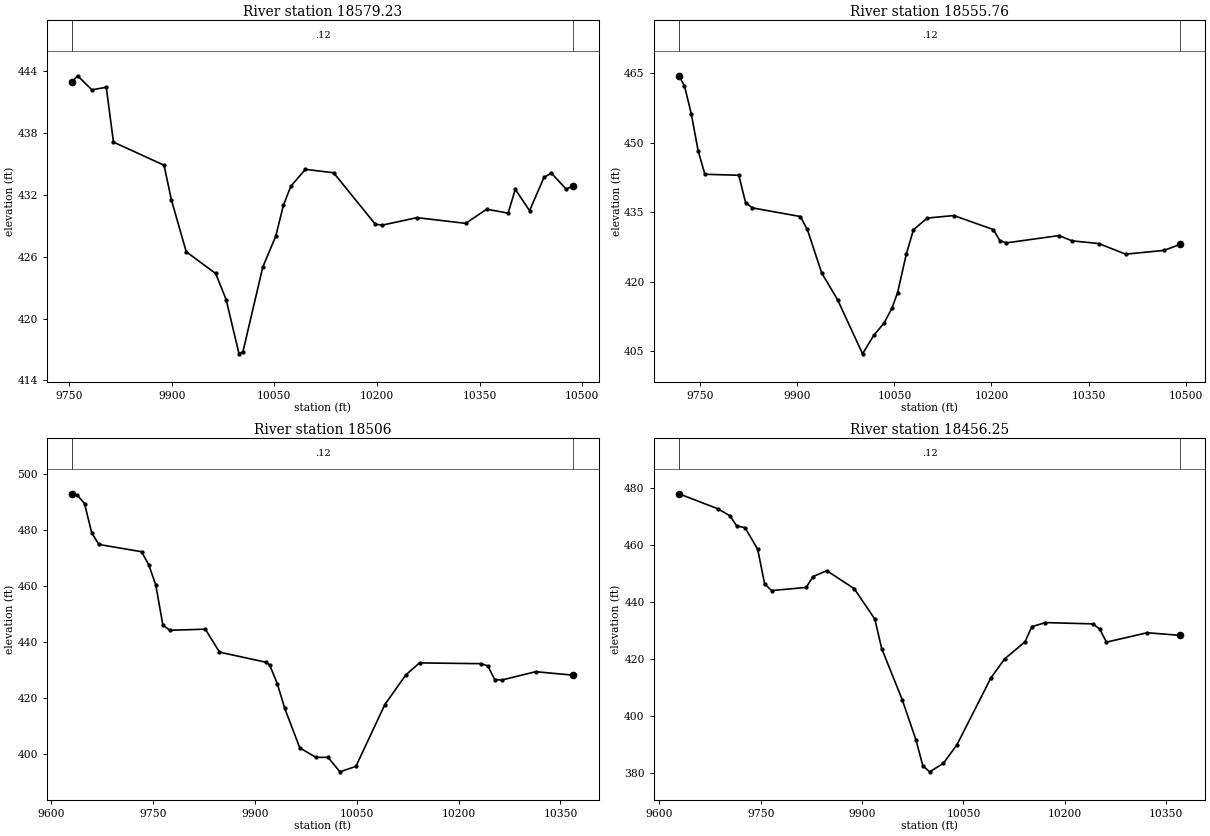
Type RM Length L Ch R = 1 ,18579.23,23.474700,23.474700,23.474700
XS GIS Cut Line= 6
796609.547032647840042.691574147796668.042908074839876.416515861
796729.597133438839784.746749196 796750.29713201839738.261178859
796802.153745002839476.223665762796842.916900488839354.776691669
#Sta/Elev= 30
9754.086442.93689762.159443.54079783.152 442.1789804.145442.42789814.642437.1102
9888.655434.86539899.292431.53159921.075426.4751 9964.09424.36969979.422421.8428
9998.288416.576710004.05416.793110033.05424.996810051.96427.974510063.16430.9727
10074.09432.831110095.36434.469210136.62434.1343 10197.7429.141910207.84429.0577
10258.53 429.78310329.82429.229410360.55430.605110391.87  430.2210402.31432.5324
10423.19 430.46110444.31433.683410455.04434.1052 10476.5432.564210487.47432.8386
#Mann= 3 , 0 , 0
9754.086    0.12       09754.086    0.12       010487.47    0.12       0
#XS Ineff= 2 , 0
       09926.364        10063.44       0
Bank Sta=9754.086,10487.47
Exp/Cntr=0.3,0.1

Type RM Length L Ch R = 1 ,18555.76,49.754700,49.754700,49.754700
XS GIS Cut Line= 6
796618.063222207840093.244584869796678.496837758839911.019927166
796750.849480863839795.372922909796771.549479435839748.887352572
796823.406092427839486.849839475796864.169247913839365.402865381
#Sta/Elev= 30
9716.686464.4863 9725.34462.28439735.836456.27529746.333448.33159756.829 443.216
9809.312443.00719819.808437.07449830.304435.95679904.467434.08979915.303431.2915
9937.335421.94669962.174416.079810000.64404.4389   10018408.432410033.77411.0678
10045.96414.253810054.74417.621210068.38426.015310079.27431.225410100.51433.7537
10141.78434.307610202.84431.272110212.98428.882910223.12428.402810304.27429.9772
10324.73428.833910365.71428.260810407.47425.9663 10466.7426.778210491.98428.0877
#Mann= 3 , 0 , 0
9716.686    0.12       09716.686    0.12       010491.98    0.12       0
#XS Ineff= 2 , 0
       09927.968        10080.85       0
Bank Sta=9716.686,10491.98
Exp/Cntr=0.3,0.1

Type RM Length L Ch R = 1 ,   18506,49.754700,49.754700,49.754700
XS GIS Cut Line= 6
796636.035801062840212.462627931796721.809166845839939.329289374
796785.443012602839828.009892951796800.433854529839788.537637198
  796813.3423054839722.812526113796838.117895815 839509.85372198
#Sta/Elev= 30
9630.734493.00339638.583492.50459649.102489.5072 9659.62479.12389670.138474.8943
9733.193472.27489743.618467.63539754.043460.40559764.467446.08279774.892444.1899
9827.015444.58919847.864436.38369917.073432.72219921.865431.71239932.936425.1599
9944.007416.25639966.148402.13319989.816398.765510007.69398.757610025.34393.5772
10048.82395.543610091.44417.628510122.19428.218210142.47432.531210233.07432.2547
10243.13431.432410253.19426.586110263.24426.378710313.57429.385110369.24428.1285
#Mann= 3 , 0 , 0
9630.734    0.12       09630.734    0.12       010369.24    0.12       0
#XS Ineff= 2 , 0
       0                               0
Bank Sta=9630.734,10369.24
Exp/Cntr=0.3,0.1

Type RM Length L Ch R = 1 ,18456.25,49.754800,49.754800,49.754800
XS GIS Cut Line= 6
796729.105432721840247.552914102796749.039545552840178.409571657
796769.382143048840092.449279175796809.414329268 839868.75078054
796824.068421872839745.340167683796844.479225467839516.241108962
#Sta/Elev= 30
9629.064477.95449686.441472.73079704.527470.24599714.803466.62489726.906466.1146
9745.632458.50199755.908446.36049766.184444.0298 9817.32445.13629827.507448.9385
 9847.88450.99989888.528444.68639918.958434.01979929.102423.70929959.532405.7574
9979.819391.65449989.963 382.63110000.11380.5079 10020.4383.500510040.54 390.046
10090.89  413.5210111.03420.095510141.24426.109210151.27  431.3910171.34432.8069
10241.55432.365110251.58430.565810261.62425.960110321.87429.256310370.93428.3291
#Mann= 3 , 0 , 0
9629.064    0.12       09629.064    0.12       010370.93    0.12       0
#XS Ineff= 2 , 0
       0                               0
Bank Sta=9629.064,10370.93
Exp/Cntr=0.3,0.1