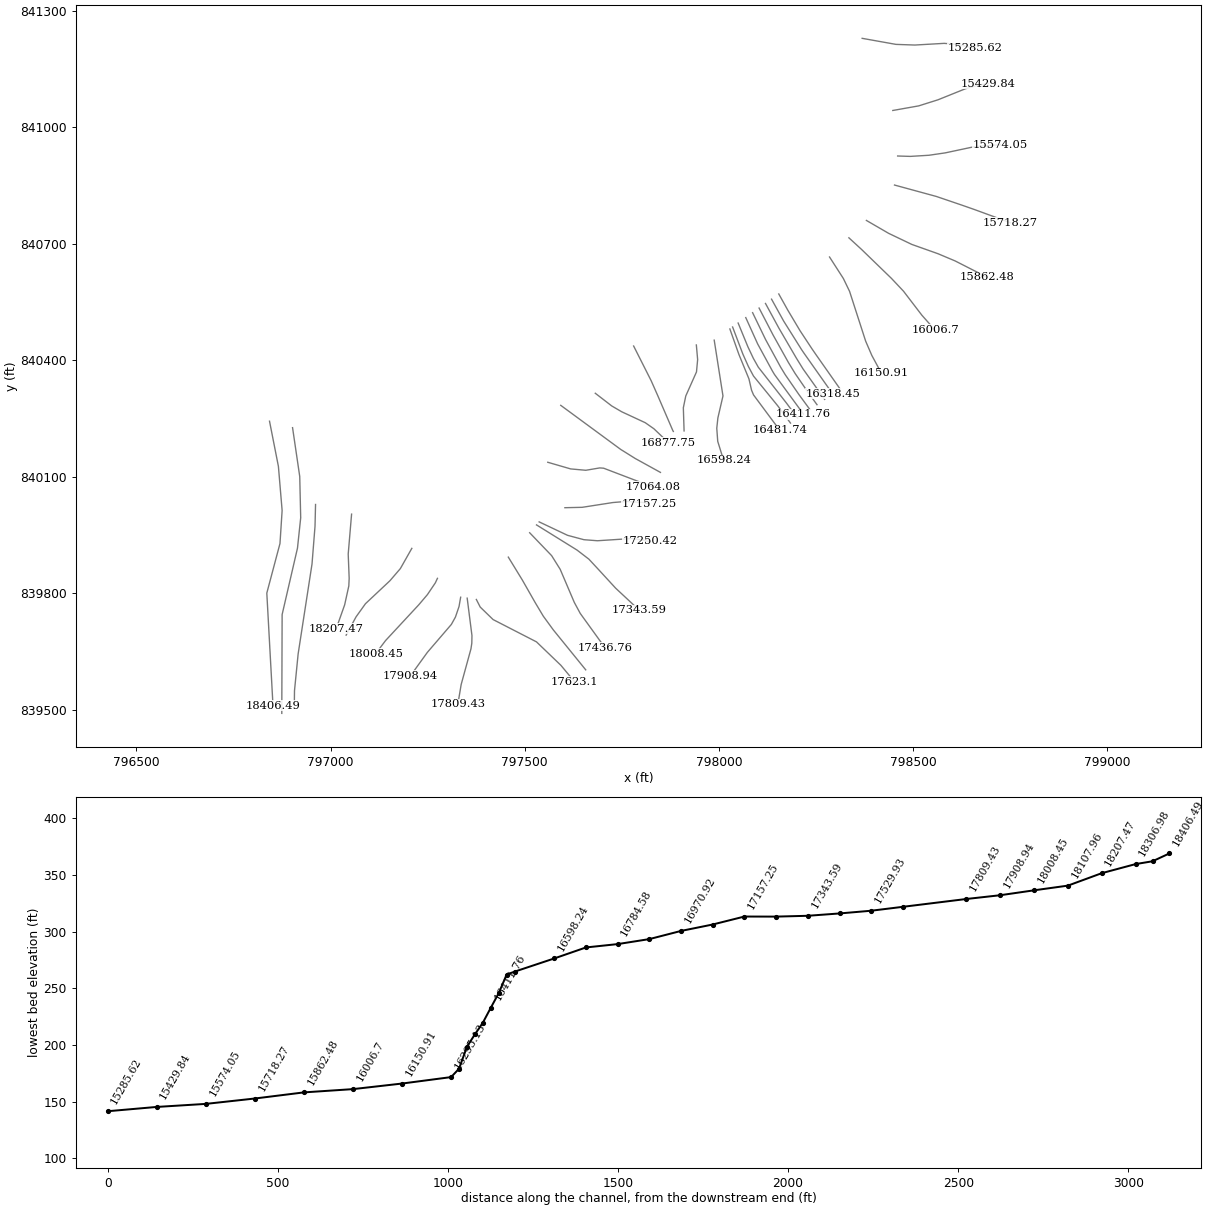
HEC-RAS study 18254_ras.prj: 18254

--- 18254_ras.g01 (geometry) --- (continued)

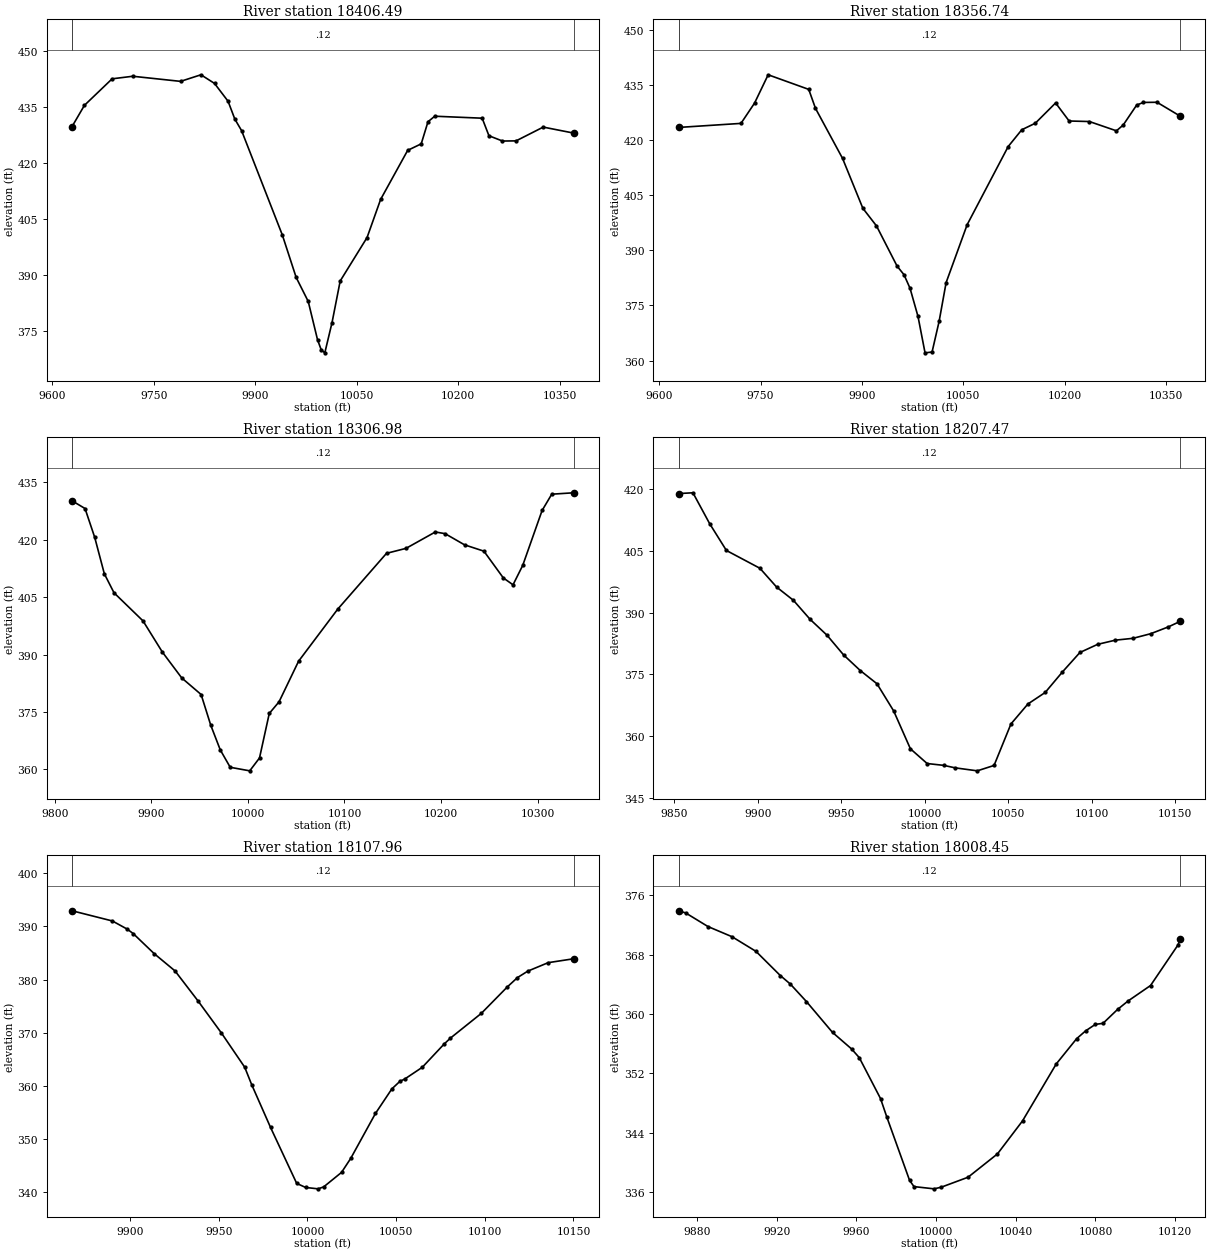
Type RM Length L Ch R = 1 ,18406.49,49.754700,49.754700,49.754700
XS GIS Cut Line= 6
 796842.85960388 840242.84285557796865.748106487 840126.49177491
796875.313698054840012.895717873796869.794177321839927.907553358
796835.892107268839800.303055721796851.844501743839509.910661954
#Sta/Elev= 30
9629.143 429.6369647.406435.31339688.349442.41719718.874443.10219789.527441.7343
9819.648 443.4999839.677441.18819859.706436.41559869.711431.63259879.714428.5364
9939.936400.59029960.395389.21519978.238382.78469991.925372.56389997.442 369.808
10002.73369.024310013.41377.132310025.46388.271710065.16399.901310085.21410.1106
10125.21423.256110145.23424.999410155.24430.923510165.25432.399910235.32431.8695
10245.34427.167710265.36425.753310285.41425.795310325.58429.486710370.85427.8708
#Mann= 3 , 0 , 0
9629.143    0.12       09629.143    0.12       010370.85    0.12       0
#XS Ineff= 2 , 0
       0                               0
Bank Sta=9629.143,10370.85
Exp/Cntr=0.3,0.1

Type RM Length L Ch R = 1 ,18356.74,49.754700,49.754700,49.754700
XS GIS Cut Line= 6
796902.170654703840226.242008116796920.667658288840100.425100276
796923.137083514839994.244775982796914.851946847 839916.05641376
796875.341362257839745.041055157796874.445718182839490.563320721
#Sta/Elev= 30
9628.617423.46789721.041424.57119741.176430.10659761.283  437.819821.351433.8325
9831.351428.65899871.374415.04769901.449401.45259921.651  396.659952.135385.7015
  9962.4383.3537 9971.32379.65289983.092371.99749993.501362.0867 10003.9 362.306
 10014.3370.6244 10024.7381.213510055.87396.9947 10116.6418.271510136.69422.8339
10156.74424.616110186.77430.139110206.78425.223710236.79425.0787 10276.8422.5486
 10286.8424.116410306.81429.571310316.83430.280310336.88430.323210371.39426.5264
#Mann= 3 , 0 , 0
9628.617    0.12       09628.617    0.12       010371.39    0.12       0
#XS Ineff= 2 , 0
       0                               0
Bank Sta=9628.617,10371.39
Exp/Cntr=0.3,0.1

Type RM Length L Ch R = 1 ,18306.98,99.509400,99.509400,99.509400
XS GIS Cut Line= 6
796961.371340425840028.430101842796960.036076992839972.700082086
796952.290161612839875.217157884796916.529988117839643.458742037
796907.160774317839548.881790967  796906.7589284839512.100093346
#Sta/Elev= 30
9817.791430.17899831.225428.15929841.228420.64469851.231411.09629861.234406.1375
9891.293398.78479911.356390.63179931.419383.87579951.482379.54699961.514371.4913
9971.327365.07089981.643360.520310001.86359.593810011.98362.9574 10022.1374.5941
10032.22377.632110052.46388.249510092.95401.836810143.55416.446110163.79417.7498
10194.15422.030210204.27 421.58810224.38418.671410244.48417.013310264.58410.0202
10274.63408.219610284.68413.290710304.76427.655510314.76431.908710337.66432.2765
#Mann= 3 , 0 , 0
9817.791    0.12       09817.791    0.12       010337.66    0.12       0
#XS Ineff= 2 , 0
       0                               0
Bank Sta=9817.791,10337.66
Exp/Cntr=0.3,0.1

Type RM Length L Ch R = 1 ,18207.47,99.509400,99.509400,99.509400
XS GIS Cut Line= 6
797054.167264569840003.601152432797045.469882065839900.828327227
797047.940053039839838.325367921797047.028851004839818.703433097
797036.297147327839769.913913264797014.437884132839708.269415593
#Sta/Elev= 30
9852.442418.87519861.074419.06599871.109411.55899881.145405.05999901.217400.7446
9911.252396.17249921.288392.97349931.324388.3412 9941.36384.53089951.395379.7051
 9961.41375.9101 9971.41372.7067 9981.41366.11039991.433356.926510001.47353.3505
10011.49352.898610018.18352.306410031.52351.574910041.58 352.88410051.71362.9564
10061.88 367.80210072.23370.596510082.57375.575810093.05380.300110103.66382.2769
10114.27383.292410124.88383.740810135.49384.8603 10146.1386.520410153.24 387.873
#Mann= 3 , 0 , 0
9852.442    0.12       09852.442    0.12       010153.24    0.12       0
#XS Ineff= 2 , 0
       0                               0
Bank Sta=9852.442,10153.24
Exp/Cntr=0.3,0.1

Type RM Length L Ch R = 1 ,18107.96,99.509400,99.509400,99.509400
XS GIS Cut Line= 6
797209.247471851839915.428823036797179.765096491839863.365694459
797152.876411238 839832.03755354 797089.96540969839772.993645927
797065.747983584839739.187563061797040.120615485839692.021156978
#Sta/Elev= 30
9867.316392.96059890.044 391.0399898.396389.50559901.814388.65719913.585384.8923
9925.355381.63199938.304375.98629951.482369.9532 9964.66363.48469968.564360.2115
9979.188352.16349993.953341.6033    9999 340.83910005.99340.578810009.15 340.942
10019.23343.675210024.41 346.31310038.36354.783610047.61 359.41110052.15360.8331
10054.92361.276710064.75363.474610077.05367.850510080.62368.970910098.03373.6316
10112.78378.644310118.43380.377410124.25381.592410135.73383.185510150.21383.9273
#Mann= 3 , 0 , 0
9867.316    0.12       09867.316    0.12       010150.21    0.12       0
#XS Ineff= 2 , 0
       0                               0
Bank Sta=9867.316,10150.21
Exp/Cntr=0.3,0.1

Type RM Length L Ch R = 1 ,18008.45,99.509400,99.509400,99.509400
XS GIS Cut Line= 6
 797275.23322247839838.237944919797269.853416314839826.677650211
797249.386743794839796.305638552797227.125895607839770.097379213
797141.712881406839678.098134653797115.981595756839644.027475573
#Sta/Elev= 30
 9870.66373.93159874.231373.64289885.434371.80639897.492370.43749909.551368.4595
9921.748365.20389926.811364.04869934.869361.69819947.989357.52989957.522355.3103
9961.425354.12919972.103348.60819975.165346.19029986.685337.58189988.905  336.74
    9999336.438410002.62336.662510016.04 338.00210030.81341.1478 10043.4345.5972
10060.34353.279710070.58356.686910075.11357.743410079.96358.610810083.84358.7552
 10091.1360.621710096.37361.762810107.69363.853410121.44369.306210122.65 370.066
#Mann= 3 , 0 , 0
 9870.66    0.12       0 9870.66    0.12       010122.65    0.12       0
#XS Ineff= 2 , 0
       0                               0
Bank Sta=9870.66,10122.65
Exp/Cntr=0.3,0.1

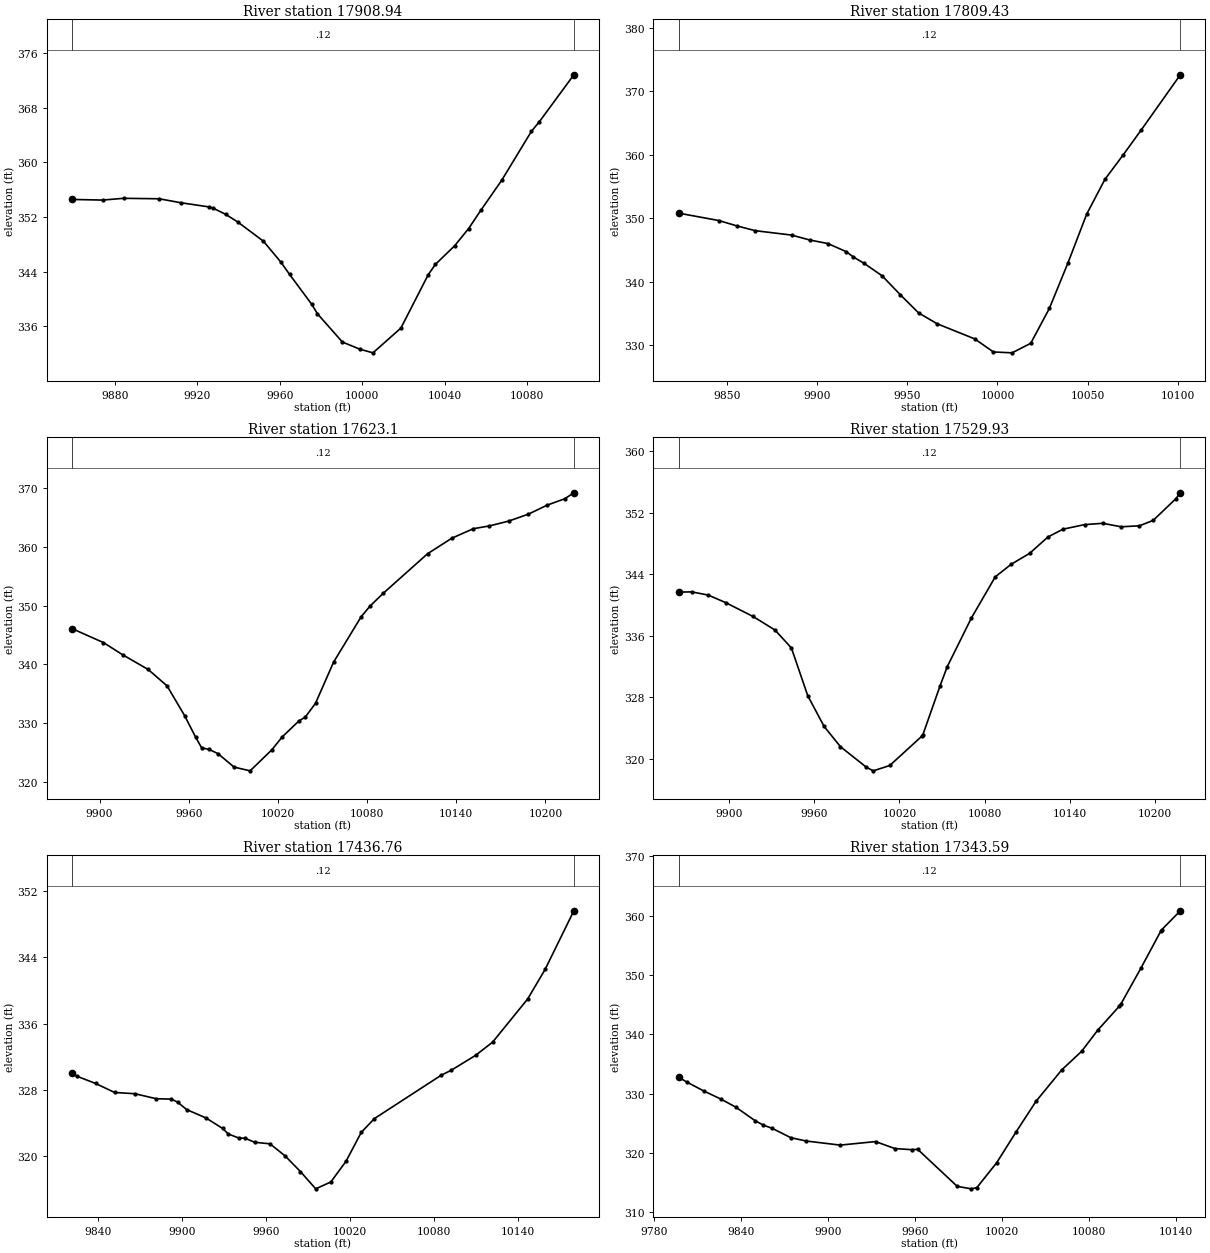
Type RM Length L Ch R = 1 ,17908.94,99.509400,99.509400,99.509400
XS GIS Cut Line= 6
797334.991905743839789.620557943 797330.82561943839765.698739519
797321.538718622 839738.52903515797311.098553372839719.634306331
797249.360678492839647.771497841797205.984393664839587.661106798
#Sta/Elev= 27
9859.173354.55189874.013354.45699884.193354.71789901.466 354.6479912.168354.0595
9925.688353.45639927.624353.28059933.755352.36749939.554351.26439952.067348.4453
9960.534345.38769964.775343.58449975.569339.19329978.293337.8237 9990.43333.6845
    9999  332.6310005.27332.106810018.83335.731710032.12343.5526 10035.6345.0558
10044.88347.7606 10051.7350.287410057.64352.9645 10067.8357.366510082.19364.5127
10086.11365.9429 10102.8372.7904
#Mann= 3 , 0 , 0
9859.173    0.12       09859.173    0.12       0 10102.8    0.12       0
#XS Ineff= 2 , 0
       0                               0
Bank Sta=9859.173,10102.8
Exp/Cntr=0.3,0.1

Type RM Length L Ch R = 1 ,17809.43,186.337600,186.337600,186.337600
XS GIS Cut Line= 6
797351.818250442839787.216794411  797364.0919443839690.899315046
797363.719121256 839671.27814898797361.524292833839656.692970644
797336.347627853839565.020497516797327.744225361839513.735494707
#Sta/Elev= 25
9822.962 350.7899845.336349.62199855.421348.77289865.506348.02519885.675347.3336
9895.759346.55879905.844345.99769915.929344.73419920.064343.87499925.964342.8777
9935.966340.91649946.037337.94479956.196335.0759 9966.58333.35219987.349330.9829
9997.733328.920510008.12328.780910018.47 330.28210028.82335.779210039.18342.9796
10049.53350.631910059.67 356.11910069.81359.969910079.95363.945310101.51372.5823
#Mann= 3 , 0 , 0
9822.962    0.12       09822.962    0.12       010101.51    0.12       0
#XS Ineff= 2 , 0
       0                               0
Bank Sta=9822.962,10101.51
Exp/Cntr=0.3,0.1

Type RM Length L Ch R = 1 , 17623.1,93.168800,93.168800,93.168800
XS GIS Cut Line= 6
797375.415511385839783.845757128797385.393601497839764.238592753
 797418.56213311839732.068249502797530.283211455839674.648699326
797593.164954898839614.239284999797628.837563627 839571.27777272
#Sta/Elev= 30
9881.542346.09649902.688343.71639915.626341.63639932.752339.13989945.464336.3427
9957.335331.25139964.694327.60029968.739325.79169973.847325.52149979.806324.7869
9990.599322.506410001.35321.875710015.98325.463410023.05327.685810034.28 330.393
10038.39331.012410045.35333.379110057.55340.412510076.04348.113310082.25349.9965
10090.87 352.10310120.74 358.85210137.08361.498710151.54363.116710162.29363.5866
10175.36364.417210188.37365.571510201.39 367.14410213.09 368.22310219.18369.2344
#Mann= 3 , 0 , 0
9881.542    0.12       09881.542    0.12       010219.18    0.12       0
#XS Ineff= 2 , 0
       0                               0
Bank Sta=9881.542,10219.18
Exp/Cntr=0.3,0.1

Type RM Length L Ch R = 1 ,17529.93,93.168900,93.168900,93.168900
XS GIS Cut Line= 6
797457.731241388839892.862369974797493.742684415839833.991374118
  797527.0480744839775.552672983797547.831725844839740.774131113
797573.524419334 839705.55314785797657.012854623839602.677946415
#Sta/Elev= 30
9864.725341.67249873.942341.71239885.664341.28859897.819340.31539916.982 338.523
9932.554336.74419944.087334.41479955.599328.1973 9967.11324.19589978.621321.5603
9996.841318.891310001.64318.423110013.29319.1182   10036322.960610036.59323.1424
10048.66329.486710053.68331.971510070.65338.305110087.45343.6631 10098.7345.3049
10111.58346.715910124.46348.845410135.06349.864110150.22350.4588 10163.1350.6313
10175.98350.177410188.85350.305110198.54351.014210214.41353.8227 10217.6354.6026
#Mann= 3 , 0 , 0
9864.725    0.12       09864.725    0.12       0 10217.6    0.12       0
#XS Ineff= 2 , 0
       0                               0
Bank Sta=9864.725,10217.6
Exp/Cntr=0.3,0.1

Type RM Length L Ch R = 1 ,17436.76,93.168800,93.168800,93.168800
XS GIS Cut Line= 6
797512.674710543839955.654906168797569.275991038839896.666031499
797591.317923664839861.415608526797627.587271856839776.378426774
797642.937322823839747.881174254 797707.29577487839658.716140657
#Sta/Elev= 30
9821.656330.06029824.829329.64729838.475328.75559852.012327.66749866.532327.5156
 9881.77326.90899892.478326.86649897.008326.49679903.524325.59329917.283324.5888
9929.077323.32639933.182322.65139940.871322.15179945.098322.14369952.082321.6471
9962.968 321.4649973.853319.98969984.739318.10419995.624316.021210006.45316.8542
10017.32319.368110028.18322.850310037.55324.512710085.17329.743610092.44330.3568
10109.77332.147910121.93333.746910146.93338.953510159.43342.535410179.96 349.623
#Mann= 3 , 0 , 0
9821.656    0.12       09821.656    0.12       010179.96    0.12       0
#XS Ineff= 2 , 0
       0                               0
Bank Sta=9821.656,10179.96
Exp/Cntr=0.3,0.1

Type RM Length L Ch R = 1 ,17343.59,93.168800,93.168800,93.168800
XS GIS Cut Line= 6
797530.326156063839975.827986769797634.773863183839910.957421178
797665.250715559839887.568503915797692.775790997839857.891032904
797734.118780871839812.881135299797794.836848964839756.276976228
#Sta/Elev= 30
9797.153332.77869802.655 331.9799814.426330.46059826.198329.09879836.629327.7219
9849.742325.46939855.583324.68779861.513324.17549874.536322.57559885.057322.0164
  9908.6321.32329932.996321.91749946.317320.74059958.207 320.5489962.026320.6169
9989.304314.3702    9999313.9523 10002.8314.151310016.41318.319110030.02323.5932
10043.63328.703110061.33333.9884   10075337.110110086.34340.739210101.01344.7148
10102.34345.176410116.01351.174110129.68357.392310130.34357.631910143.13 360.815
#Mann= 3 , 0 , 0
9797.153    0.12       09797.153    0.12       010143.13    0.12       0
#XS Ineff= 2 , 0
       0                               0
Bank Sta=9797.153,10143.13
Exp/Cntr=0.3,0.1

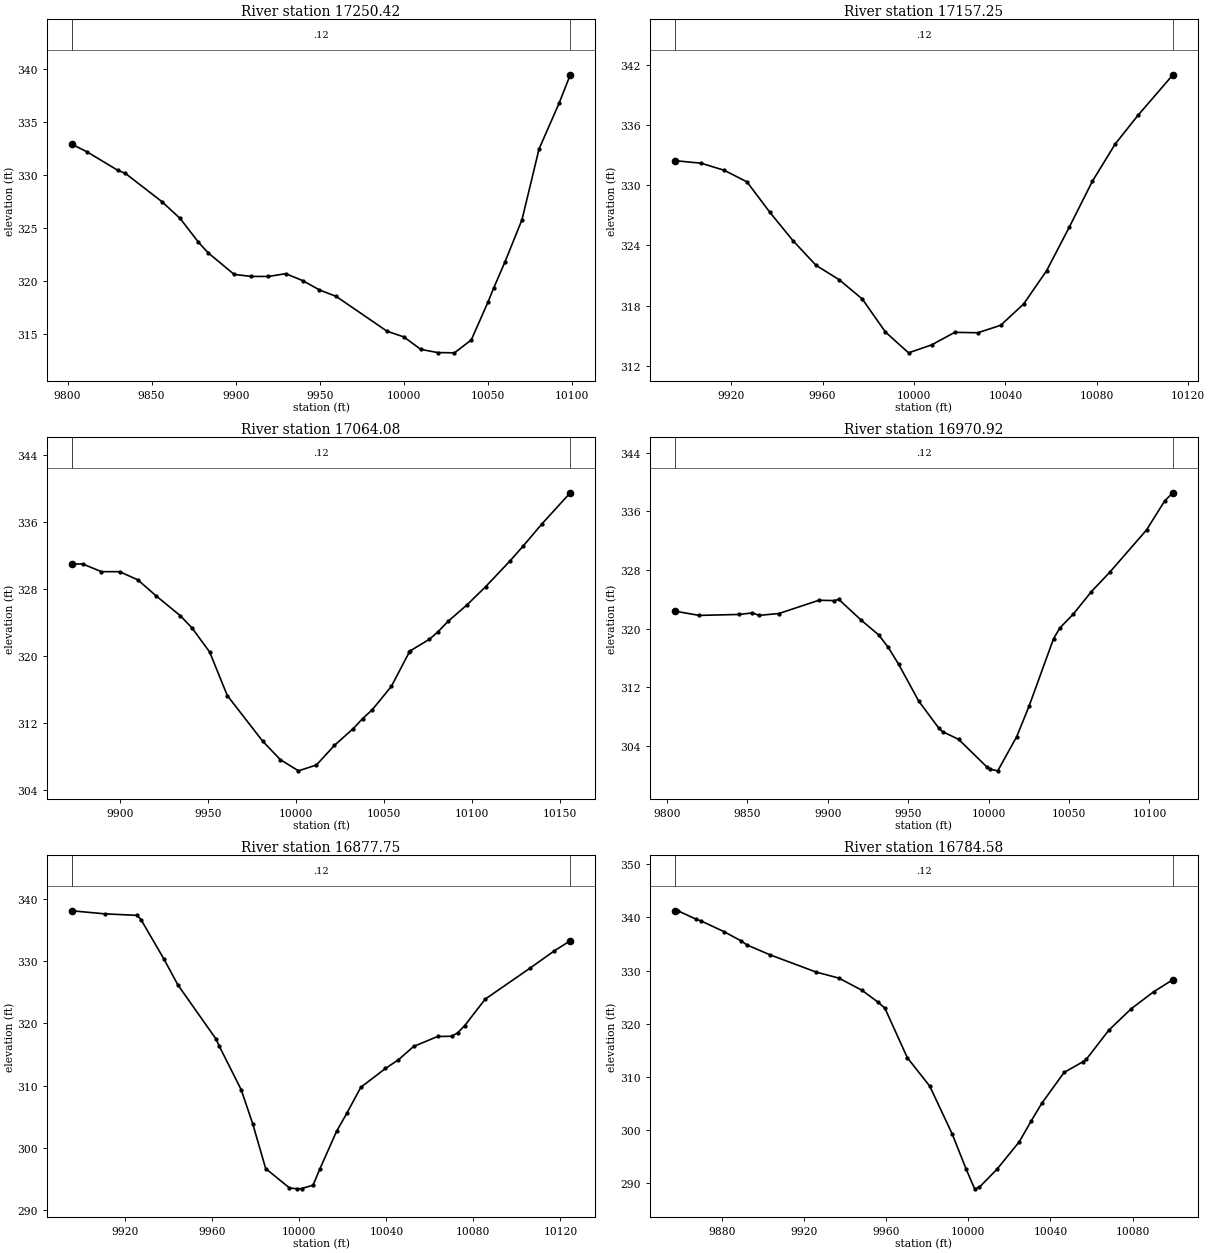
Type RM Length L Ch R = 1 ,17250.42,93.168800,93.168800,93.168800
XS GIS Cut Line= 6
797537.134450598839983.608894811797610.205445892839949.031118916
797652.499800259839937.715150133797687.297487315  839935.0585941
797778.279836559839940.979149861797823.161821463839933.114818225
#Sta/Elev= 28
 9802.56332.86859811.592332.15729829.875330.41739834.314330.13549856.077327.4765
9866.959325.88739877.841323.65599883.506322.66679899.102320.61869909.172320.4265
9919.524320.42269929.795320.68529939.824320.03819949.853319.15659959.883318.5413
9990.047 315.271 10000.1314.728810010.16313.555710020.22313.257610030.22313.2307
10040.22314.445110050.22318.0319 10053.5319.3158 10060.3321.803710070.42325.7802
10080.53332.422910092.48336.739610099.12339.4152
#Mann= 3 , 0 , 0
 9802.56    0.12       0 9802.56    0.12       010099.12    0.12       0
#XS Ineff= 2 , 0
       0                               0
Bank Sta=9802.56,10099.12
Exp/Cntr=0.3,0.1

Type RM Length L Ch R = 1 ,17157.25,93.168800,93.168800,93.168800
XS GIS Cut Line= 6
797603.392510602840020.124786661797647.768200771840021.104408322
797727.043379177840033.447298477797761.942150578 840036.32175513
797803.434523838840033.739094342797819.845896926 840030.10561126
#Sta/Elev= 22
9895.241332.46019906.874332.20169916.884331.50239926.894330.34619936.903327.3129
9946.996324.4896 9957.12322.01949967.245320.58619977.369318.65889987.494315.3649
9997.618313.290110007.73 314.08510017.84315.336710027.89315.292710037.92316.0378
10047.96318.162210057.99321.473110068.01325.857410078.02330.393510088.04334.1231
 10098.1337.0084 10113.3341.0226
#Mann= 3 , 0 , 0
9895.241    0.12       09895.241    0.12       0 10113.3    0.12       0
#XS Ineff= 2 , 0
       0                               0
Bank Sta=9895.241,10113.3
Exp/Cntr=0.3,0.1

Type RM Length L Ch R = 1 ,17064.08,93.168800,93.168800,93.168800
XS GIS Cut Line= 6
 797559.32306591840137.108163477797618.325258452840119.975882204
797657.237553362840116.486677726797693.068953792840122.564295743
797703.078873969 840121.86385803797830.280394814840073.341479261
#Sta/Elev= 30
9872.724 330.9439878.906330.94879889.516 330.0349899.846330.02879910.177329.0578
9920.508 327.1629934.274324.78789940.975323.32589951.016320.45049961.056315.2483
9981.131309.81219991.201307.596110001.53306.262710011.74306.962810021.91309.2907
10032.72311.314310037.98312.495210043.52 313.56610054.32316.345610064.42320.3985
10065.13320.597910075.93321.960510080.81322.860210086.64324.121510097.26326.0587
10107.89328.236910121.57331.271410129.15333.066310139.77335.702410156.01339.4473
#Mann= 3 , 0 , 0
9872.724    0.12       09872.724    0.12       010156.01    0.12       0
#XS Ineff= 2 , 0
       0                               0
Bank Sta=9872.724,10156.01
Exp/Cntr=0.3,0.1

Type RM Length L Ch R = 1 ,16970.92,93.168800,93.168800,93.168800
XS GIS Cut Line= 6
797592.704517676840283.687371098797747.349058736840170.008227767
 797749.30278525840168.752862087797751.040215221840167.762237488
797784.407704843 840146.88262413797849.398822111840111.032093097
#Sta/Elev= 30
9804.746322.39629820.006321.81289844.828321.93999853.181 322.1539857.239321.8159
9869.651322.07059894.473323.87839903.831323.83419906.884 323.9849920.715321.1707
9931.706319.13079937.599317.43899944.118 315.1099956.529310.1101 9968.94306.4383
9971.366 305.9389981.351304.8831    9999301.1002   10001300.812310005.67300.5884
10017.47305.268310025.06 309.38510040.36318.634210044.26320.094210052.46321.9463
10063.88 325.057 10075.3327.708110098.14333.468710109.56337.482310114.59338.5536
#Mann= 3 , 0 , 0
9804.746    0.12       09804.746    0.12       010114.59    0.12       0
#XS Ineff= 2 , 0
       0                               0
Bank Sta=9804.746,10114.59
Exp/Cntr=0.3,0.1

Type RM Length L Ch R = 1 ,16877.75,93.168900,93.168900,93.168900
XS GIS Cut Line= 6
797681.636314601840314.815024466797723.993951604840282.138642138
797749.608033764840267.190852312797810.254331055840239.000787821
797832.542422655840223.404557835 797869.98027497840187.737237614
#Sta/Elev= 30
9895.432338.12749910.618337.63139925.398337.39279927.222336.69729937.802330.3232
9944.123326.21499961.702317.47939963.122316.3804 9973.28309.31249978.615303.7905
9984.516296.63849995.458293.5234    9999293.3753   10001293.4167 10006.3293.9611
10009.35296.516510017.12302.641910021.79305.521610028.24309.709610039.59312.7511
10045.56314.149710052.54316.294210063.56 317.89510069.98317.932410072.76318.4767
10076.04319.658910085.46 323.91410106.07328.900310117.16331.666910124.54333.3011
#Mann= 3 , 0 , 0
9895.432    0.12       09895.432    0.12       010124.54    0.12       0
#XS Ineff= 2 , 0
       0                               0
Bank Sta=9895.432,10124.54
Exp/Cntr=0.3,0.1

Type RM Length L Ch R = 1 ,16784.58,93.168800,93.168800,93.168800
XS GIS Cut Line= 6
797780.408872967840436.430835424797825.600986527840346.902091438
797842.484432174840308.739396954797843.269751765840306.900029362
797881.097029841840219.161385801797882.565833643840216.446107268
#Sta/Elev= 30
9856.981341.19319858.584341.2346 9867.17 339.6989869.786339.33799880.988337.3214
9889.361335.57789892.189334.81889903.391332.96129925.795329.72639936.997328.5724
9948.198  326.299955.936324.08279959.349322.93969970.284313.61589981.219 308.257
9992.154299.2662    9999292.600110003.07288.958510005.37289.263510013.96292.6538
10024.85297.830310030.63301.737210035.74305.025310046.63310.845610055.89312.8665
10057.52 313.35410068.41318.7906 10079.3322.812510090.19325.996510099.63328.2879
#Mann= 3 , 0 , 0
9856.981    0.12       09856.981    0.12       010099.63    0.12       0
#XS Ineff= 2 , 0
       0                               0
Bank Sta=9856.981,10099.63
Exp/Cntr=0.3,0.1

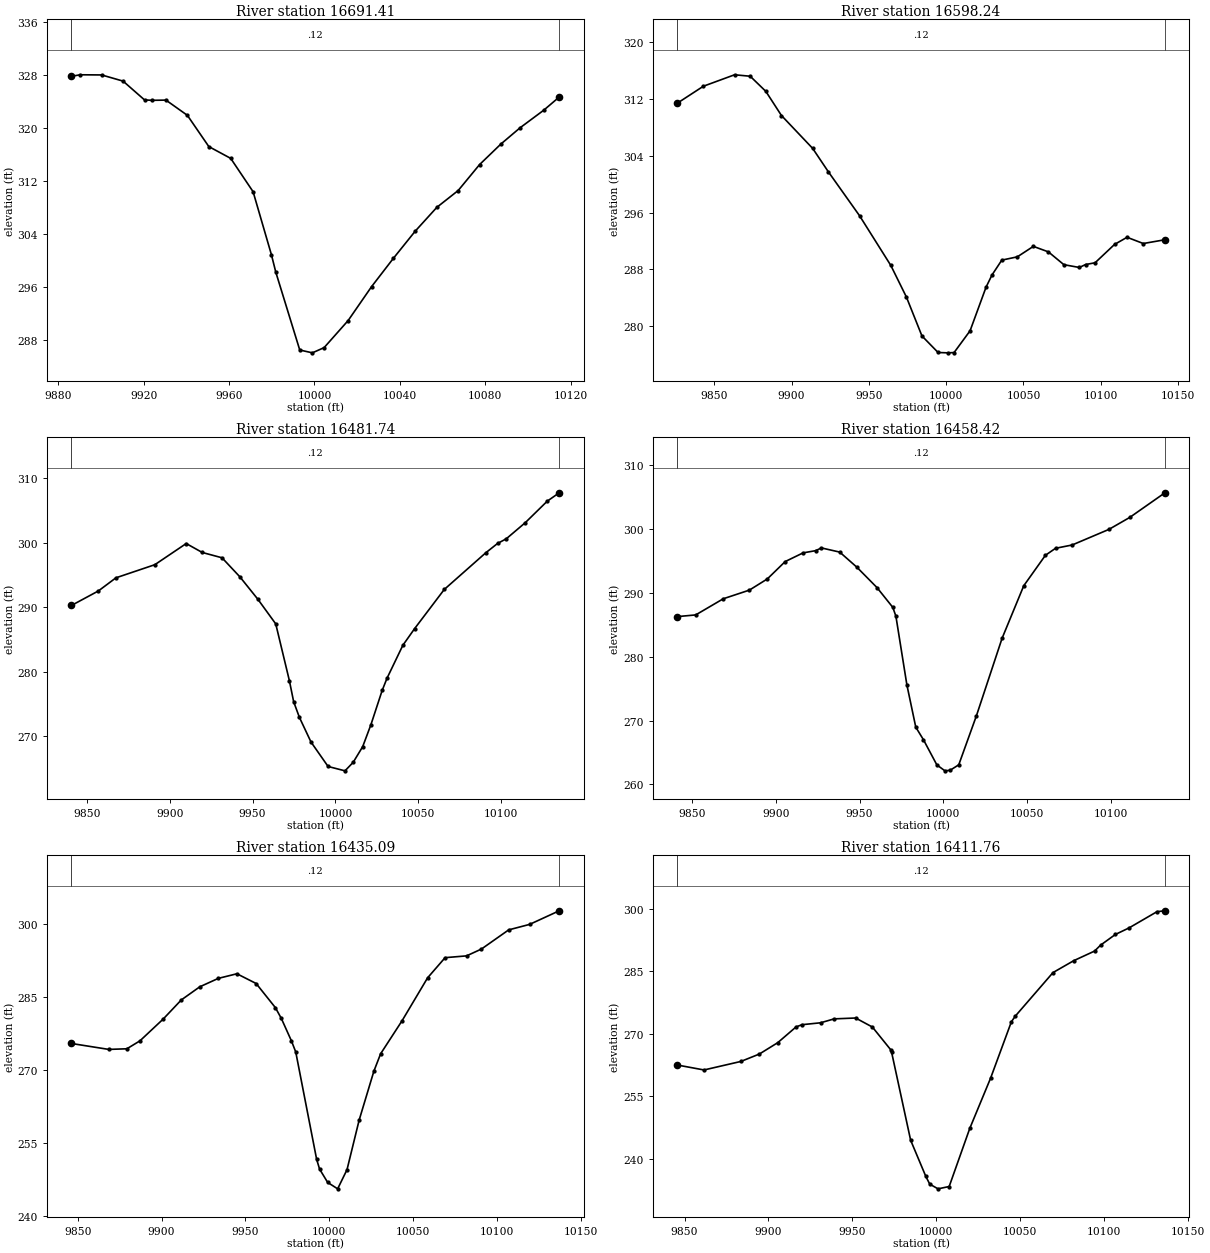
Type RM Length L Ch R = 1 ,16691.41,93.168800,93.168800,93.168800
XS GIS Cut Line= 6
797941.861017963 840439.12296946 797945.18842707840401.556414502
 797942.23773279840369.742520562797914.652769245840307.854498853
 797908.37448155840277.501333239 797910.27862585 840217.83174688
#Sta/Elev= 27
9886.121327.74179890.261327.9747  9900.3327.94899910.339327.01779920.378324.1828
9923.835324.1193 9930.42324.15139940.463321.85139950.505317.13689960.759315.3547
9971.246  310.329979.815300.82859981.878298.1783  9993.1286.4287    9999285.9992
10004.51286.786810015.77 290.87510026.74 295.99210036.95300.263410047.16304.3561
10057.32 307.96410067.32310.504210077.32314.413210087.32317.519410096.38319.9911
10107.42322.633810114.65324.6192
#Mann= 3 , 0 , 0
9886.121    0.12       09886.121    0.12       010114.65    0.12       0
#XS Ineff= 2 , 0
       0                               0
Bank Sta=9886.121,10114.65
Exp/Cntr=0.3,0.1

Type RM Length L Ch R = 1 ,16598.24,116.496100,116.496100,116.496100
XS GIS Cut Line= 6
797987.855671103840451.538059599798010.412256327840307.892940946
797997.325243149840251.333355845797994.459769335840224.701188653
797996.915029298840191.000572923798012.104353029840142.136723077
#Sta/Elev= 30
9825.916311.3328 9842.89313.73299863.106315.34559873.215315.14139883.323313.0187
9893.432 309.6269913.648305.00099923.757301.72639943.974295.5442 9964.19288.5668
9974.281284.12549984.327278.66339994.763276.3417   10001 276.29410005.11276.3332
10015.46279.3934 10025.8285.5224 10029.6287.214110035.97289.314210046.02289.7763
10056.38291.245610066.11290.474210076.14288.674210086.16288.282610090.17 288.697
10096.31288.941810108.91  291.52   10117292.522610127.51291.647810141.51292.1772
#Mann= 3 , 0 , 0
9825.916    0.12       09825.916    0.12       010141.51    0.12       0
#XS Ineff= 2 , 0
       0                               0
Bank Sta=9825.916,10141.51
Exp/Cntr=0.3,0.1

Type RM Length L Ch R = 1 ,16481.74,23.327300,23.327300,23.327300
XS GIS Cut Line= 6
798028.167451387840480.365669927798051.385804661840414.854756201
798077.303563545840351.792281481 798083.99741612840322.654641113
798089.180017842840310.418406776798156.948184932840219.138491028
#Sta/Elev= 30
 9840.57290.27189856.872292.52519867.482294.56239890.958296.5949 9909.92299.8765
9919.581 298.493 9931.54297.66719942.351294.70529953.163291.24519963.975287.4208
9972.194278.63969974.786275.36149978.254272.93329985.263269.1074 9995.58265.3165
10005.79264.639610010.75265.964210016.49268.394510021.47271.809110028.24277.1041
10031.17278.996610040.73284.103710047.85286.693110065.72292.752810090.71298.4232
10097.89299.884210103.21300.618210114.68303.116510127.94306.448910135.16 307.745
#Mann= 3 , 0 , 0
 9840.57    0.12       0 9840.57    0.12       010135.16    0.12       0
#XS Ineff= 2 , 0
       0                               0
Bank Sta=9840.57,10135.16
Exp/Cntr=0.3,0.1

Type RM Length L Ch R = 1 ,16458.42,23.327300,23.327300,23.327300
XS GIS Cut Line= 6
798035.214401031840485.405058336798061.513355581840415.950889326
798075.867393308840383.746477304798088.955156025840359.217885775
798151.323380259840282.644496814798184.264741564840238.063687127
#Sta/Elev= 30
9840.922286.28789852.048286.55449868.555289.08969884.126290.44249894.819292.1887
9905.512294.91459916.229296.27999923.753296.62829927.178297.05659938.126296.4012
9948.316294.0463 9960.36290.84759969.847287.73699971.695286.35089978.248 275.592
9983.565268.96199988.177266.97929996.171263.0428   10001262.1157 10004.1 262.206
10009.25263.061110019.84270.772410035.14282.891310048.09291.125710061.04295.9025
10067.08296.998410077.03297.516910098.97299.9594 10111.4301.831410132.46305.6998
#Mann= 3 , 0 , 0
9840.922    0.12       09840.922    0.12       010132.46    0.12       0
#XS Ineff= 2 , 0
       0                               0
Bank Sta=9840.922,10132.46
Exp/Cntr=0.3,0.1

Type RM Length L Ch R = 1 ,16435.09,23.327300,23.327300,23.327300
XS GIS Cut Line= 6
798049.472042924840495.600930158798074.536618617840434.608649975
 798088.56856899840404.820942341798101.417787927840381.928524577
798173.902386576840289.527311751798202.661658374 840250.80926348
#Sta/Elev= 30
9846.226275.52849868.498274.3112 9879.31 274.4389887.078 276.0629900.933280.5339
9911.744284.46679922.789287.17049933.843288.89989944.897289.84399956.357287.8446
9967.824282.89279971.347 280.6949977.365276.08479979.968273.78649992.412251.7535
9994.167249.7395    9999246.992610004.95245.677710010.53249.613310017.76259.7932
10026.54269.837310030.56273.411510043.37280.209410058.55289.004410068.99293.1497
10081.79293.517110090.64294.9176 10106.9298.856410119.36299.980510137.03 302.778
#Mann= 3 , 0 , 0
9846.226    0.12       09846.226    0.12       010137.03    0.12       0
#XS Ineff= 2 , 0
       0                               0
Bank Sta=9846.226,10137.03
Exp/Cntr=0.3,0.1

Type RM Length L Ch R = 1 ,16411.76,23.327300,23.327300,23.327300
XS GIS Cut Line= 6
798069.086598025840509.627617821798099.761326893840441.761518839
798137.518720207840372.420511585798138.520276327840370.689360136
798143.057441337840363.126564317798217.643361759840261.188744257
#Sta/Elev= 30
9845.569 262.5069861.622261.3086 9883.57263.35519894.544265.12699905.518267.8613
9916.492271.66599920.046272.1852    9931272.63789939.131273.58049951.911 273.787
9961.904271.61529972.822266.1558 9973.29 265.6649984.677244.42939993.733235.7334
9996.063233.8829   10001232.759710007.63233.319310019.89247.271610032.28259.3262
10044.67272.876710046.98 274.22910069.45284.695110081.84287.561910094.23289.8662
10097.78291.281510106.63293.857410114.72295.417710131.41299.327810136.13299.5403
#Mann= 3 , 0 , 0
9845.569    0.12       09845.569    0.12       010136.13    0.12       0
#XS Ineff= 2 , 0
       0                               0
Bank Sta=9845.569,10136.13
Exp/Cntr=0.3,0.1

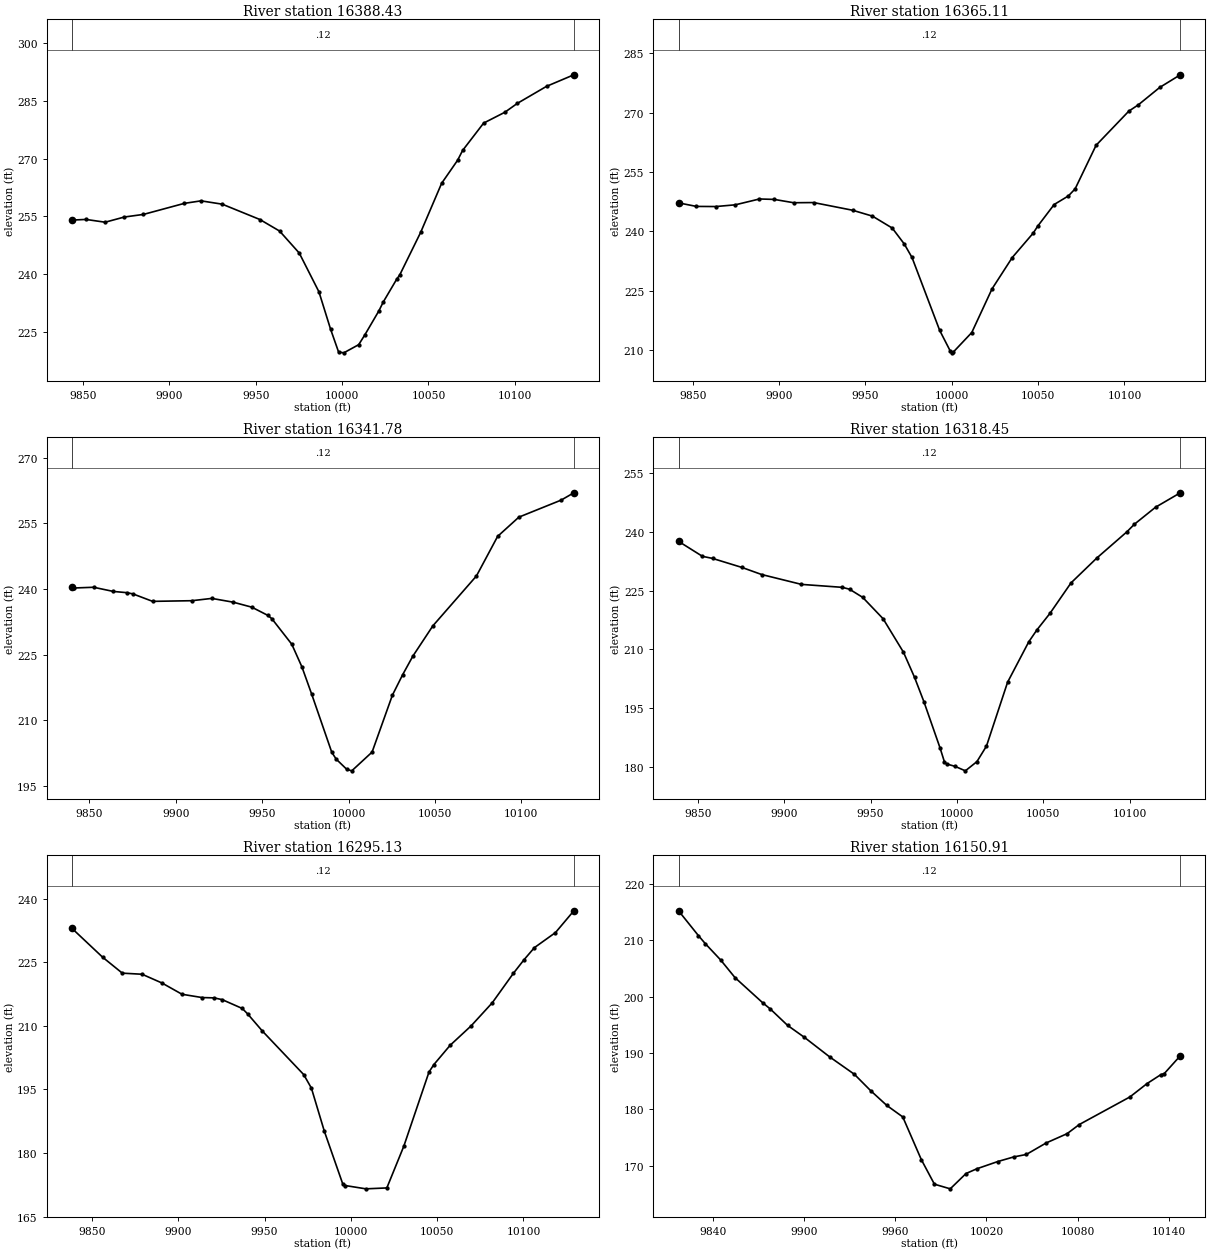
Type RM Length L Ch R = 1 ,16388.43,23.327300,23.327300,23.327300
XS GIS Cut Line= 6
798086.734848916840522.248169334798119.948190206840453.456684772
798158.711820924840382.371160173798170.560835165840362.804621786
798205.837441213840311.695059124798234.357941163840272.768779662
#Sta/Elev= 30
9843.642 254.0279851.691254.19139862.795253.4717  9873.9254.81669885.004255.4968
9908.651258.36179918.318259.01539930.596258.15339952.433254.16729963.819251.1754
9975.205245.46489986.592235.41869993.332225.72619997.978219.7817   10001219.5689
10009.62 221.68710013.14224.193210021.31230.454810023.87232.776810031.69238.7221
10033.36239.754210045.51250.830610057.66263.5722 10066.9269.548210069.81272.0988
10081.96279.188310094.28282.010910101.48284.3084 10118.4288.731710134.23291.7353
#Mann= 3 , 0 , 0
9843.642    0.12       09843.642    0.12       010134.23    0.12       0
#XS Ineff= 2 , 0
       0                               0
Bank Sta=9843.642,10134.23
Exp/Cntr=0.3,0.1

Type RM Length L Ch R = 1 ,16365.11,23.327300,23.327300,23.327300
XS GIS Cut Line= 6
 798103.40418448 840534.16868256798139.437296825840464.756541987
798178.903365521840394.052960209798196.333925672840365.456704882
798230.455600857840315.760504325798252.525496402840285.355451921
#Sta/Elev= 30
 9841.82247.2051 9852.15246.30739863.417246.27519874.684246.71179888.692248.1874
9897.219248.07869908.486247.23729920.027 247.2839942.648245.33589954.098 243.852
9965.548240.83719972.511236.81719976.998233.40059993.042214.9548    9999209.8842
9999.906 209.309   10001 209.548 10011.6214.441810023.31 225.45910035.04233.3974
10047.17239.5673 10049.8241.3377 10059.3246.791710067.47248.938310071.43250.7359
10083.56261.750610102.51270.377810108.07271.990810120.43276.379510132.34279.5709
#Mann= 3 , 0 , 0
 9841.82    0.12       0 9841.82    0.12       010132.34    0.12       0
#XS Ineff= 2 , 0
       0                               0
Bank Sta=9841.82,10132.34
Exp/Cntr=0.3,0.1

Type RM Length L Ch R = 1 ,16341.78,23.327300,23.327300,23.327300
XS GIS Cut Line= 6
798119.904577664840545.968382341798154.360098837840482.525364897
798198.093353998840407.465911694798199.094910117840405.734760245
798216.698945948840377.246504805798272.246175931840299.018144929
#Sta/Elev= 30
9839.934240.48839841.036240.23319852.415240.40099863.795239.44839871.564239.1684
9875.174238.88379886.554237.17759909.313237.32829920.839237.85459933.264236.9848
9943.986235.84739953.128233.9998 9955.56233.22659967.133227.37329972.992222.1957
9978.707215.8936 9990.28202.65889992.855201.0903    9999198.749510001.86198.4196
10013.62202.709210025.37215.713110031.26220.362710037.24 224.66310048.83231.5909
10074.04242.9896 10086.3252.039210098.57 256.432 10123.1260.337610130.43262.0095
#Mann= 3 , 0 , 0
9839.934    0.12       09839.934    0.12       010130.43    0.12       0
#XS Ineff= 2 , 0
       0                               0
Bank Sta=9839.934,10130.43
Exp/Cntr=0.3,0.1

Type RM Length L Ch R = 1 ,16318.45,23.327300,23.327300,23.327300
XS GIS Cut Line= 6
798135.481507555840557.107698487798166.726917515840500.577143927
798212.819186228 840427.11484758798217.771384919840419.816700328
798218.903397924840418.167898776798292.829913771 840313.27877376
#Sta/Elev= 30
9838.865 237.5599852.699233.73149858.541233.2017 9875.55230.89819886.976229.0876
9910.039226.5688 9933.65225.81639937.837225.33689945.456223.25719957.261217.8073
9969.066209.25019975.468202.84519980.872196.6495 9990.18184.89679992.736181.3164
9994.064180.7253    9999 180.10210004.88  178.9710011.58181.321410017.11185.2883
10029.34201.600110041.58211.8978 10046.3 214.94410053.81219.139510066.05226.9491
10081.02233.316610098.37239.980310102.75241.931710114.98246.268910129.32249.9564
#Mann= 3 , 0 , 0
9838.865    0.12       09838.865    0.12       010129.32    0.12       0
#XS Ineff= 2 , 0
       0                               0
Bank Sta=9838.865,10129.32
Exp/Cntr=0.3,0.1

Type RM Length L Ch R = 1 ,16295.13,144.215000,144.215000,144.215000
XS GIS Cut Line= 6
798154.107285896840570.427295792798177.446026977 840528.56436663
798209.016801583840475.576620747798239.802457026840428.872616592
798249.550725347840414.717377217798311.606964652840326.287710973
#Sta/Elev= 30
9838.457232.9694 9856.12226.20369867.569222.42799879.018222.17099890.536220.1076
9902.176217.44559913.816216.67149920.682216.59659925.457216.18099937.097214.0935
9940.219212.80319948.757208.7595  9972.7198.48999977.139 195.3069984.671185.0915
9995.328172.68039996.643172.332410008.71171.547810020.85171.761910030.68181.5983
10045.28199.105110048.09200.8569 10057.5205.398310069.71210.002310081.93 215.432
10094.15222.376210100.31225.577410106.36228.446310118.58232.004510129.22237.1422
#Mann= 3 , 0 , 0
9838.457    0.12       09838.457    0.12       010129.22    0.12       0
#XS Ineff= 2 , 0
       0                               0
Bank Sta=9838.457,10129.22
Exp/Cntr=0.3,0.1

Type RM Length L Ch R = 1 ,16150.91,144.215100,144.215100,144.215100
XS GIS Cut Line= 6
 798284.80171644840665.636830617798320.438150572840610.242132977
798336.358310055840577.240923091 798377.80064717840448.996285689
798393.626841978840412.321746278798418.618761575840365.951148525
#Sta/Elev= 30
9817.479215.24789830.552210.83939835.018209.4297 9845.14206.5217  9854.6203.3832
9872.761198.92559877.868 197.7959889.223194.88649900.326192.75459916.917 189.286
9933.112  186.219943.788183.31039954.465180.67069964.973 178.6279977.178171.0452
9985.788166.67999996.195165.855110006.58 168.57610013.66169.414710027.42170.7001
10037.99171.526310046.23171.959410059.25 173.99910073.07175.655310081.04177.2732
10114.36182.175210125.63 184.54910134.65186.127210136.98186.329210147.54189.4988
#Mann= 3 , 0 , 0
9817.479    0.12       09817.479    0.12       010147.54    0.12       0
#XS Ineff= 2 , 0
       0                               0
Bank Sta=9817.479,10147.54
Exp/Cntr=0.3,0.1

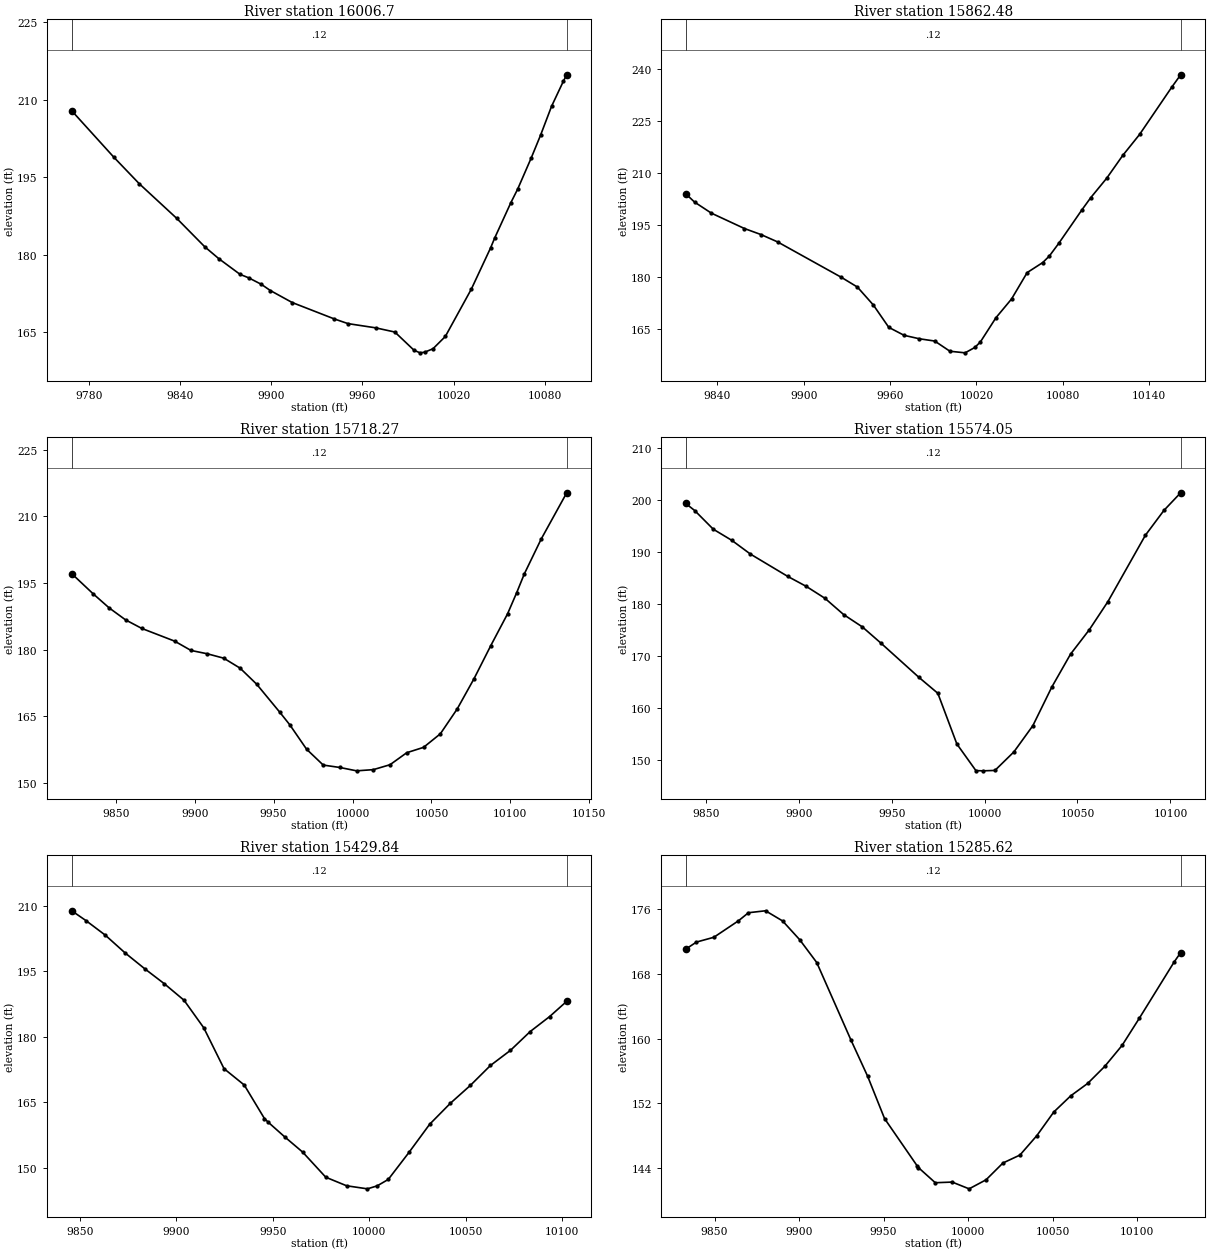
Type RM Length L Ch R = 1 , 16006.7,144.215000,144.215000,144.215000
XS GIS Cut Line= 6
798334.622248627840715.048997794798367.044568538840685.282119601
798444.072679946840610.701453667798475.236343508840577.592359429
798522.496835515840515.818477588798556.437101084840477.518375734
#Sta/Elev= 30
9768.822207.87639796.486198.88229813.242193.7303 9837.83187.03239856.371181.4919
9865.668 179.1769879.587 176.1489885.123175.49679893.507174.23179899.499173.0155
9913.875 170.6919941.617167.50449950.588166.60099968.792165.78359981.401164.9684
 9994.01161.43849997.968160.9351   10001161.0601 10006.5 161.729 10014.6164.1051
10031.73173.2958 10044.4181.290610047.08183.199110057.76190.076410062.16192.6557
10071.13198.731910077.24203.118510084.49208.733610092.32213.638410094.48214.8553
#Mann= 3 , 0 , 0
9768.822    0.12       09768.822    0.12       010094.48    0.12       0
#XS Ineff= 2 , 0
       0                               0
Bank Sta=9768.822,10094.48
Exp/Cntr=0.3,0.1

Type RM Length L Ch R = 1 ,15862.48,144.215000,144.215000,144.215000
XS GIS Cut Line= 6
798379.715149748840759.772284979798437.060707905840726.522015748
798496.720849985840697.989532541798564.078125751840674.075719179
 798608.36895093840655.413065739798690.534061224 840613.57316256
#Sta/Elev= 30
9817.877203.90369824.086201.49729835.737198.31799858.767193.87889870.282192.1371
9881.798190.02569926.225179.7934 9937.31177.00259948.395171.82729959.115165.3912
9969.758163.09359980.402 162.0969991.046161.444910001.63158.505210012.19158.0435
10018.93159.590910022.79161.168310033.64168.169910044.49173.570810055.34181.1766
 10066.2184.082210070.79185.966710077.24189.567410093.46 199.29310099.52202.7629
10110.67208.394310121.81214.9555 10133.5 220.99510155.76 234.55910162.08238.2058
#Mann= 3 , 0 , 0
9817.877    0.12       09817.877    0.12       010162.08    0.12       0
#XS Ineff= 2 , 0
       0                               0
Bank Sta=9817.877,10162.08
Exp/Cntr=0.3,0.1

Type RM Length L Ch R = 1 ,15718.27,144.215100,144.215100,144.215100
XS GIS Cut Line= 6
798452.101713711840850.912359413798559.807652839840821.538633145
798621.596667446840800.520135548 798623.49344309840799.885909913
798657.646815076840787.937373453798750.199727913840754.076184132
#Sta/Elev= 30
9822.094197.10169835.464192.62459845.829189.37889856.194186.68619866.559184.7435
 9887.29181.89019897.655179.7928 9908.02179.03629918.385 178.0499928.751175.8048
9939.218172.20529954.038165.81169960.344162.98629970.907157.52229981.469153.9455
9992.032153.4027 10002.6152.647210013.19152.916410023.78154.027510034.38156.7349
10045.01157.939510055.66160.991910066.31166.582110076.96173.389910087.61180.8695
10098.25188.045710103.94192.7344 10108.9197.072410119.55204.900410135.74215.3385
#Mann= 3 , 0 , 0
9822.094    0.12       09822.094    0.12       010135.74    0.12       0
#XS Ineff= 2 , 0
       0                               0
Bank Sta=9822.094,10135.74
Exp/Cntr=0.3,0.1

Type RM Length L Ch R = 1 ,15574.05,144.215000,144.215000,144.215000
XS GIS Cut Line= 6
798460.153666689840925.680494294798492.816436849840924.684482772
798540.927623942840927.612644094798582.602343828840933.727518775
798656.615073251840949.471344193798724.011142462840954.931970399
#Sta/Elev= 26
9839.163199.28259844.011197.92089854.016194.33019864.021192.18089874.028189.5442
9894.065185.26489904.084183.33439914.102181.05349924.157177.92599934.264175.5431
9944.371172.39329964.617165.87599974.856162.79429985.095153.05049995.334 147.934
    9999147.889810005.57147.967110015.77151.524510025.98156.567610036.18163.9917
10046.27170.322510056.33174.988910066.39 180.426 10086.5193.148210096.51197.9424
10105.52201.3311
#Mann= 3 , 0 , 0
9839.163    0.12       09839.163    0.12       010105.52    0.12       0
#XS Ineff= 2 , 0
       0                               0
Bank Sta=9839.163,10105.52
Exp/Cntr=0.3,0.1

Type RM Length L Ch R = 1 ,15429.84,144.215000,144.215000,144.215000
XS GIS Cut Line= 6
 798447.67349776841042.909270977798514.398757934841054.744235092
798563.904695997841070.352273097798634.403638919841098.716254287
798671.439807447841108.950704938798693.764323947841111.889460834
#Sta/Elev= 28
9845.753208.89989853.114206.6575 9863.16203.3154 9873.34199.28079883.561195.6369
9893.781 192.1839904.001188.40289914.238182.08269924.723172.73839935.208 168.994
9945.693161.30849947.715160.43939956.178157.11869965.515153.61929977.497147.8664
9988.296145.90819999.096145.206710004.17145.8916 10009.9147.359210020.65153.5496
10031.39160.008610042.13164.8165 10052.5168.910210062.88173.460210073.25176.9196
10083.53 181.24510093.61184.676510102.45188.1649
#Mann= 3 , 0 , 0
9845.753    0.12       09845.753    0.12       010102.45    0.12       0
#XS Ineff= 2 , 0
       0                               0
Bank Sta=9845.753,10102.45
Exp/Cntr=0.3,0.1

Type RM Length L Ch R = 1 ,15285.62,144.215100,144.215100,144.215100
XS GIS Cut Line= 6
798368.803717363841228.658853733798455.887913946841213.082482479
798504.451806038841211.391590302798579.862267753841215.716934507
798614.120150636841213.055241162798658.775784606841202.543393819
#Sta/Elev= 29
9832.866171.05079839.247171.93029849.545172.5226 9864.12174.56339870.026175.5605
9880.128175.8006 9890.23174.54219900.331172.22639910.433 169.4019930.549159.8777
9940.555155.33219950.561150.10279970.025144.20369970.574144.04369980.585142.1666
9990.597142.246610000.61141.410710010.63142.528810020.65144.609410030.67 145.587
10040.69147.991810050.72150.913510060.75152.915410070.78154.449810080.83156.5454
 10091.1  159.1410101.37162.522110121.92 169.462 10125.8170.6259
#Mann= 3 , 0 , 0
9832.866    0.12       09832.866    0.12       0 10125.8    0.12       0
#XS Ineff= 2 , 0
       0                               0
Bank Sta=9832.866,10125.8
Exp/Cntr=0.3,0.1