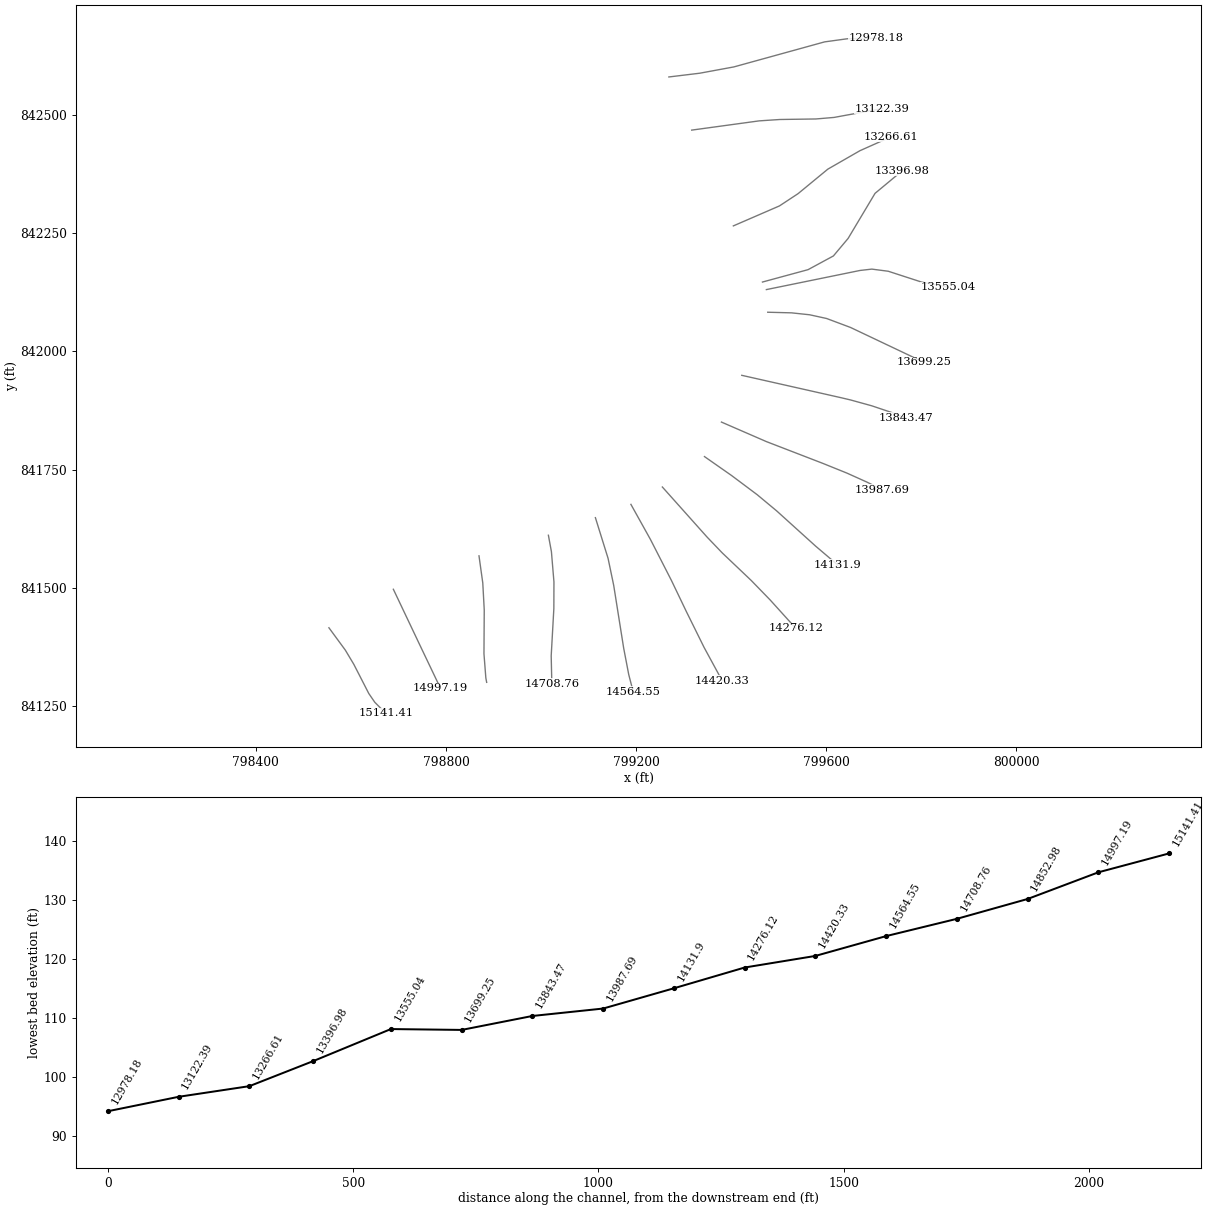
HEC-RAS study 18254_ras.prj: 18254

--- 18254_ras.g01 (geometry) --- (continued)

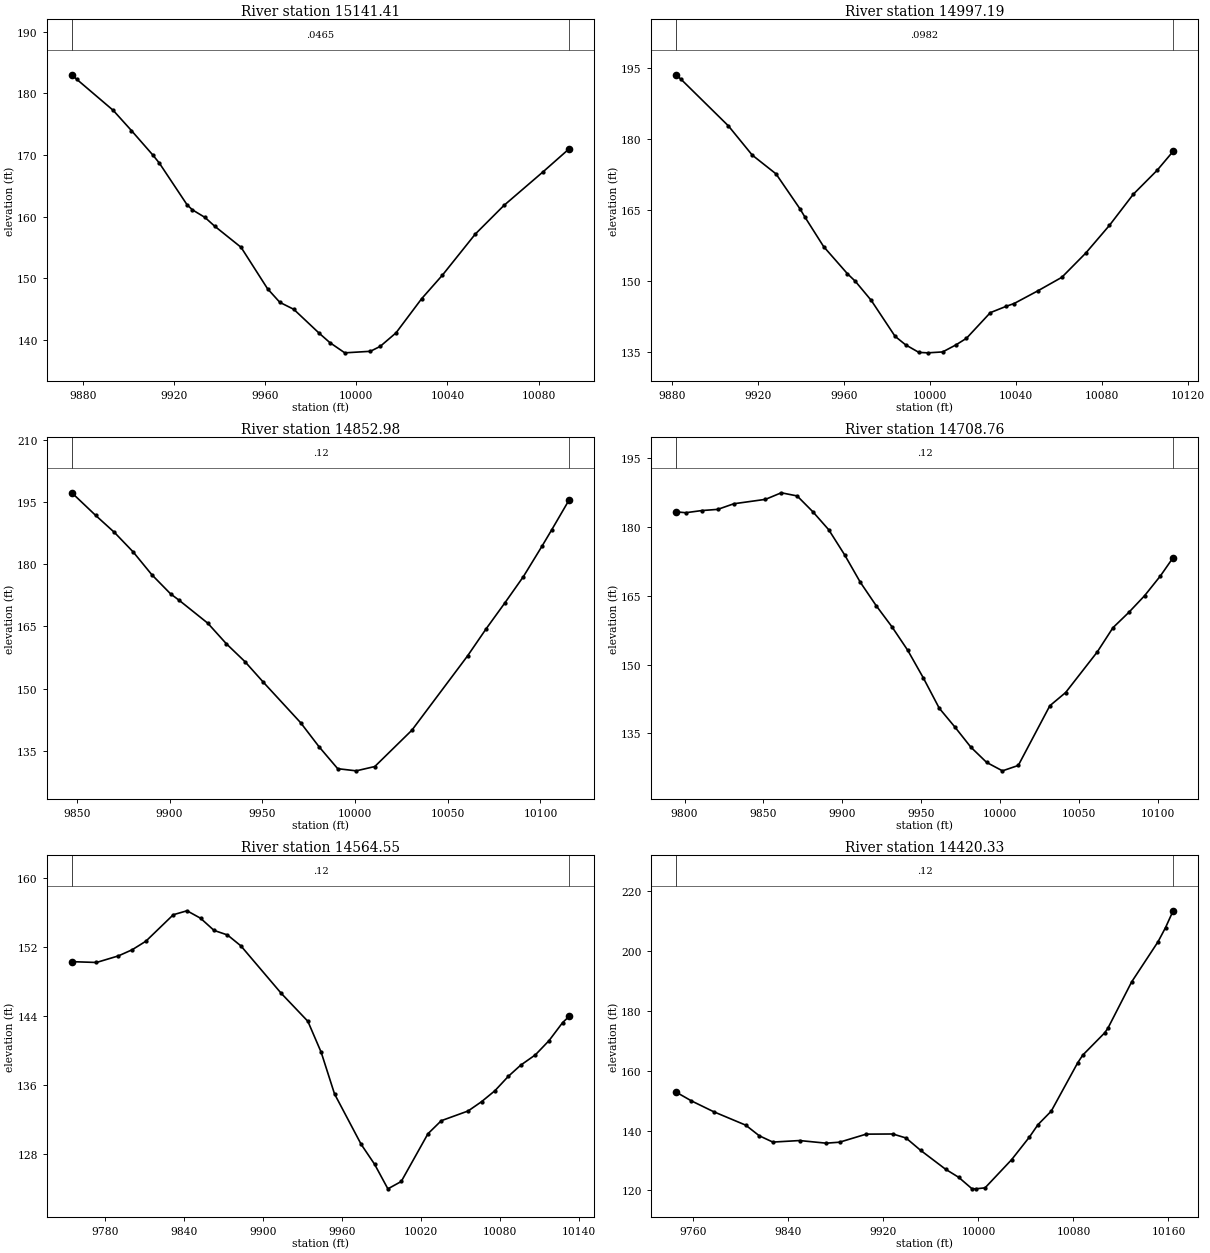
Type RM Length L Ch R = 1 ,15141.41,144.215000,144.215000,144.215000
XS GIS Cut Line= 6
 798553.71190767841415.746218372798588.174523311 841368.60579737
798606.209653127841338.345888529798637.581303688841276.925513789
798650.258561824841258.363880273798673.615019105841234.919905461
#Sta/Elev= 26
9875.218183.00359877.285182.29599893.393177.22779901.348 173.9689910.757169.9954
 9913.58168.70329925.812161.91169928.121161.10739933.634 159.8789937.831158.4785
9949.473155.03369961.114148.30499966.498146.10629972.604144.98069983.794141.0901
 9988.45139.57929994.984137.9242 10006.2138.172810010.51138.965810017.47141.1632
10028.73146.709710037.83150.518510052.27157.186110064.82161.819910082.14167.3175
10093.47 171.014
#Mann= 3 , 0 , 0
9875.218  0.0465       09875.218  0.0465       010093.47  0.0465       0
#XS Ineff= 2 , 0
       0                               0
Bank Sta=9875.218,10093.47
Exp/Cntr=0.3,0.1

Type RM Length L Ch R = 1 ,14997.19,144.215000,144.215000,144.215000
XS GIS Cut Line= 4
798689.319128995841497.110551161798739.420714393841391.227603667
798740.248879045841389.407124799798788.349924179841288.280549199
#Sta/Elev= 28
9881.862193.50889884.197192.60779906.323182.70199917.386176.53339928.449172.5582
9939.512165.21179941.904  163.419950.575157.18389961.638151.44339965.284149.8606
9972.701145.80889983.764138.21799988.664 136.4179994.827134.8164    9999134.7229
10005.88134.915510012.06136.403610016.95137.799910028.03143.218310035.34144.5478
 10039.1145.152210050.17147.845910061.25150.689410072.32155.7858 10083.4161.6815
10094.47168.249810105.54173.311310112.98177.3266
#Mann= 3 , 0 , 0
9881.862  0.0982       09881.862  0.0982       010112.98  0.0982       0
#XS Ineff= 2 , 0
       0                               0
Bank Sta=9881.862,10112.98
Exp/Cntr=0.3,0.1

Type RM Length L Ch R = 1 ,14852.98,144.215100,144.215100,144.215100
XS GIS Cut Line= 6
798869.567667293841567.727003141798877.545202422841510.311300953
798880.612574422841453.463657158798880.032060834841360.739645983
798883.988048494841309.737999711798885.714772014841300.468167121
#Sta/Elev= 24
9847.297197.22579860.177191.75569870.268187.66989880.359182.9708 9890.45177.4635
9900.542172.86249905.273171.27469920.607165.78819930.621160.83129940.636156.5302
9950.651151.52289970.668141.80939980.668135.97539990.668130.720610000.67130.2004
10010.67131.238410030.67 139.99210060.69157.901710070.72164.441110080.75170.6396
10090.78177.003610100.81 184.32710106.09188.301610115.52195.5426
#Mann= 3 , 0 , 0
9847.297    0.12       09847.297    0.12       010115.52    0.12       0
#XS Ineff= 2 , 0
       0                               0
Bank Sta=9847.297,10115.52
Exp/Cntr=0.3,0.1

Type RM Length L Ch R = 1 ,14708.76,144.215000,144.215000,144.215000
XS GIS Cut Line= 6
799015.649162467841611.212157051799022.014300414841576.461976266
799027.324550867841512.533942554799027.130875047 841456.46776488
799021.553313381  841356.5578392799022.860900955841296.891757889
#Sta/Elev= 30
9794.423 183.2789800.738183.07519810.905183.54519821.071183.80649831.218185.0272
9851.287185.98829861.321187.42039871.356186.7322 9881.39183.26529891.425179.3486
9901.433173.91679911.433167.91279921.433162.84219931.433158.23749941.433153.1209
9951.436147.03579961.453140.48039971.471136.33949981.488131.99239991.505128.6698
10001.52126.834810011.54128.005310031.56141.017610041.58143.899410061.59152.7254
10071.59158.030410081.59161.3453 10091.6 164.986 10101.6169.279810109.72173.2963
#Mann= 3 , 0 , 0
9794.423    0.12       09794.423    0.12       010109.72    0.12       0
#XS Ineff= 2 , 0
       0                               0
Bank Sta=9794.423,10109.72
Exp/Cntr=0.3,0.1

Type RM Length L Ch R = 1 ,14564.55,144.215000,144.215000,144.215000
XS GIS Cut Line= 6
799114.568494663841648.375221085799141.256424349841562.402257442
 799153.11265493841505.288335125799174.116405497841372.610613133
799184.764029707 841316.81978919799194.242965283841280.184124746
#Sta/Elev= 30
9755.023150.31589773.712 150.2219790.372 150.987 9800.78151.69789811.187152.6916
9832.002155.7704 9842.41156.22999852.673155.36389862.886153.9494  9873.1153.4189
9883.313152.14699913.858146.6404  9934.1143.38469944.221139.77839954.342 134.939
9974.584129.07069984.705126.77299994.826123.906210004.96124.760110025.22130.3096
10035.35131.8272 10055.7132.957110065.88134.035610076.06135.313810086.25 136.991
10095.52138.272110106.78139.486710117.11141.136210127.44143.238110132.42143.9599
#Mann= 3 , 0 , 0
9755.023    0.12       09755.023    0.12       010132.42    0.12       0
#XS Ineff= 2 , 0
       0                               0
Bank Sta=9755.023,10132.42
Exp/Cntr=0.3,0.1

Type RM Length L Ch R = 1 ,14420.33,144.215100,144.215100,144.215100
XS GIS Cut Line= 6
799189.321867339841676.459361099799230.351899641841602.522898853
799274.640099304841515.671402685799305.599903959841450.896957423
799343.221010049841374.519072695799381.220729848841304.345881731
#Sta/Elev= 30
9745.152152.87599758.382149.87949777.182146.25239804.052141.7915 9815.47138.2488
9826.887136.14189849.385136.65639871.835135.7779 9883.06136.1068 9905.51 138.794
9927.951138.84359939.035137.50759951.231133.41779972.285127.09839983.369124.3966
9994.452120.61089997.609120.544910005.59120.875610027.88 130.24910042.88137.7878
10050.17141.974910061.31146.4618 10083.6162.604710087.89165.179610106.31172.5882
   10109174.121410129.02189.5854 10151.2202.952210157.55207.705410163.95213.3097
#Mann= 3 , 0 , 0
9745.152    0.12       09745.152    0.12       010163.95    0.12       0
#XS Ineff= 2 , 0
       0                               0
Bank Sta=9745.152,10163.95
Exp/Cntr=0.3,0.1

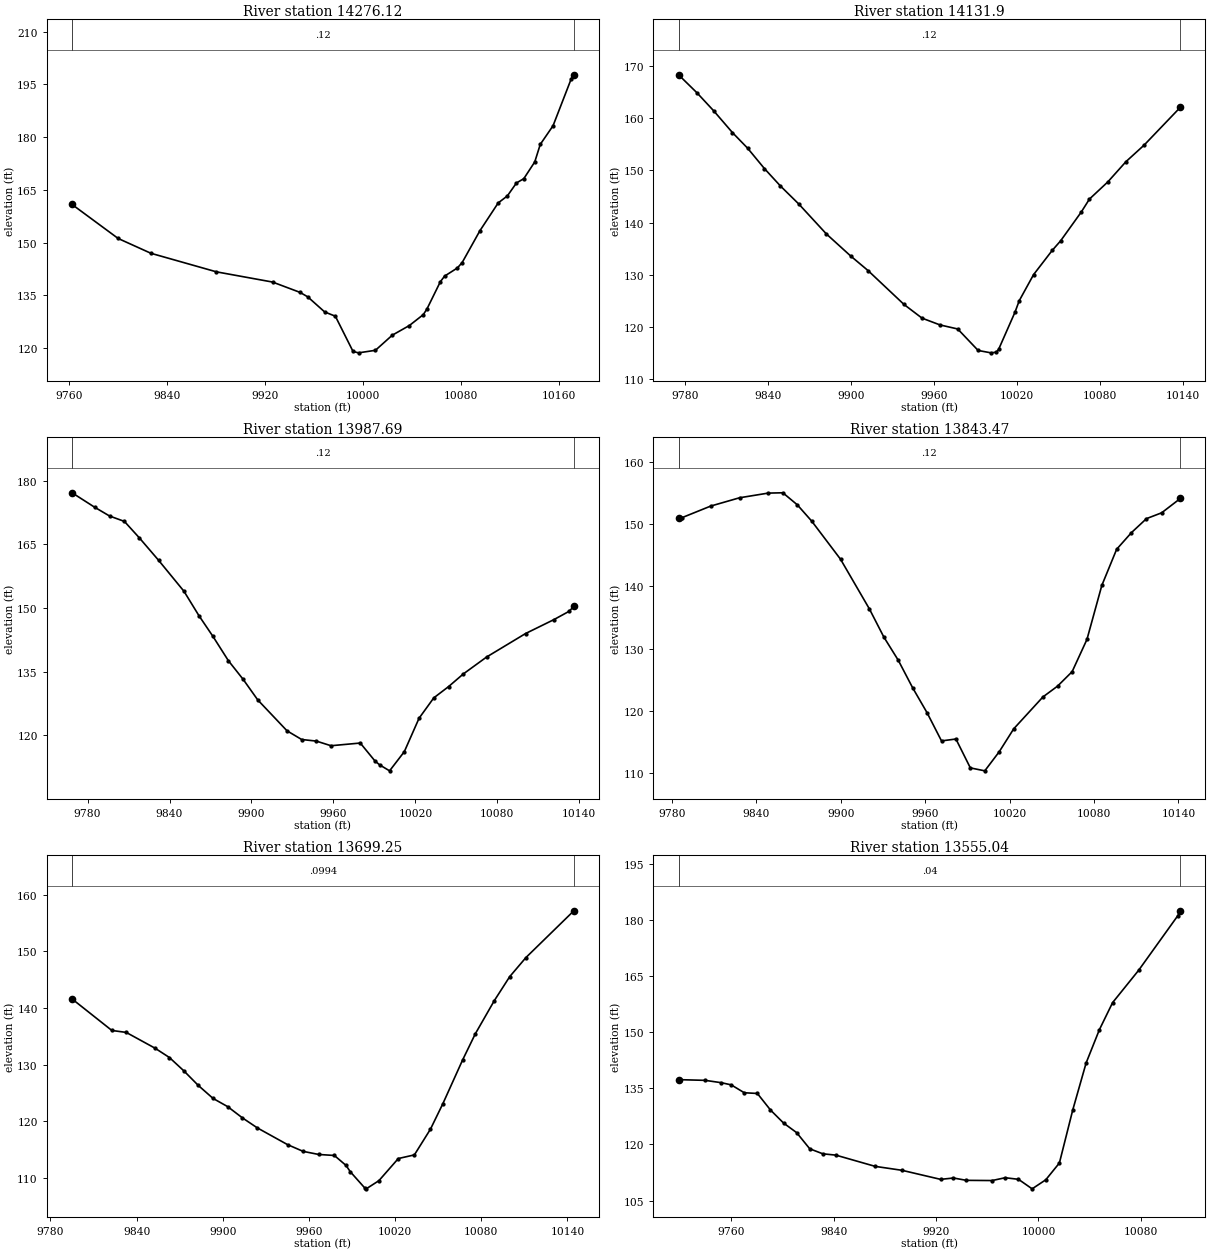
Type RM Length L Ch R = 1 ,14276.12,144.215000,144.215000,144.215000
XS GIS Cut Line= 6
799255.504248318841713.133567324 799349.41376343 841607.61657216
799381.516826457841573.950146594799442.640596437841515.626132133
799482.557418672841474.348466678799536.382952754841414.603312301
#Sta/Elev= 30
9762.193160.82869799.855151.14859826.629146.92989880.177141.64439926.033138.7375
9948.516135.79389954.788134.5261 9968.63130.22559977.374129.00889991.837118.9621
9996.313118.5784 10010.1119.298110023.91123.609810037.85 126.35510049.23129.4581
10052.23131.064910063.15138.809510066.62140.420210077.06142.7417   10081144.2856
10095.52153.359110110.46161.270910117.92163.2599 10125.4166.960110131.38168.1789
10140.34172.956610144.84 177.94710155.28183.244210170.22196.680710172.29197.7642
#Mann= 3 , 0 , 0
9762.193    0.12       09762.193    0.12       010172.29    0.12       0
#XS Ineff= 2 , 0
       0                               0
Bank Sta=9762.193,10172.29
Exp/Cntr=0.3,0.1

Type RM Length L Ch R = 1 , 14131.9,144.215000,144.215000,144.215000
XS GIS Cut Line= 6
799344.167994066841777.394962877799401.405489647841737.237097769
 799454.98714035841696.976056267799495.969372346841662.784401557
799578.201729237841588.147337531799624.897667833841548.297413203
#Sta/Elev= 30
9775.195168.30469788.427164.87899800.643 161.3949814.187 157.2299825.074154.2647
 9837.29150.34349848.839147.01459862.119143.55919882.132137.81139899.644133.6025
9912.137130.8257  9938.2124.32269951.223121.70289964.247120.40149977.012119.6299
9991.789115.5141   10001115.059410004.94115.179910006.59115.7272 10018.4122.8255
10021.52125.053310031.86130.036810045.33134.672310051.39136.498910066.33142.0191
10072.25144.5048 10085.5147.779710098.65151.669510111.79154.839410137.95162.0744
#Mann= 3 , 0 , 0
9775.195    0.12       09775.195    0.12       010137.95    0.12       0
#XS Ineff= 2 , 0
       0                               0
Bank Sta=9775.195,10137.95
Exp/Cntr=0.3,0.1

Type RM Length L Ch R = 1 ,13987.69,144.215100,144.215100,144.215100
XS GIS Cut Line= 6
799379.864740536841850.307466331 799474.42700782841809.068038174
  799593.0318637841763.147715859799643.990840406841742.506704397
799686.542932196841723.281684798799718.173220306 841707.45317547
#Sta/Elev= 30
9768.652177.14539785.164173.74399796.074171.67599806.984170.39469817.893166.5291
9831.961161.25289850.622153.91779861.531 148.1939871.816143.29579883.083 137.586
9893.877133.1952  9904.6128.33739926.047121.0525 9936.77119.00679947.494 118.636
9958.217117.54129979.664118.17519990.387113.9621 9993.87113.022910001.12111.6247
10011.91116.1441 10022.7 124.01710033.49128.821610044.28131.466510055.09134.4522
10072.21138.456310100.67143.975910121.31147.2389 10132.5149.202810136.04150.3924
#Mann= 3 , 0 , 0
9768.652    0.12       09768.652    0.12       010136.04    0.12       0
#XS Ineff= 2 , 0
       0                               0
Bank Sta=9768.652,10136.04
Exp/Cntr=0.3,0.1

Type RM Length L Ch R = 1 ,13843.47,144.215000,144.215000,144.215000
XS GIS Cut Line= 6
799422.672034411841949.056283502799631.695506967841901.762170478
799652.033757307841896.924719712799696.298258117841884.650204528
799740.798367086 841869.64978854 799767.26594527841858.822410778
#Sta/Elev= 30
9784.693 151.029 9787.08151.04889807.585152.92119828.091154.25369848.387155.0032
9858.849155.05579869.102153.12599879.355150.5028 9899.86144.37269920.366136.3908
9930.619131.87639940.871128.14769951.124123.70969961.377119.6991 9971.63115.1758
9981.882115.48129992.135110.838610002.39110.365510012.67113.437610022.98117.1234
10043.74122.244910054.12123.979110064.49126.304510075.02131.483710085.58140.1563
10096.13145.975110106.68148.656910117.34150.901510128.14151.8384 10141.4154.1403
#Mann= 3 , 0 , 0
9784.693    0.12       09784.693    0.12       0 10141.4    0.12       0
#XS Ineff= 2 , 0
       0                               0
Bank Sta=9784.693,10141.4
Exp/Cntr=0.3,0.1

Type RM Length L Ch R = 1 ,13699.25,144.215000,144.215000,144.215000
XS GIS Cut Line= 6
799477.308753285 842082.33676435799527.366725358842081.039797615
799565.409989701842076.975903375799601.188663278842069.118797827
 799651.50703072842050.195487652 799805.53559489841976.820497109
#Sta/Elev= 30
9795.073141.60059822.773136.02629832.777135.68129852.824132.89279862.881131.2347
9872.938128.87249882.995126.29039893.226124.00459903.464122.54119913.702120.5577
9924.052118.78959945.112115.82499955.949114.63319966.786114.08389977.711113.9059
9985.852112.14399988.802111.0313    9999108.12479999.885108.001210008.75109.4489
10022.25113.363110033.44114.008310044.64118.563310053.28 123.07110067.02130.8033
10075.88135.4379 10089.1141.303610099.83 145.55110111.11148.925610144.49 157.203
#Mann= 3 , 0 , 0
9795.073  0.0994       09795.073  0.0994       010144.49  0.0994       0
#XS Ineff= 2 , 0
       0                               0
Bank Sta=9795.073,10144.49
Exp/Cntr=0.3,0.1

Type RM Length L Ch R = 1 ,13555.04,158.064500,158.064500,158.064500
XS GIS Cut Line= 6
 799474.46760176842130.161068979799671.539764191842170.576146265
799696.391956292842173.435385722799730.959119031842168.924731921
799801.311227809842145.990996161799856.946806087842135.338398303
#Sta/Elev= 30
9718.877137.3084 9739.67137.11979752.251136.4934    9760135.91769770.226133.8084
9780.453133.6179 9790.68129.20459800.906125.71979811.133123.1552 9821.36118.8412
9831.587117.50069841.813117.14499872.494114.14539893.459113.09439923.572110.6766
9933.637111.03969943.703110.41619963.763110.36079973.999111.11299984.402110.6873
 9995.05108.146810005.71110.562310016.35115.050210026.85129.299810037.23141.7716
 10047.6150.661110057.91 157.88310078.27166.522310108.82181.0869 10110.8182.4051
#Mann= 3 , 0 , 0
9718.877    0.04       09718.877    0.04       0 10110.8    0.04       0
#XS Ineff= 2 , 0
       0                               0
Bank Sta=9718.877,10110.8
Exp/Cntr=0.3,0.1

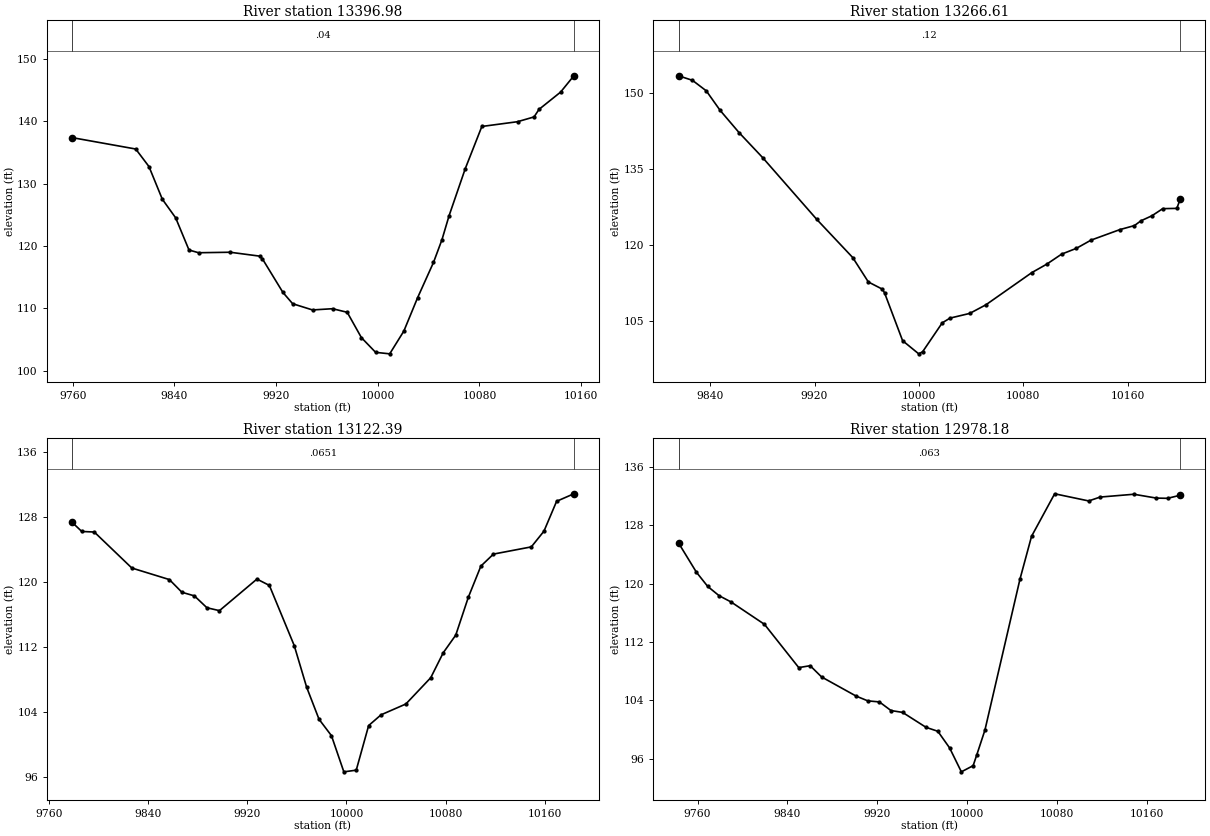
Type RM Length L Ch R = 1 ,13396.98,130.365600,130.365600,130.365600
XS GIS Cut Line= 6
799466.223228299842146.126363612799562.183708908842172.277068849
799615.514694835842201.229636281799646.475623701842238.234455045
799703.153377594842333.454318605 799760.34334789842381.115645493
#Sta/Elev= 30
 9759.49137.41049809.574135.57959819.986132.76679830.486127.52769840.987124.5431
9851.488119.37919859.032118.94349883.892119.02019907.013118.39919909.242117.9632
9925.409112.56679933.048110.76139948.655109.76579964.428109.96269975.962109.3888
9987.136105.3222 9998.31102.9645 10009.4102.724110020.51106.369910031.37111.7419
10043.84117.384510050.53 121.04310056.07124.860410068.85132.437910081.89139.1979
10109.94139.960610122.96140.727410126.85141.935110143.84144.708810154.28147.3279
#Mann= 3 , 0 , 0
 9759.49    0.04       0 9759.49    0.04       010154.28    0.04       0
#XS Ineff= 2 , 0
       0                               0
Bank Sta=9759.49,10154.28
Exp/Cntr=0.3,0.1

Type RM Length L Ch R = 1 ,13266.61,144.215000,144.215000,144.215000
XS GIS Cut Line= 6
799404.969007466842264.745648362799501.989222257842306.939670858
799541.222421305842332.881758398799603.857346315842384.642492302
799671.521033066842423.650065083799737.489586783842453.163095809
#Sta/Elev= 30
9815.698153.48469826.347152.58679836.964 150.507 9847.58146.64449862.146142.2301
9880.342137.25269921.687125.07069949.273117.51739961.261 112.6849972.006111.2607
9973.664110.54049987.511101.07179999.86498.4676810002.8798.8842510017.91104.5993
10023.87105.537110038.96106.464810051.37108.165610086.66114.551110098.05116.2122
10109.41118.189410120.76119.343510132.02120.968210154.19123.055210165.28123.8428
10170.26124.787110178.71125.788110186.99127.194310197.78127.247810200.47129.1325
#Mann= 3 , 0 , 0
9815.698    0.12       09815.698    0.12       010200.47    0.12       0
#XS Ineff= 2 , 0
       0                               0
Bank Sta=9815.698,10200.47
Exp/Cntr=0.3,0.1

Type RM Length L Ch R = 1 ,13122.39,144.215100,144.215100,144.215100
XS GIS Cut Line= 6
 799317.25094034842467.068141831799459.346407241842486.593190506
799502.588401073842489.484162686799578.592421458842490.602565688
799616.892888734842493.862491547799718.638058194842512.593338517
#Sta/Elev= 30
 9778.74127.32659786.562126.19839796.656126.13089826.938121.7069 9857.22120.2873
9867.314118.72899877.408118.28359887.502116.82519897.596116.46889927.837120.3485
9937.859119.57119957.904112.18219967.921107.06329977.922103.12089987.923101.1105
9997.92496.6633410007.9296.8680210017.93102.351210027.93103.669410047.95105.0003
10068.02108.231710078.06111.289410088.18113.464810098.31118.109810108.44121.9425
10118.57123.418210149.12124.304910159.32 126.23710169.52129.906610183.43  130.83
#Mann= 3 , 0 , 0
 9778.74  0.0651       0 9778.74  0.0651       010183.43  0.0651       0
#XS Ineff= 2 , 0
       0                               0
Bank Sta=9778.74,10183.43
Exp/Cntr=0.3,0.1

Type RM Length L Ch R = 1 ,12978.18,144.215000,144.215000,144.215000
XS GIS Cut Line= 6
799269.198351672842579.344863435799334.270567944842587.274708025
799405.973588907842600.558073809799597.067730659842653.466476934
799644.808430266842660.032905495799706.315763142842660.945130346
#Sta/Elev= 30
9743.114125.57269759.032121.56339769.106119.6147 9779.18118.35239789.863117.4895
9819.579114.4276 9850.09108.4978 9860.26108.7569 9870.43107.2157 9901.22104.5893
9911.538103.94089921.855 103.7969932.172102.61379942.489102.36129963.388100.3122
9973.85999.773399984.33197.499389994.80294.2161810005.29 95.061210008.4196.48753
10015.7699.9235410046.98120.626310057.27126.485310077.83132.312510108.15131.3305
10118.25131.861910148.34 132.24810168.35131.721110178.35131.690810189.67 132.119
#Mann= 3 , 0 , 0
9743.114   0.063       09743.114   0.063       010189.67   0.063       0
#XS Ineff= 2 , 0
       0                               0
Bank Sta=9743.114,10189.67
Exp/Cntr=0.3,0.1