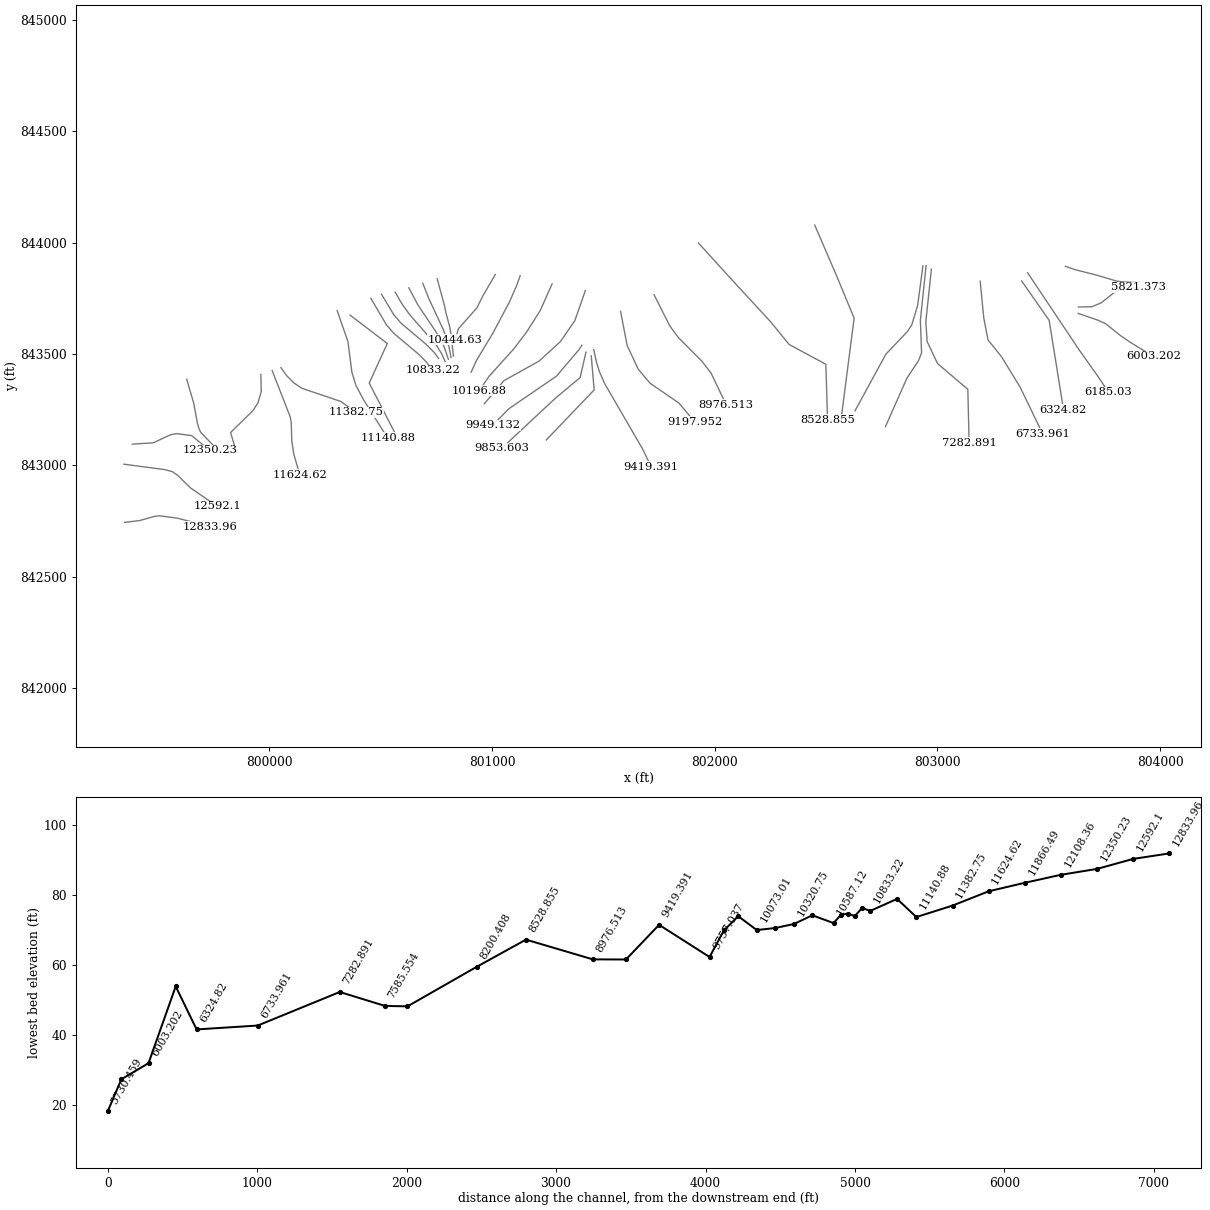
HEC-RAS study 18254_ras.prj: 18254

--- 18254_ras.g01 (geometry) --- (continued)

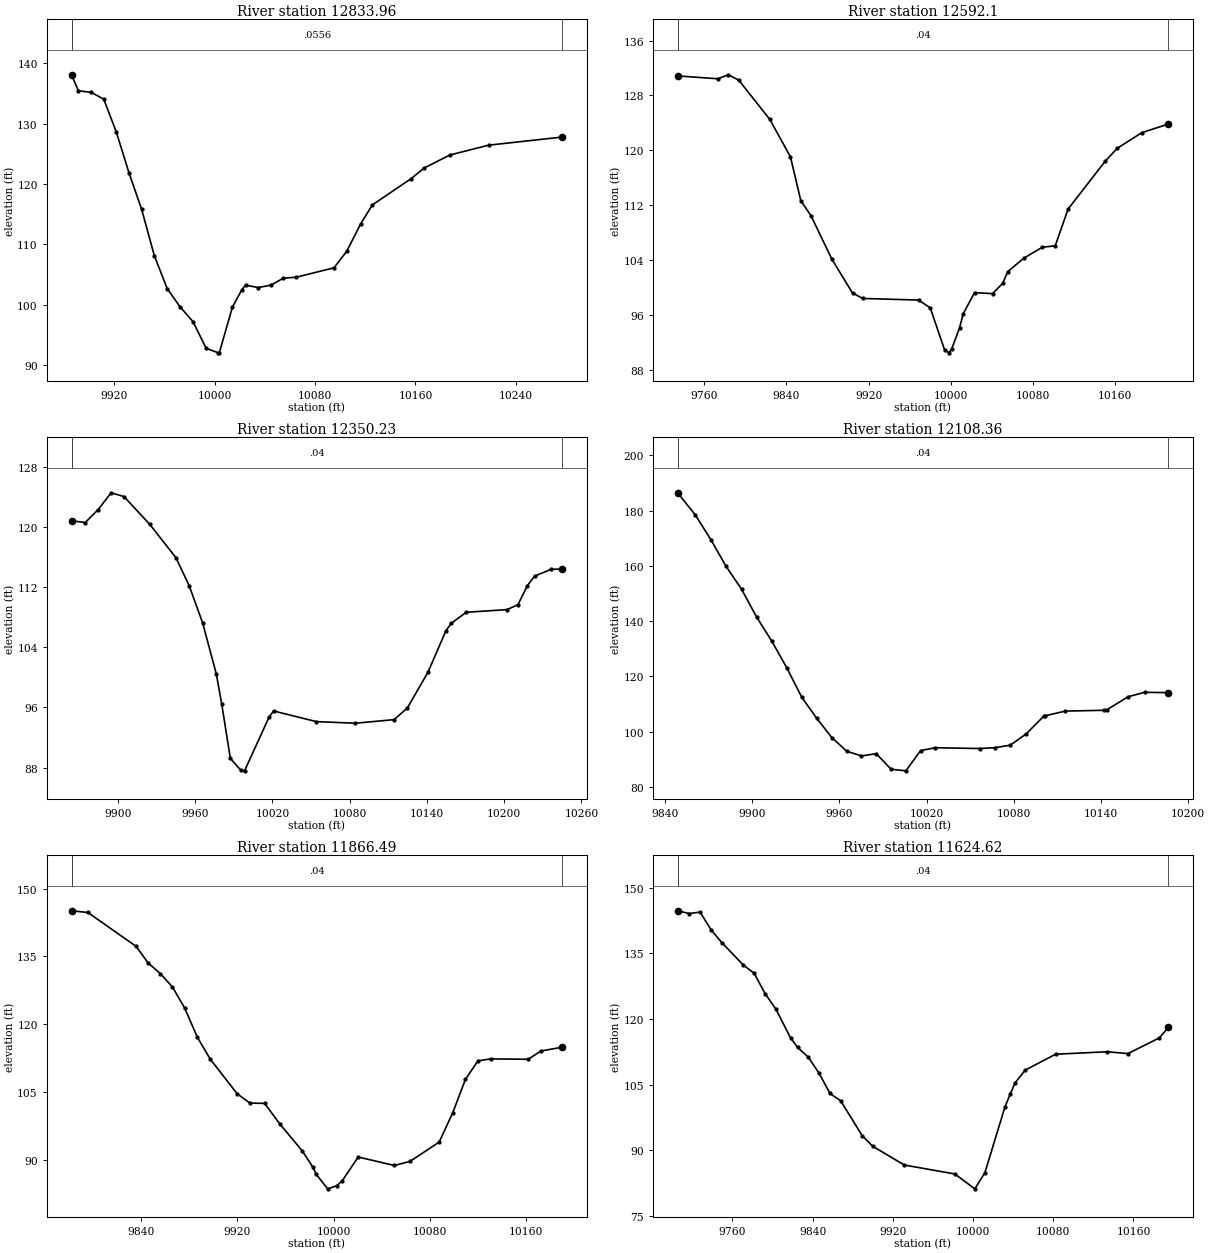
Type RM Length L Ch R = 1 ,12833.96,241.869000,241.869000,241.869000
XS GIS Cut Line= 6
799349.506280201842744.157050176799417.121221688842752.183725513
799482.181636824842770.639882313799505.694107483 842773.88577972
799587.389224394842762.895349881799731.394936244842725.210511444
#Sta/Elev= 30
9886.013138.08299891.514135.43319901.585135.17369911.664134.05269921.744128.5721
9931.823121.82149941.903115.76259951.982 108.1099962.218102.64749972.49599.62573
9982.819 97.16379993.30992.7382910003.0192.0004710003.7892.0369210014.2699.61943
10021.79102.479210024.63103.214910034.73102.823510044.82103.213710054.85104.3828
10064.87104.524210095.16106.093310105.32108.8561 10116.4113.389310125.66116.5192
10156.51120.8603 10166.8122.612210187.39124.787110218.39126.419610276.96127.7613
#Mann= 3 , 0 , 0
9886.013  0.0556       09886.013  0.0556       010276.96  0.0556       0
#XS Ineff= 2 , 0
       0                               0
Bank Sta=9886.013,10276.96
Exp/Cntr=0.3,0.1

Type RM Length L Ch R = 1 , 12592.1,241.868900,241.868900,241.868900
XS GIS Cut Line= 6
799346.360584392843005.414999257799530.657557588842980.939123927
799563.745069713842971.951915256799586.450229999842956.820532908
799645.698215399842898.752966082799766.732948773842815.764168584
#Sta/Elev= 30
9734.103130.85519773.329130.44019783.468131.02259793.592130.24529823.791124.5206
9843.924119.0451 9853.99112.65899864.057110.40829884.189104.11999904.322 99.1658
9914.38998.374219968.60598.138439979.97597.001099994.02190.833449998.39390.43573
   1000191.0597710008.5294.0909610012.13 96.165810023.0699.22439 10040.699.07786
10050.42100.575710055.52102.291410071.05104.256510089.06105.849110101.61106.0596
10114.16111.426810150.35118.425410162.21120.317710185.93122.576510211.71123.8303
#Mann= 3 , 0 , 0
9734.103    0.04       09734.103    0.04       010211.71    0.04       0
#XS Ineff= 2 , 0
       0                               0
Bank Sta=9734.103,10211.71
Exp/Cntr=0.3,0.1

Type RM Length L Ch R = 1 ,12350.23,241.869000,241.869000,241.869000
XS GIS Cut Line= 6
799384.327231437843095.450190753799478.539645165843101.421071246
799556.842976779843138.087561399799583.503370643843142.779371932
799650.910781384843133.821112037799731.674990714843067.832521304
#Sta/Elev= 30
9863.918120.81039874.619120.58089884.646122.30439894.666124.53239904.668124.0295
9924.742120.32269945.021115.90439955.297112.18799965.792 107.2199976.406100.4305
9980.53596.512259987.28389.234689995.45987.629689998.32987.5668510017.3194.69273
10020.8995.5266810053.9894.1142510084.2693.8968510114.47 94.373910124.6495.89362
 10140.8 100.67710154.75106.1922   10159107.198310170.55108.646210202.16109.0001
10210.65109.644710217.97112.171610223.57 113.44910236.48114.3615 10245.1114.3932
#Mann= 3 , 0 , 0
9863.918    0.04       09863.918    0.04       0 10245.1    0.04       0
#XS Ineff= 2 , 0
       0                               0
Bank Sta=9863.918,10245.1
Exp/Cntr=0.3,0.1

Type RM Length L Ch R = 1 ,12108.36,241.868900,241.868900,241.868900
XS GIS Cut Line= 6
799628.573243737843386.589483246799660.144121915843279.312124416
799677.217334867843186.669983789799684.587596327843162.764680386
799691.754909217843147.821459249799754.175638199843083.301716477
#Sta/Elev= 30
 9848.82186.42629861.065178.37139871.631169.53199882.197 159.7799892.762151.5847
9903.184141.46949913.517132.84859923.849123.18569934.181112.50519944.513104.8567
9954.84597.934449965.10892.978449975.27991.27961 9985.4592.091139995.62186.45862
10005.7885.8849510015.9593.2217810026.1294.2425610056.67 93.951810067.1494.26103
 10077.695.1672310088.5599.2647410100.44105.547710101.18105.752410115.56107.4997
10142.18107.774410144.33108.064110158.71112.696710170.01114.284710186.29114.1597
#Mann= 3 , 0 , 0
 9848.82    0.04       0 9848.82    0.04       010186.29    0.04       0
#XS Ineff= 2 , 0
       0                               0
Bank Sta=9848.82,10186.29
Exp/Cntr=0.3,0.1

Type RM Length L Ch R = 1 ,11866.49,241.869000,241.869000,241.869000
XS GIS Cut Line= 6
799961.499503404843408.437906533799963.359466285843331.695274457
799948.682045639843281.026113793799925.842733473 843245.59705165
799825.467928737843147.444627821799852.615971088843057.988488033
#Sta/Elev= 30
9782.262145.0954 9795.85144.71729835.936137.22249845.966133.54569855.995131.2105
9866.144128.22599876.354123.53869886.693117.18489897.333112.34979919.842104.6314
9930.489102.56149942.688102.4988 9955.6597.832699973.86192.029129982.67888.42802
  9985.586.837869995.10283.5937110002.6484.2879710007.2585.3970610020.42 90.6286
10050.4988.7628110063.4889.66547 10087.793.9318610099.04100.455310109.49107.7876
10119.94111.906310130.39 112.33610161.74112.255110172.19114.076310189.97114.9251
#Mann= 3 , 0 , 0
9782.262    0.04       09782.262    0.04       010189.97    0.04       0
#XS Ineff= 2 , 0
       0                               0
Bank Sta=9782.262,10189.97
Exp/Cntr=0.3,0.1

Type RM Length L Ch R = 1 ,11624.62,241.868900,241.868900,241.868900
XS GIS Cut Line= 6
800012.439239387843425.738194216800092.974736001843219.038480311
800098.002597851843192.307624688 800100.50152641843109.763694681
800109.755890693843049.563999549800136.812427548842956.621396713
#Sta/Elev= 30
9705.326144.71369716.924144.08269727.725144.41389738.526140.42879749.328137.4548
 9770.93132.30429781.731130.42759792.532125.79999803.334122.24779817.934115.6855
9824.936113.50089835.737111.24819846.538107.5487 9857.34102.95619868.048101.2661
9889.42693.316819899.974 90.89129931.37786.609229981.79184.56663 10001.881.16366
10011.8184.8432810031.8199.8560910037.05102.808810041.87105.363510051.99  108.29
10082.34111.930210133.77112.491910154.49112.076910185.92115.673910194.81118.0777
#Mann= 3 , 0 , 0
9705.326    0.04       09705.326    0.04       010194.81    0.04       0
#XS Ineff= 2 , 0
       0                               0
Bank Sta=9705.326,10194.81
Exp/Cntr=0.3,0.1

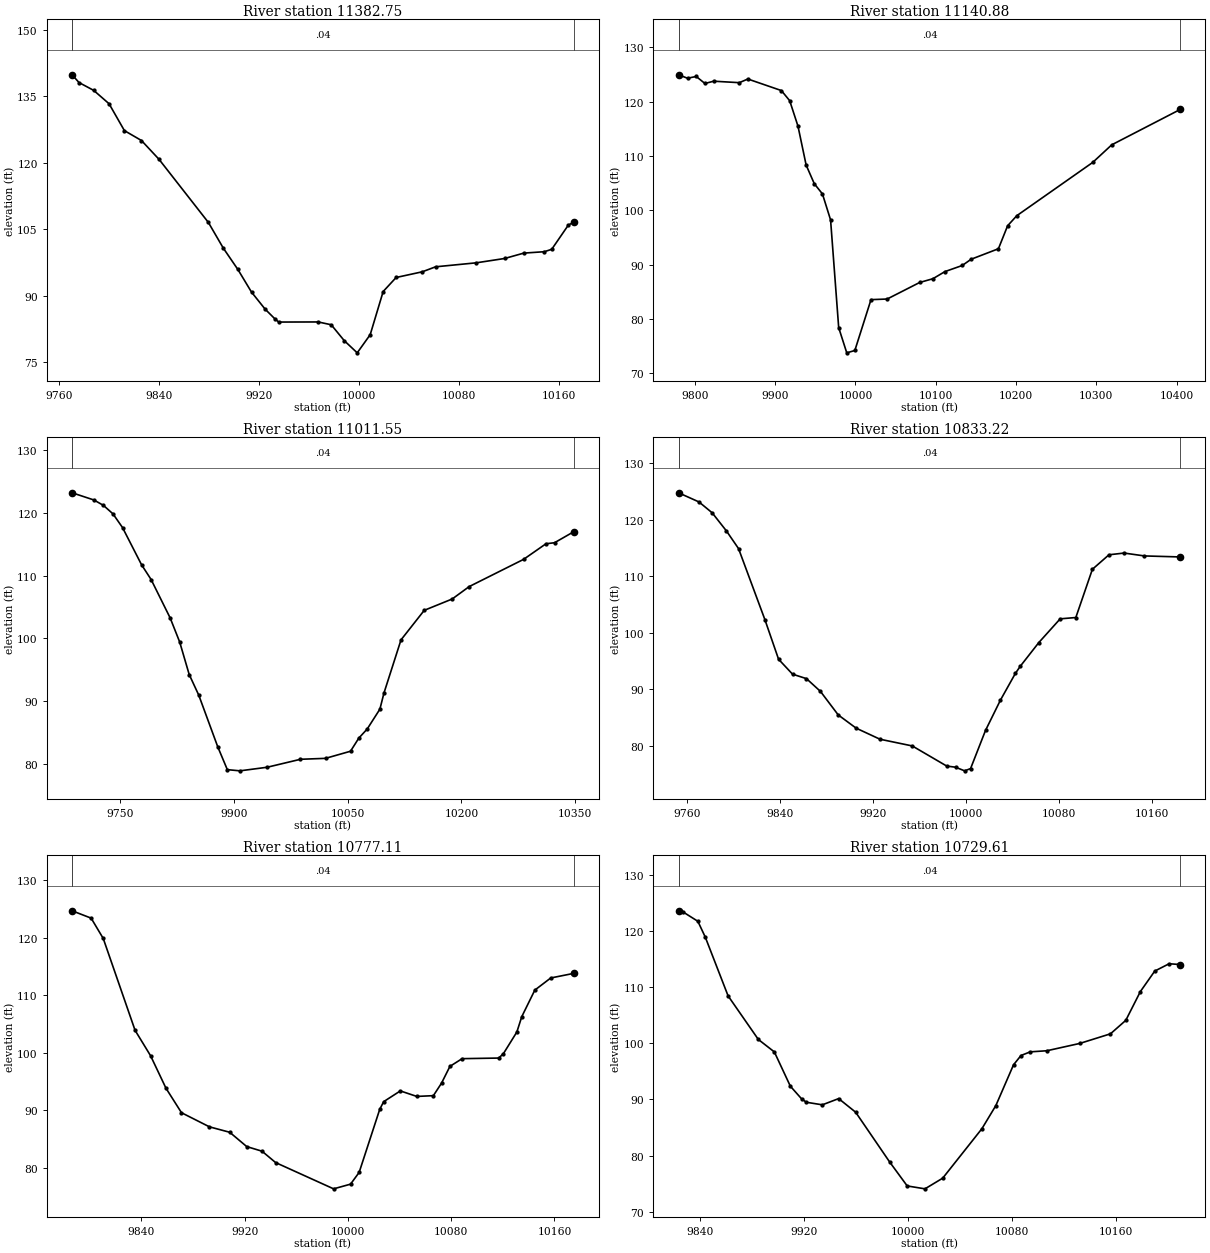
Type RM Length L Ch R = 1 ,11382.75,241.869000,241.869000,241.869000
XS GIS Cut Line= 6
  800051.7691143843439.095510223800077.629923402843402.856343447
800108.835788933843371.257598573800145.479625458843346.407057345
800319.830406164843287.481965147800388.285462988843239.313672511
#Sta/Elev= 30
9770.233139.79559775.795 138.0439787.549136.27589799.834133.2632 9812.12127.2001
9825.795124.96419839.849120.72059879.356106.48089891.284100.69319902.93995.88327
9913.865 90.77359924.75486.929689932.31584.811589935.64484.013879967.27884.03699
9977.68383.403079988.08879.825899998.49277.0692910008.8881.1645610019.2690.90214
10029.6394.0657810050.5495.3490210061.25 96.477710093.7397.3743110116.5798.35885
10131.8499.5689910148.2199.8806810154.19100.425810167.53105.902610171.91 106.541
#Mann= 3 , 0 , 0
9770.233    0.04       09770.233    0.04       010171.91    0.04       0
#XS Ineff= 2 , 0
       0                               0
Bank Sta=9770.233,10171.91
Exp/Cntr=0.3,0.1

Type RM Length L Ch R = 1 ,11140.88,129.328000,129.328000,129.328000
XS GIS Cut Line= 6
800304.230225772843695.297967166800352.616159558843556.534247354
800370.396248609843418.457018703800388.595004737843359.418311059
800423.714726925843293.014344484800531.148782203843122.774983737
#Sta/Elev= 30
9779.782124.94519790.954124.31149801.803124.63259812.651123.3441  9823.5123.7637
9855.466123.49359866.088124.1652 9907.82122.04299918.184120.18029928.514115.4937
9938.661108.34179948.808 104.9099958.956103.03269969.10398.247759979.20378.42993
9989.255 73.79559999.30774.2269110019.42 83.579310039.54  83.69510080.0986.74231
10096.5187.42863 10111.588.7417610133.02 89.862310144.0991.0104810178.0992.94265
10189.55  97.17310201.0199.0276710295.54108.827410319.19112.059210404.59118.5779
#Mann= 3 , 0 , 0
9779.782    0.04       09779.782    0.04       010404.59    0.04       0
#XS Ineff= 2 , 0
       0                               0
Bank Sta=9779.782,10404.59
Exp/Cntr=0.3,0.1

Type RM Length L Ch R = 1 ,11011.55,178.334400,178.334400,178.334400
XS GIS Cut Line= 4
800362.059869143843675.093279942800529.543752435843547.584973722
800448.214130106843369.762579098800565.383924994843142.315330177
#Sta/Elev= 30
9686.335123.13849715.167121.99379727.735121.13389740.303119.78969752.871 117.617
9778.008111.70439790.576109.36589815.712103.26649828.281 99.44239840.849 94.2738
9853.41791.010959878.55482.782359891.12279.174289907.757 78.9837 9943.6679.55342
9987.645 80.819110020.6380.9669510053.6282.0963310064.62 84.189910075.62 85.6246
10092.37 88.778910097.7391.3377310120.23 99.783610150.86  104.4710187.72106.2706
10210.22108.247310281.88112.563910311.46115.044610322.71115.205110348.22116.9641
#Mann= 3 , 0 , 0
9686.335    0.04       09686.335    0.04       010348.22    0.04       0
#XS Ineff= 2 , 0
       0                               0
Bank Sta=9686.335,10348.22
Exp/Cntr=0.3,0.1

Type RM Length L Ch R = 1 ,10833.22,56.113400,56.113400,56.113400
XS GIS Cut Line= 6
800455.611683271843750.514974214800524.854546564  843632.4369119
800558.187375327843593.533098802800670.615442963 843498.99160539
800707.816336129843461.252477961800733.026746543843426.327616486
#Sta/Elev= 30
9752.841124.72689770.424123.10599781.757121.18429794.043117.96979804.424114.8539
 9827.09102.28249838.82795.28884 9850.8292.653389862.81491.858599874.807 89.6081
9890.09885.443769905.46883.108429926.00581.14678 9953.7579.960139983.38576.39895
9990.89476.203659998.72675.5577110003.86 75.9622 10016.782.7104510029.5388.06813
10042.3692.7890610046.5694.0498310062.52 98.243610080.86102.434810094.31102.6686
10108.55   111.2 10122.8113.763410135.79114.068110153.33113.558810184.13113.3803
#Mann= 3 , 0 , 0
9752.841    0.04       09752.841    0.04       010184.13    0.04       0
#XS Ineff= 2 , 0
       0                               0
Bank Sta=9752.841,10184.13
Exp/Cntr=0.3,0.1

Type RM Length L Ch R = 1 ,10777.11,47.496700,47.496700,47.496700
XS GIS Cut Line= 6
800503.632860265843768.030895335800558.491699342843676.924759122
800591.824528105843638.020946024800704.252595741843543.479452612
800741.453488907843505.740325183800759.694259539843480.470748962
#Sta/Elev= 30
9786.247124.65049801.015123.37229810.403119.84259835.054 103.9019847.04899.49855
9859.04193.834359871.03589.594219892.71387.142319908.41686.200199921.585 83.7163
9933.455 82.91219943.94480.943259988.901 76.380710002.0277.1941610008.6979.23418
10024.64 90.1817 10027.791.51573 10040.693.3802810053.3692.42252 10066.292.55506
10072.5294.7257710079.0397.6412910088.4798.9775510116.8599.0843810120.4699.84319
10130.89103.6066 10134.7106.270410144.81110.878810157.14112.984410175.06 113.789
#Mann= 3 , 0 , 0
9786.247    0.04       09786.247    0.04       010175.06    0.04       0
#XS Ineff= 2 , 0
       0                               0
Bank Sta=9786.247,10175.06
Exp/Cntr=0.3,0.1

Type RM Length L Ch R = 1 ,10729.61,47.496800,47.496800,47.496800
XS GIS Cut Line= 6
800564.657730732843777.841045941800595.794698939843724.900429321
800628.965705195843678.419964909800750.873274949843538.173845496
800773.080606379 843502.43744951800789.127815219843467.054650554
#Sta/Elev= 30
9823.724123.64269826.946123.46849838.563121.76799844.288 118.9349861.797108.4634
9885.032100.6948 9897.3198.476459909.59692.368349918.20990.117559921.88189.50208
9934.16689.043919946.70890.153479959.74187.729569985.80778.871489999.34974.58065
   1001374.0640510026.6175.9673510056.7484.7932610067.4588.92054   1008196.17746
10086.7597.8383610093.8198.4881110106.6298.68685 10131.999.9917710155.45101.7029
10167.22104.104710178.44109.244510189.47112.8934 10200.5114.194910209.11114.0604
#Mann= 3 , 0 , 0
9823.724    0.04       09823.724    0.04       010209.11    0.04       0
#XS Ineff= 2 , 0
       0                               0
Bank Sta=9823.724,10209.11
Exp/Cntr=0.3,0.1

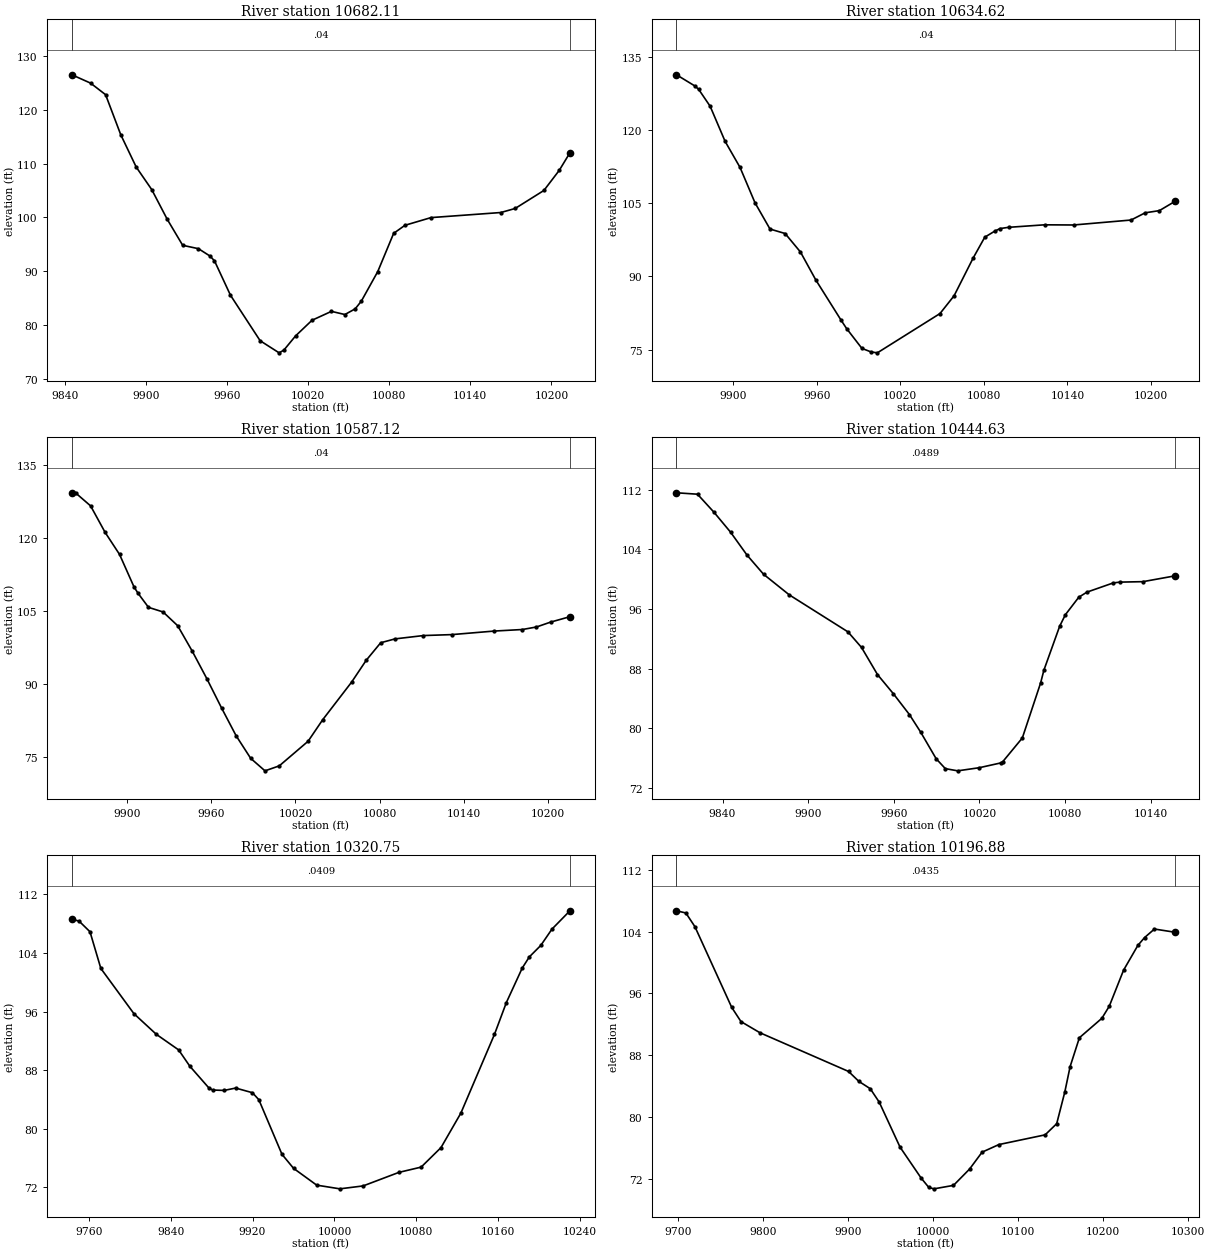
Type RM Length L Ch R = 1 ,10682.11,47.496700,47.496700,47.496700
XS GIS Cut Line= 6
 800626.22475448843797.446187583800667.071929104843720.314185763
800745.186163949843603.979927061 800767.95376412843566.537453425
800784.864161736843532.217672725800803.852758966843476.605965416
#Sta/Elev= 30
9845.324126.52019859.151124.96719870.261122.81439881.453115.37619892.908109.3482
9904.363105.17049915.81899.643389927.27394.793479938.936  94.1659947.42692.80345
9950.78391.90933 9962.6385.499849984.56277.040989998.59374.7881610002.1175.29703
10010.7777.9382110022.9380.8503110037.2982.5041510047.2481.9159710054.8882.97664
 10059.484.4039710071.5589.90845 10083.397.0191910091.6898.5190110110.9399.94865
10162.55100.892910173.18101.648810194.44105.000310205.78108.739610213.69112.0153
#Mann= 3 , 0 , 0
9845.324    0.04       09845.324    0.04       010213.69    0.04       0
#XS Ineff= 2 , 0
       0                               0
Bank Sta=9845.324,10213.69
Exp/Cntr=0.3,0.1

Type RM Length L Ch R = 1 ,10634.62,47.496700,47.496700,47.496700
XS GIS Cut Line= 6
800689.130589665843817.477654656800716.298883621843748.629494683
800781.563231423843608.479506802800795.583705341843570.688459438
800807.069986134843530.195411145800815.675106125843484.274514925
#Sta/Elev= 30
9859.237131.29249872.651128.96439875.227128.28549883.401124.85199894.151117.6631
9904.902112.31469915.652105.07079926.40399.710439937.256 98.79679948.28895.00538
 9959.3289.277549977.52681.020349981.38579.349029992.41875.27731    999974.55231
 10003.574.36784 10048.582.4119310058.62 86.051810072.2693.7475710080.6798.04574
10087.8699.2875110091.5799.8063210097.74100.062610123.56 100.57710144.47100.5416
10185.71101.555510195.89103.035710206.06103.480710216.24105.200210216.97105.5323
#Mann= 3 , 0 , 0
9859.237    0.04       09859.237    0.04       010216.97    0.04       0
#XS Ineff= 2 , 0
       0                               0
Bank Sta=9859.237,10216.97
Exp/Cntr=0.3,0.1

Type RM Length L Ch R = 1 ,10587.12,142.490200,142.490200,142.490200
XS GIS Cut Line= 6
800753.396292601843837.942152241 800786.55251339843717.006951243
800792.726138717843685.519160305800808.755576017 843625.85773023
800815.447106538843589.828305292800826.510580071843491.302930457
#Sta/Elev= 30
9860.674129.3334 9863.71129.20939874.027126.62899884.344121.1877 9894.66116.6348
9904.977109.93559907.853108.63299915.294105.73639925.682104.78729936.099 101.954
9946.51596.693539956.93291.022089967.34985.030049977.76679.288029988.139 74.6423
9998.34172.0648710008.5273.0873710029.0778.1568910039.4382.5699810060.1490.35589
10070.4994.8273110080.8398.44481   1009199.2395110111.3499.9290410131.52100.1223
10161.71100.852810181.84101.1721 10191.9101.693810201.96102.698210215.75 103.813
#Mann= 3 , 0 , 0
9860.674    0.04       09860.674    0.04       010215.75    0.04       0
#XS Ineff= 2 , 0
       0                               0
Bank Sta=9860.674,10215.75
Exp/Cntr=0.3,0.1

Type RM Length L Ch R = 1 ,10444.63,123.874400,123.874400,123.874400
XS GIS Cut Line= 5
801014.707640946843857.725137383800960.454168737843764.409165159
800932.242363155843707.985554039800848.692015976843613.584512383
800834.586113155 843563.67131792
#Sta/Elev= 30
9807.762111.59099822.481 111.3999834.049108.97569845.616106.31329857.183 103.229
 9868.75 100.6659886.76397.900369927.89992.935359937.40390.846319948.58487.20886
9959.76484.624849970.94481.847499978.78779.503369989.71475.910929996.12874.59029
 10004.874.2953710019.89 74.714610034.9875.3574210036.1975.4845610050.0778.70478
 10062.986.0966610065.1687.7901110076.25 93.703610080.2495.2388810089.6197.58035
10095.3398.2650410113.7799.5006110118.4399.6082210134.5599.6689510156.72100.4369
#Mann= 3 , 0 , 0
9807.762  0.0489       09807.762  0.0489       010156.72  0.0489       0
#XS Ineff= 2 , 0
       0                               0
Bank Sta=9807.762,10156.72
Exp/Cntr=0.3,0.1

Type RM Length L Ch R = 1 ,10320.75,123.874400,123.874400,123.874400
XS GIS Cut Line= 6
801126.056860253 843851.75598804801111.609943327843810.451871089
801077.916874123843733.824502362801003.911765166843594.457656515
800930.941971535843473.124834012800905.779908841843418.749510704
#Sta/Elev= 30
 9743.41108.62059750.493108.33889761.111106.89119771.728101.88219804.05395.70917
9825.90192.895989847.74990.763069858.67388.538819877.116 85.60229880.86685.28533
 9892.1885.232259903.49585.554239919.866 84.91989926.12483.968339948.75376.51077
9960.06874.594329982.69772.3001310005.3471.7959210028.0672.1939110063.0574.04389
10084.7874.7620910104.1877.4258210123.5882.1271910156.4192.8701710168.0897.23025
10183.56101.931710190.52103.4599 10201.7105.023210212.65107.254610230.22109.7566
#Mann= 3 , 0 , 0
 9743.41  0.0409       0 9743.41  0.0409       010230.22  0.0409       0
#XS Ineff= 2 , 0
       0                               0
Bank Sta=9743.41,10230.22
Exp/Cntr=0.3,0.1

Type RM Length L Ch R = 1 ,10196.88,123.874400,123.874400,123.874400
XS GIS Cut Line= 6
801269.618565948843815.383665296801216.756954281843696.506549488
801153.963604841843597.193491994801095.916261409843521.375387662
800985.816430748843399.456632602 800942.20817786843334.686688411
#Sta/Elev= 30
9698.191106.70099709.219106.4161 9719.84104.6445 9763.1394.181839774.03392.33815
9796.45290.886479900.59985.87437 9912.6184.595189926.08283.638999936.63281.90036
9961.128 76.06619985.92872.057339994.98970.83643   1000170.6600510023.9971.10865
10042.87 73.219810057.6375.4145610077.3976.3989810131.78 77.658910145.3779.10533
10154.88 83.198810161.1686.5089710172.0790.2455110198.4992.7633410207.19  94.328
10224.0199.0005410240.84102.213910248.66103.221810260.32104.334810283.99103.9278
#Mann= 3 , 0 , 0
9698.191  0.0435       09698.191  0.0435       010283.99  0.0435       0
#XS Ineff= 2 , 0
       0                               0
Bank Sta=9698.191,10283.99
Exp/Cntr=0.3,0.1

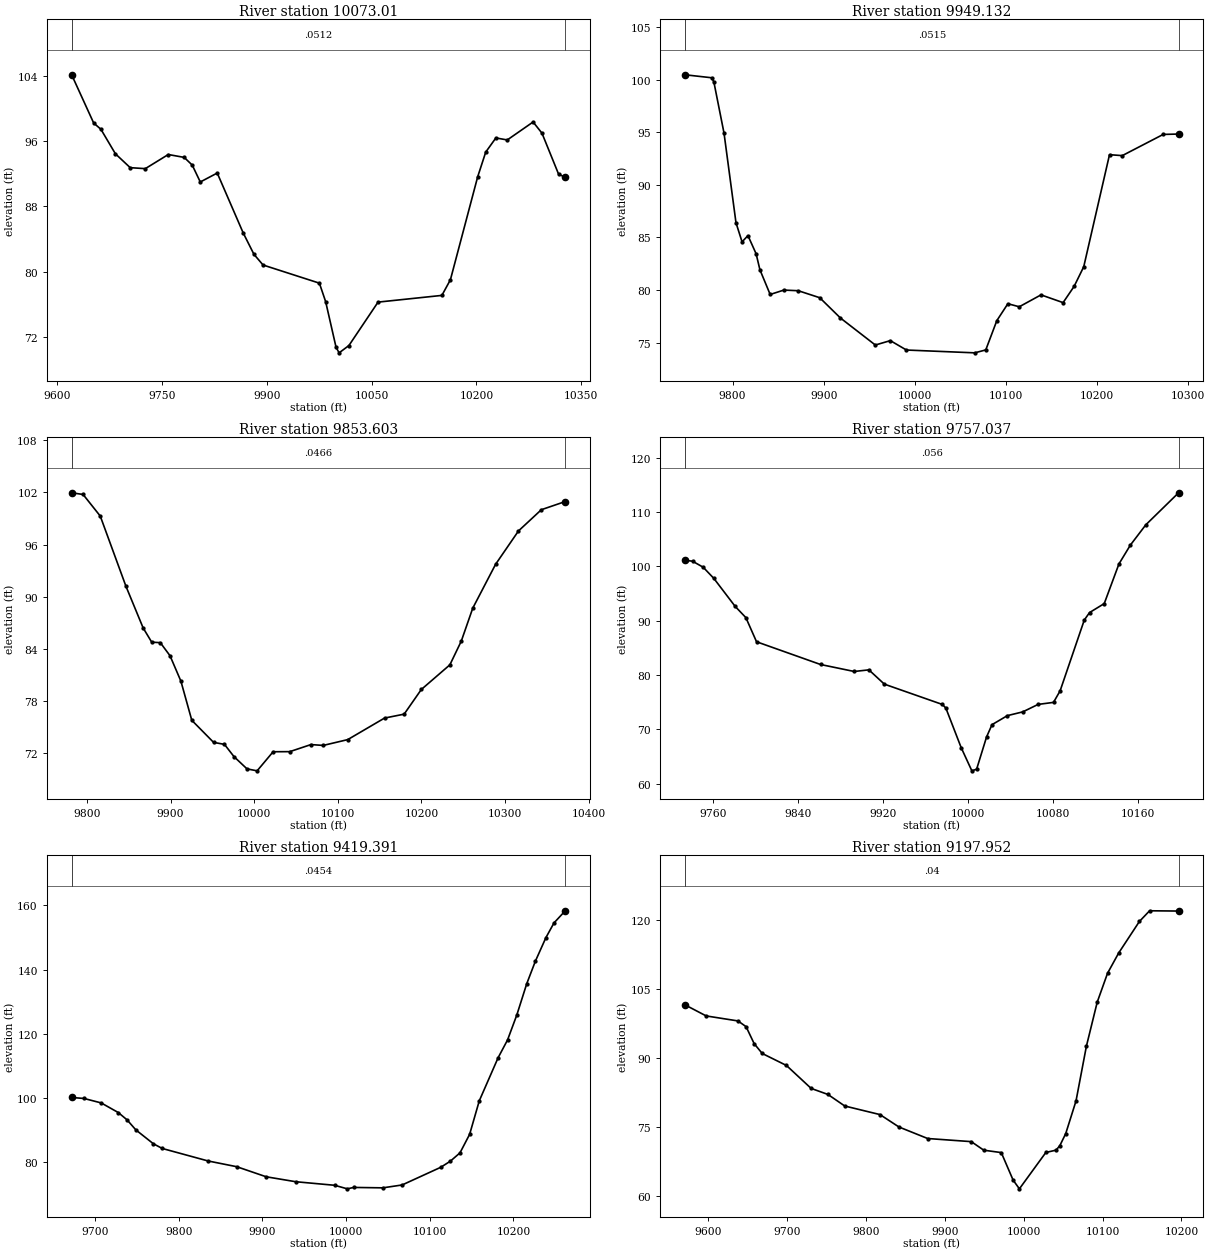
Type RM Length L Ch R = 1 ,10073.01,123.874400,123.874400,123.874400
XS GIS Cut Line= 6
801419.038787818843785.410886001801371.489924936843649.513648759
801306.836666442843555.970003893801210.963249828843468.379210262
801053.687853093 843380.78064065800965.125147677843276.873423649
#Sta/Elev= 30
9620.534104.11349652.04398.208529662.41697.439669683.16394.439069704.335 92.7432
9725.92692.621179758.84994.351739781.59994.000349793.12693.056219804.65290.98938
9828.91792.083989866.06284.754099881.44982.135869894.51980.824799975.12678.60418
9984.08976.34442    999970.7523410003.3970.0734210017.4270.97053 10059.176.28364
10150.4777.1042310162.6779.0181210201.7291.6252410213.2294.6452410227.7596.38125
10244.0896.1362710281.0598.3341610293.7296.9669310317.4491.9665510327.07 91.5456
#Mann= 3 , 0 , 0
9620.534  0.0512       09620.534  0.0512       010327.07  0.0512       0
#XS Ineff= 2 , 0
       0                               0
Bank Sta=9620.534,10327.07
Exp/Cntr=0.3,0.1

Type RM Length L Ch R = 1 ,9949.132,95.528600,95.528600,95.528600
XS GIS Cut Line= 5
801403.295888046843539.347224337801389.866431892843519.140872449
801289.230210364843400.910901263801075.471529841843254.426526278
801003.147189854843180.954180886
#Sta/Elev= 30
 9747.73100.4593 9777.43100.1719  9779.599.740629790.56294.914589803.69486.39483
9810.356 84.57519816.82685.172459825.78483.443879829.95881.923699841.21179.57488
9856.22279.993279872.067 79.93129895.61979.266069918.35177.336579956.626 74.7696
 9973.0975.18783 9990.7874.2938510065.7374.0265710077.85 74.304610089.9877.08813
 10102.178.6954310114.6178.4058710138.4779.5369910162.71 78.800110174.8480.34914
10185.3782.2110810213.6592.8624310227.6892.7747610272.5994.7897910289.4894.82552
#Mann= 3 , 0 , 0
 9747.73  0.0515       0 9747.73  0.0515       010289.48  0.0515       0
#XS Ineff= 2 , 0
       0                 10088.3       0
Bank Sta=9747.73,10289.48
Exp/Cntr=0.3,0.1

Type RM Length L Ch R = 1 ,9853.603,96.566400,96.566400,96.566400
XS GIS Cut Line= 4
801421.608682632843508.332776263801395.567015946843394.400484592
801284.889932632843302.169581831801044.115843508843077.601440989
#Sta/Elev= 30
9781.793101.9621 9795.47101.76729815.98699.28406 9846.7691.198079867.27586.41862
9877.53384.782429887.79184.730459899.40283.223819912.41980.301039925.43675.80253
 9951.4773.265089964.48873.03466 9975.8371.631519991.45170.2165810003.5469.99087
10022.6972.1858410042.59  72.19810067.9173.0106310082.5772.9131310111.8973.58107
10155.8776.0573610179.3376.5088510199.8679.3432410234.0382.18025 10247.784.91465
10261.37 88.693210288.7293.7453710316.0797.5768610343.42100.016110371.98100.9549
#Mann= 3 , 0 , 0
9781.793  0.0466       09781.793  0.0466       010371.98  0.0466       0
#XS Ineff= 2 , 0
       0                10120.95       0
Bank Sta=9781.793,10371.98
Exp/Cntr=0.3,0.1

Type RM Length L Ch R = 1 ,9757.037,337.645300,337.645300,337.645300
XS GIS Cut Line= 3
801445.480210364843492.056734607801458.501043737843339.061942935
801243.657293737843114.452567905
#Sta/Elev= 30
9733.616101.11119740.699100.93259750.73599.822699760.77197.764419780.84392.61028
9790.87990.555779800.91586.111049861.13281.929639892.78580.644129906.62380.94228
9921.16378.314299975.81474.570619979.03273.907189993.49966.6027210003.4962.36353
10007.9762.6672910017.3368.6028110022.4370.85697 10036.972.5204610051.3773.21181
10065.8374.58636 10080.374.9571210086.5277.0822410109.2490.1020110114.1991.48143
10128.0393.1344410141.87100.432910152.64103.9049 10167.1107.619910197.98113.5219
#Mann= 3 , 0 , 0
9733.616   0.056       09733.616   0.056       010197.98   0.056       0
#XS Ineff= 2 , 0
       0                               0
Bank Sta=9733.616,10197.98
Exp/Cntr=0.3,0.1

Type RM Length L Ch R = 1 ,9419.391,221.439000,221.439000,221.439000
XS GIS Cut Line= 6
801456.709253876843519.473359126801468.789727818843464.038396909
801482.990639906843418.915254562801505.423019349843367.597346768
801674.863407381843075.896752099801715.042985869842992.894151217
#Sta/Elev= 30
9672.216100.0803 9687.0399.765559707.49998.377819727.96895.366179738.42893.08743
9748.91189.962899769.87985.62604 9780.5384.16159 9835.2380.264039869.49178.47314
9904.632 75.33339939.91873.791789986.39372.6804510001.5471.5717210009.0572.00997
10043.9271.8820810066.9772.7775610113.0778.28411 10124.680.1987410136.1282.79466
10147.6588.5829110159.1899.0442910181.77112.535210192.93118.019410203.99 125.799
10215.88 135.58110226.21142.619910238.83149.981810248.43154.540410261.88158.3282
#Mann= 3 , 0 , 0
9672.216  0.0454       09672.216  0.0454       010261.88  0.0454       0
#XS Ineff= 2 , 0
       0                               0
Bank Sta=9672.216,10261.88
Exp/Cntr=0.3,0.1

Type RM Length L Ch R = 1 ,9197.952,221.439100,221.439100,221.439100
XS GIS Cut Line= 6
801577.207043415843691.639747931801606.560468076843538.875401578
801656.676916054843431.649090893801709.468062167  843369.0320347
801839.315083633843280.000644857801910.356679903843194.801732488
#Sta/Elev= 30
9570.648101.61629597.52499.208429637.88698.119719648.11596.869349658.343 93.1843
9668.57291.05359 9699.2688.45054 9730.5783.467189751.88582.15209  9773.279.64238
 9817.8977.778729841.89975.085679878.27972.583719933.61471.903869949.44170.04545
9971.64269.525729986.63363.554549994.58961.6513510028.15 69.550810041.0370.05585
10045.83 71.016210053.3473.64899 10066.480.7557610079.5592.6322410093.29102.2151
10106.36108.479110120.44112.869910146.73119.726910159.68122.048910196.44121.9899
#Mann= 3 , 0 , 0
9570.648    0.04       09570.648    0.04       010196.44    0.04       0
#XS Ineff= 2 , 0
       0                               0
Bank Sta=9570.648,10196.44
Exp/Cntr=0.3,0.1

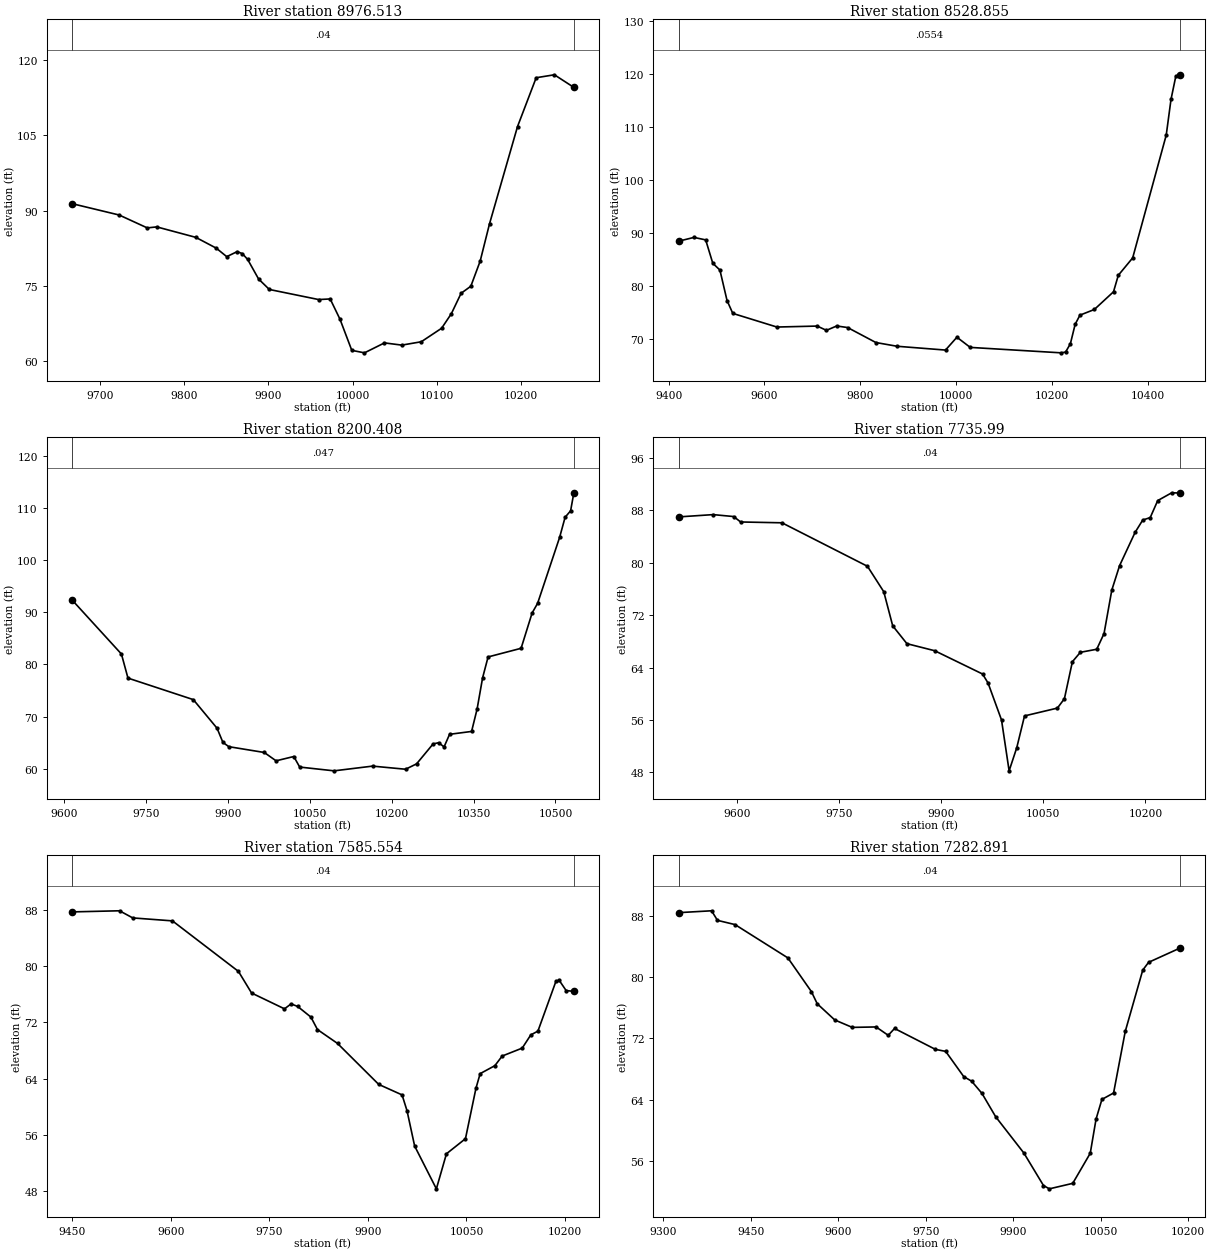
Type RM Length L Ch R = 1 ,8976.513,447.658200,447.658200,447.658200
XS GIS Cut Line= 6
801727.647148125843766.414711247801797.556273229843627.341732621
801836.448074561843574.538415911801941.787009364843468.576388502
801983.500582742843414.680030291802050.898178861843273.474419405
#Sta/Elev= 30
9666.77591.394019722.68289.135379756.05986.567549767.39986.76469 9813.7384.68297
9838.05882.528779850.47880.839359862.89881.844779869.00681.441599875.31780.28578
 9888.31 76.38799901.072 74.30369959.58372.297019973.32972.414419984.957 68.3878
    999962.1790710014.0761.6835810037.8363.6644210058.3963.2209910081.5363.88941
10105.6866.5810510117.2669.4814910128.83 73.543610140.3974.9485910151.49 79.9603
10162.5787.3793510195.82106.738910217.99116.473310239.61117.061110262.75114.5518
#Mann= 3 , 0 , 0
9666.775    0.04       09666.775    0.04       010262.75    0.04       0
#XS Ineff= 2 , 0
       0                               0
Bank Sta=9666.775,10262.75
Exp/Cntr=0.3,0.1

Type RM Length L Ch R = 1 ,8528.855,328.447300,328.447300,328.447300
XS GIS Cut Line= 6
801926.894412488843998.796811655802081.586364061843828.635664925
802250.341220349843645.817903996802334.152085394843543.054998472
802499.082640976843454.079304039 802506.67812708843205.598401278
#Sta/Elev= 30
9420.72888.441079452.88989.160819477.37688.693249492.24284.268949507.10882.98714
9521.97577.226169533.97674.790629626.03772.213129710.07972.395929729.44371.58764
9750.90672.415479773.67372.115439832.64569.283349876.87568.576229977.97367.85729
 10001.870.2870510029.5968.36206 10219.567.3335210228.58 67.480410238.5969.03837
10248.5972.73326 10258.674.4608310288.6175.5307610328.6378.8780110338.6381.99561
10368.6585.2861410438.68 108.50210448.69115.276710458.69119.6422 10468.1119.9151
#Mann= 3 , 0 , 0
9420.728  0.0554       09420.728  0.0554       0 10468.1  0.0554       0
#XS Ineff= 2 , 0
       09867.099        10078.84       0
Bank Sta=9420.728,10468.1
Exp/Cntr=0.3,0.1

Type RM Length L Ch R = 1 ,8200.408,464.418100,464.418100,464.418100
XS GIS Cut Line= 4
802449.169446498844079.079304039802547.910765976843850.129651278
802626.035765976843661.327567935802566.356946528843199.087984592
#Sta/Elev= 30
 9614.1192.376679704.586 82.00289716.56577.38362 9836.3673.254329879.81867.77119
 9890.6465.040739901.46364.224139966.39763.113029988.04161.5112110020.5162.33812
10031.3360.3139810094.3259.58903 10164.960.49579 10225.459.8955110245.5660.92879
10275.8164.7478910285.89 64.989510295.9864.1853710306.0666.5995810346.3967.14889
10356.4871.4370310366.5677.4253210376.6481.4459610437.1483.1017310457.3189.87312
10467.3991.7278910507.72104.3749 10517.8108.245910527.89109.488210533.85112.9454
#Mann= 3 , 0 , 0
 9614.11   0.047       0 9614.11   0.047       010533.85   0.047       0
#XS Ineff= 2 , 0
       0                               0
Bank Sta=9614.11,10533.85
Exp/Cntr=0.3,0.1

Type RM Length L Ch R = 1 , 7735.99,150.435900,150.435900,150.435900
XS GIS Cut Line= 6
802934.915137969843895.646477391802911.362264735843719.459817698
802884.933372325843630.939513434802865.496743547843601.440143982
802768.768281049843499.615394229 802629.73835461843244.821387753
#Sta/Elev= 30
9514.10487.01297 9565.0287.363659595.18887.066369605.31386.240329666.06386.11333
9791.67979.47531 9815.6375.589639828.76870.382929849.64767.658659890.45166.58249
9960.77463.026839968.81761.660859988.62656.012819999.80248.2437410011.0251.77434
10022.4356.6294210070.7357.8245210081.0359.2541310092.7564.9026810104.4866.34072
10128.52 66.805810139.2569.2008810150.6675.8395410162.0879.57128 10184.984.65596
10196.1286.5331710207.1286.9139510218.1289.5049910238.7190.6970510251.3390.65695
#Mann= 3 , 0 , 0
9514.104    0.04       09514.104    0.04       010251.33    0.04       0
#XS Ineff= 2 , 0
       0                               0
Bank Sta=9514.104,10251.33
Exp/Cntr=0.3,0.1

Type RM Length L Ch R = 1 ,7585.554,302.662600,302.662600,302.662600
XS GIS Cut Line= 6
802949.154545263 843896.94609342802923.505050815843651.501804421
802929.002311707843505.992976925   802915.195486 843470.44131294
802862.965237115843391.383357078802766.494048506843173.808541013
#Sta/Elev= 30
9449.42587.694779521.67587.854229541.82286.84021 9602.2686.420819702.74279.24803
9722.74676.178019772.88473.930149782.93874.632869792.993 74.26579813.08472.76085
9823.08570.986869853.62469.017579916.36763.199919951.918 61.70859959.456 59.4618
9971.05954.4492410004.1648.3700710019.4853.3467210048.4555.4907510064.4762.67032
10070.8264.7297710093.1965.8580710104.3867.2287510134.8668.3537510147.93   70.23
10158.7870.7662610186.3477.8738410191.2177.9770310201.7376.52531 10213.576.41102
#Mann= 3 , 0 , 0
9449.425    0.04       09449.425    0.04       0 10213.5    0.04       0
#XS Ineff= 2 , 0
       0                               0
Bank Sta=9449.425,10213.5
Exp/Cntr=0.3,0.1

Type RM Length L Ch R = 1 ,7282.891,548.930300,548.930300,548.930300
XS GIS Cut Line= 6
802973.061483232843881.476898263802947.990972046843645.182269543
802953.948732154843556.268436637803000.407471808843457.632837062
 803136.71984368843341.643672566803142.475188411 843100.71037186
#Sta/Elev= 30
9326.04488.373279382.732 88.61829392.78187.369829422.97286.816059513.546 82.4719
9553.80178.082069563.86376.491919593.87574.381059623.94773.409899664.77573.46837
9685.58472.376459696.45773.268469766.63770.537519784.10770.281829815.04466.99305
9828.65166.391769846.358 64.79749869.88361.749239918.22357.020119951.81852.78692
9961.87752.3539910001.9753.0704810031.9956.9926110041.9961.46412   1005264.01755
   1007264.8532310092.0172.8819710122.0180.8801210132.0381.8955710186.4483.77362
#Mann= 3 , 0 , 0
9326.044    0.04       09326.044    0.04       010186.44    0.04       0
#XS Ineff= 2 , 0
       0                               0
Bank Sta=9326.044,10186.44
Exp/Cntr=0.3,0.1

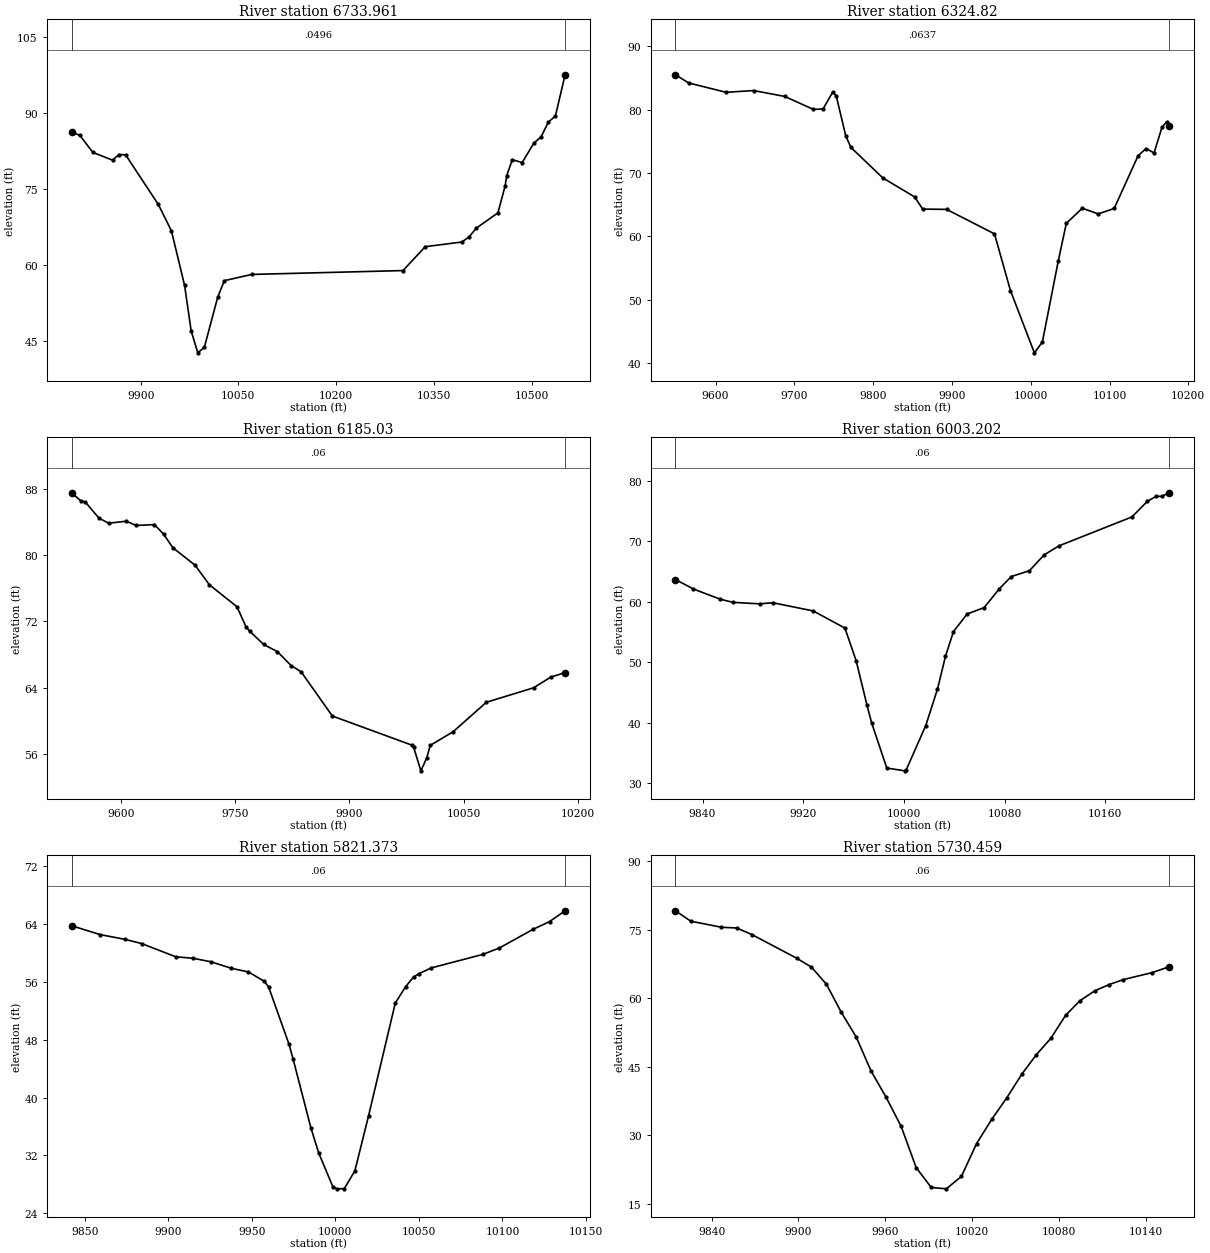
Type RM Length L Ch R = 1 ,6733.961,409.140900,409.140900,409.140900
XS GIS Cut Line= 6
803192.186686121843827.444778188803208.219019585843662.579125303
803227.083109565843563.955069508803287.895019136843488.302417037
803371.753533792843351.081929886803472.865302404843141.594767245
#Sta/Elev= 30
9794.154 86.20639806.64785.599989826.72482.227419856.84180.70433 9866.8881.80896
9876.91881.756319927.19271.972159947.31166.760389967.47156.033689977.58447.06038
9987.69842.754989997.81143.84817 10018.253.6788110028.4656.9734610070.5658.19663
 10302.658.9576410336.7463.6595510392.7864.5757510403.9865.5828210415.1967.31989
10448.2970.3254610459.3375.6362610461.7577.6546310470.3680.7899410485.4180.22615
10503.4684.0678910514.49 85.287310525.5388.1477310536.5689.4329510551.3597.51688
#Mann= 3 , 0 , 0
9794.154  0.0496       09794.154  0.0496       010551.35  0.0496       0
#XS Ineff= 2 , 0
       0                               0
Bank Sta=9794.154,10551.35
Exp/Cntr=0.3,0.1

Type RM Length L Ch R = 1 , 6324.82,139.789400,139.789400,139.789400
XS GIS Cut Line= 4
  803378.1861763843828.635664925803501.939737529843651.443065867
 803566.62909919843249.243991807803563.752329499843249.390578777
#Sta/Elev= 30
9549.02485.504599565.65684.219679613.31782.739479648.24783.01637 9687.6382.09347
9724.22380.03924 9736.4280.121669748.61882.762389753.034 82.21459765.154  75.899
 9771.6874.051579812.19469.239319852.70866.232379862.83664.321769893.22264.27343
9953.99360.41276 9974.25 51.478510004.6441.6460610014.7643.3389910035.0256.17351
10045.1562.0612810065.41 64.460910085.6663.5585510105.9264.4145410136.3172.74064
10146.4373.8690210156.56 73.172910166.6977.2568810172.5278.07456 10175.4 77.3925
#Mann= 3 , 0 , 0
9549.024  0.0637       09549.024  0.0637       0 10175.4  0.0637       0
#XS Ineff= 2 , 0
       09926.456                       0
Bank Sta=9549.024,10175.4
Exp/Cntr=0.3,0.1

Type RM Length L Ch R = 1 , 6185.03,181.828600,181.828600,181.828600
XS GIS Cut Line= 4
 803405.11562708843865.320623472803636.235418737843519.183470696
803726.296182603843392.230345696803767.636097195843329.148698246
#Sta/Elev= 30
9535.68287.501579548.09286.487979553.48286.398779571.491 84.44219584.16583.83288
9607.50784.070279620.23883.556299644.28783.662069656.311 82.51079668.33580.88116
9697.54878.762629716.43276.394739752.50573.75573 9764.5371.301959769.58170.76743
9787.58969.196349805.59868.332029823.60666.655469836.67565.90351 9877.63  60.568
9981.53957.066619984.31956.79409  9993.853.95247 10001.655.5497710006.0657.02357
10036.1758.6744110079.6262.2224810141.6763.9730710164.01  65.25410182.9665.80274
#Mann= 3 , 0 , 0
9535.682    0.06       09535.682    0.06       010182.96    0.06       0
#XS Ineff= 2 , 0
       09943.985        10047.95       0
Bank Sta=9535.682,10182.96
Exp/Cntr=0.3,0.1

Type RM Length L Ch R = 1 ,6003.202,181.828600,181.828600,181.828600
XS GIS Cut Line= 6
803632.062853479843682.751231889803720.609429772843652.363190572
803755.030268496 843636.81467524803821.797357588843583.428095646
803862.599534308843555.070694901803969.615476393843489.696409929
#Sta/Elev= 30
9818.48163.693279832.77262.125019853.78660.452619864.29359.910259885.30859.66697
9895.81559.849589928.00658.486779953.16755.644969962.12350.208359970.698 42.8634
9974.33639.989769986.42632.4539510000.7531.9912110001.7332.0876210017.4139.50046
10026.7245.5322310033.0950.9859510039.4555.0816910050.3257.9914210063.8159.04055
10075.9862.1889110085.3764.1866210099.7765.1541410111.4967.7756110123.2169.26718
10181.2974.0693210193.5276.6599910200.4777.4730510205.2377.4890110210.6478.06976
#Mann= 3 , 0 , 0
9818.481    0.06       09818.481    0.06       010210.64    0.06       0
#XS Ineff= 2 , 0
       0                               0
Bank Sta=9818.481,10210.64
Exp/Cntr=0.3,0.1

Type RM Length L Ch R = 1 ,5821.373,90.914300,90.914300,90.914300
XS GIS Cut Line= 6
803633.378399843843711.364365244 803694.10341051843712.493548885
803736.750412062843730.637299664803791.327626581843774.220583667
803817.891774709843788.241573585803904.268652518843799.539272457
#Sta/Elev= 30
9842.21263.795889859.18662.571979874.08661.913349884.098 61.32959904.44859.50071
 9915.0159.287199925.571 58.8051 9937.7857.905859948.00957.398319957.55256.09688
9960.07855.322629972.315 47.37699974.77345.311689985.43935.782919990.015 32.3745
 9998.6927.57771   1000127.3813210005.3627.4060210011.7129.87364 10019.937.49856
10035.8953.0941210042.0355.3500110046.8456.6967310050.0157.1567210057.3957.95404
10088.0959.8161810098.1960.7157710118.2263.2842510128.2464.3723910137.5165.86481
#Mann= 3 , 0 , 0
9842.212    0.06       09842.212    0.06       010137.51    0.06       0
#XS Ineff= 2 , 0
       0                               0
Bank Sta=9842.212,10137.51
Exp/Cntr=0.3,0.1

Type RM Length L Ch R = 1 ,5730.459,90.914400,90.914400,90.914400
XS GIS Cut Line= 6
803574.997052624843894.205032337 803617.60603557843879.213002754
803713.254964056843855.076283825803805.210268829843827.721190239
803832.824010274843824.195766541 803906.36030584843820.717262362
#Sta/Elev= 30
9814.95379.166719825.558 76.88499846.75975.55754 9857.3675.388319867.74973.96381
9898.68968.794539909.00366.820129919.31663.08333 9929.6356.913629939.94351.50798
9950.25744.026079960.58838.326239971.00331.937679981.41922.882739991.83518.54543
10002.2518.23971 10012.7 20.966410023.1528.14296 10033.633.4337710044.0438.17572
10054.7143.4788810064.5847.6541910074.6651.2784610084.7356.2576910094.7459.48429
10104.7561.5970710114.7662.9932810124.7764.0997410144.7965.6360710156.1766.89085
#Mann= 3 , 0 , 0
9814.953    0.06       09814.953    0.06       010156.17    0.06       0
#XS Ineff= 2 , 0
       0                               0
Bank Sta=9814.953,10156.17
Exp/Cntr=0.3,0.1