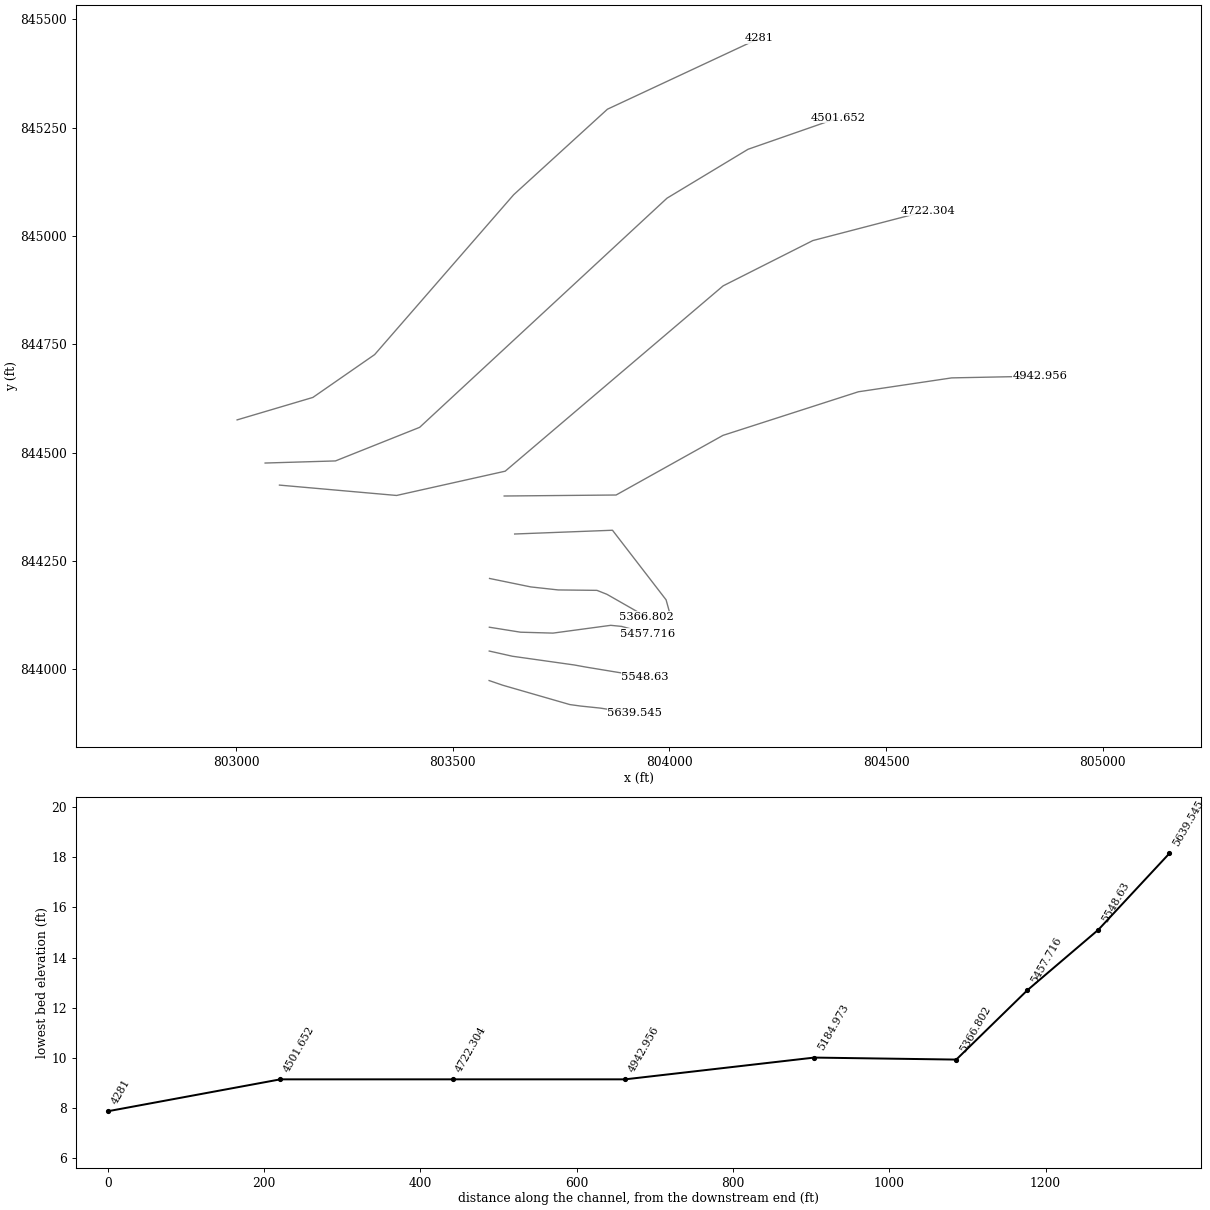
HEC-RAS study 18254_ras.prj: 18254

--- 18254_ras.g01 (geometry) --- (continued)

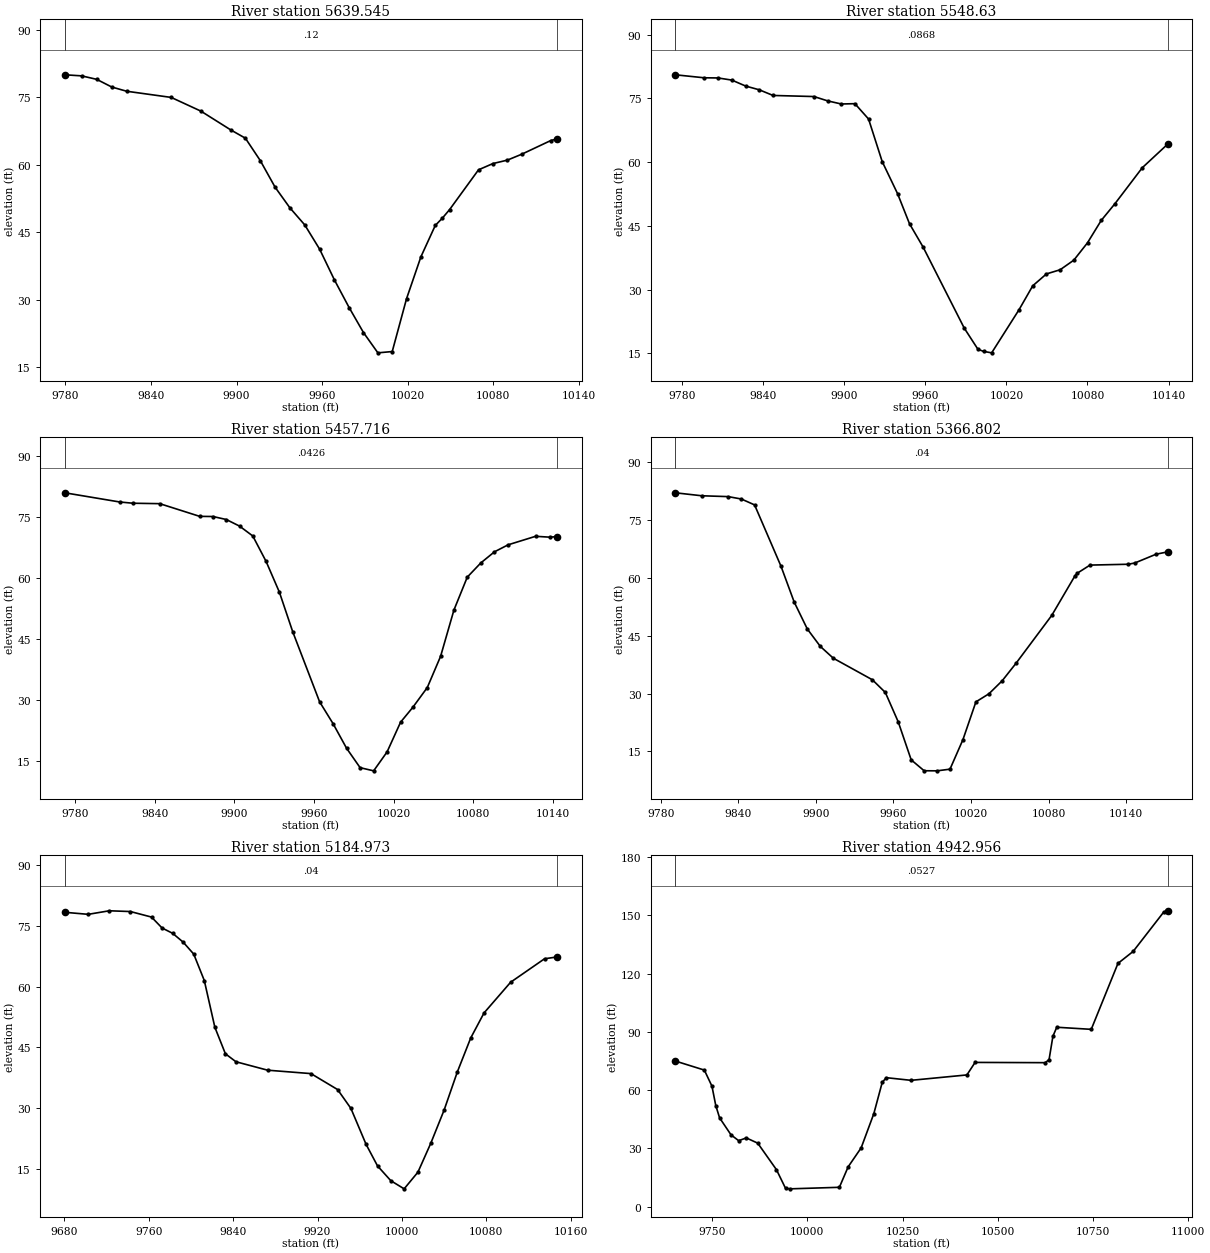
Type RM Length L Ch R = 1 ,5639.545,90.914300,90.914300,90.914300
XS GIS Cut Line= 6
803583.790605505843974.245347096803615.325787322843963.428155414
803770.059844614843918.826008696803794.960460763843915.391281632
803839.939431308843910.721954662803919.460325372843898.507622598
#Sta/Elev= 30
9779.49180.051159791.341 79.80939801.91379.035049812.48577.323439822.89876.38696
9854.11975.012929874.93371.964189895.748  67.8059906.15565.930749916.56260.96231
9926.96955.030319937.376 50.42079947.783 46.62539958.19141.235029968.59834.36712
9978.85128.247549988.94522.66162 9999.0418.1551310009.0918.4419610019.1430.21938
 10029.239.5340210039.2646.5119210044.22 48.131610049.3450.0542410069.5858.89356
10079.6960.2886410089.8161.0533710099.9362.3745210120.1665.3993210124.6865.78156
#Mann= 3 , 0 , 0
9779.491    0.12       09779.491    0.12       010124.68    0.12       0
#XS Ineff= 2 , 0
       0                               0
Bank Sta=9779.491,10124.68
Exp/Cntr=0.3,0.1

Type RM Length L Ch R = 1 , 5548.63,90.914300,90.914300,90.914300
XS GIS Cut Line= 6
803584.101433665844042.316715425803637.593462705844030.323552653
803780.284173495844010.195343699 803807.00906474844005.337062949
803931.001437257843984.922202671803943.376287973843982.427894848
#Sta/Elev= 30
9774.91480.537769796.33179.830599806.57979.792019816.82879.286759827.076 77.8808
9837.21376.992869847.31275.67324 9877.6175.415139887.70974.398599897.80873.66466
9907.90773.738289918.00670.128359928.10560.104539939.43952.586879948.30345.48649
9958.40239.978199988.79220.941989998.95415.9475610003.0715.45856 10009.115.11358
10029.3725.26347 10039.530.8872110049.6433.6829210059.7734.6606710069.9136.92058
10080.0441.0132410090.1846.2672310100.3150.1951510120.5858.6711510139.2964.19756
#Mann= 3 , 0 , 0
9774.914  0.0868       09774.914  0.0868       010139.29  0.0868       0
#XS Ineff= 2 , 0
       0                               0
Bank Sta=9774.914,10139.29
Exp/Cntr=0.3,0.1

Type RM Length L Ch R = 1 ,5457.716,90.914300,90.914300,90.914300
XS GIS Cut Line= 6
 803584.35248845844097.297714281803656.305535131844085.807379475
803731.139560333844083.703098188803864.497297269844101.673074741
803889.391568095844099.197683135803950.400235954844082.614091205
#Sta/Elev= 30
9772.25880.935329813.61478.679629823.69178.369199843.84678.264629873.91275.14907
9883.93175.109019893.93174.378159903.93272.760049913.93270.332919923.94464.09426
9933.97656.538819944.007 46.83619964.26629.638429974.43624.260939984.60718.22761
9994.77813.4778110004.97 12.702410015.11 17.358910025.2624.6406410034.4528.27394
10045.3933.14801 10055.4  40.80110065.4552.16341 10075.560.2371910085.6963.71661
10095.9966.4500810106.2968.1690710126.95 70.253610137.4870.0460510143.1770.16765
#Mann= 3 , 0 , 0
9772.258  0.0426       09772.258  0.0426       010143.17  0.0426       0
#XS Ineff= 2 , 0
       0                               0
Bank Sta=9772.258,10143.17
Exp/Cntr=0.3,0.1

Type RM Length L Ch R = 1 ,5366.802,181.828600,181.828600,181.828600
XS GIS Cut Line= 6
803584.866177053 844209.79552066803679.941654757844190.279261932
803743.217661064844183.332139466803832.579167013844182.347937774
 803855.54194482844173.279370114803947.440004428844120.841006498
#Sta/Elev= 30
9791.21682.07625 9811.7781.299899832.18781.080849842.39680.457219852.60478.93057
9873.02163.02895 9883.2353.728559893.36346.748199903.42342.228499913.48339.15794
9943.66333.570269953.71330.278719963.71422.623349973.71512.789629983.7179.964371
9993.7189.94038110003.7210.3744110013.7318.0335710023.7627.8319210033.84 29.9306
10044.07 33.299310054.8237.8592810082.4250.2686410100.3860.5408110102.0761.19559
   1011263.3172410141.6163.5348410146.6363.8599910163.0766.1372410171.9966.74101
#Mann= 3 , 0 , 0
9791.216    0.04       09791.216    0.04       010171.99    0.04       0
#XS Ineff= 2 , 0
       0                               0
Bank Sta=9791.216,10171.99
Exp/Cntr=0.3,0.1

Type RM Length L Ch R = 1 ,5184.973,242.017100,242.017100,242.017100
XS GIS Cut Line= 4
803642.745835394844312.369234607803868.440279812844321.049790159
803992.138196498844160.459512368804002.387753291844123.513435564
#Sta/Elev= 30
9680.27478.375879702.54477.871749722.559 78.74939742.57478.560149762.58977.19214
9772.59674.489589782.60473.179479792.61170.992799802.61868.039959812.62661.51198
9822.633 49.9644 9832.6443.403169842.64841.42946 9872.6739.346629913.77138.50243
9939.01734.561249951.63929.906619966.04721.011749976.88515.685869989.50712.02885
10002.1310.0201510015.2114.1452610027.38 21.2742   1004029.4638310052.6238.95118
10065.2447.2949110077.8753.4912910103.11 61.086310135.2666.8866810147.1867.33809
#Mann= 3 , 0 , 0
9680.274    0.04       09680.274    0.04       010147.18    0.04       0
#XS Ineff= 2 , 0
       0                               0
Bank Sta=9680.274,10147.18
Exp/Cntr=0.3,0.1

Type RM Length L Ch R = 1 ,4942.956,220.652000,220.652000,220.652000
XS GIS Cut Line= 6
803618.576641347844400.048630755803876.791690069844402.344085665
804123.358450668844539.928681189804435.809306758844640.539954016
804651.136354034844672.588154054804855.254398223844676.658018741
#Sta/Elev= 30
9653.07774.989089729.57770.305299749.57762.011479759.59452.049419769.61545.71183
9799.67636.940449819.71733.951869839.75735.378669869.79932.670559918.81619.04497
9942.8629.3773599954.9119.15319710084.119.94512110107.2220.50325 10141.330.25645
10174.5647.8678410196.6964.0340610207.4866.3906810272.2465.0294610418.9367.80772
10440.3874.2555410624.5674.1224210634.6575.7035110644.7587.7273910654.84 92.3666
 10745.4  91.28710815.53125.239610855.54131.439210935.56151.660810945.82152.3403
#Mann= 3 , 0 , 0
9653.077  0.0527       09653.077  0.0527       010945.82  0.0527       0
#XS Ineff= 2 , 0
       0                               0
Bank Sta=9653.077,10945.82
Exp/Cntr=0.3,0.1

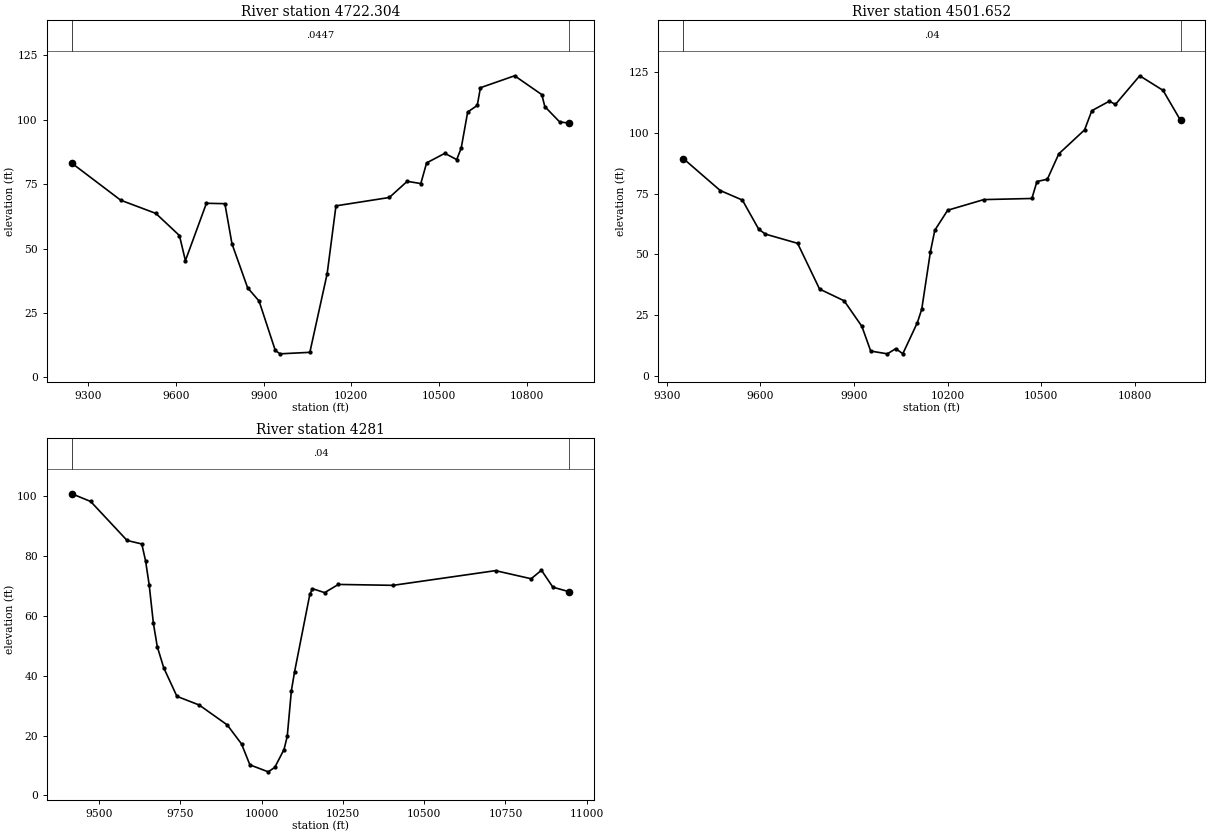
Type RM Length L Ch R = 1 ,4722.304,220.652000,220.652000,220.652000
XS GIS Cut Line= 6
803100.052829878 844425.21080823803370.252571275844401.300736435
 803620.90226472844457.313318188804123.773594959844884.932256975
804330.672495309844989.408675065 804596.90995778845058.693134029
#Sta/Elev= 30
9243.41583.119739410.74368.756269530.92663.643149611.80155.046049632.21945.30866
9704.15167.566039767.34867.413189791.66651.83184 9845.1534.792789884.41929.62546
9939.90610.483579956.2029.15319710058.269.741104 10117.540.2472610147.6566.57288
10330.3669.8109310391.5576.0823210438.1275.2147310457.9983.2361510520.3486.94831
10561.0284.5163210576.4288.9701610598.54102.959810631.38105.531810642.22112.4027
10759.29117.033310852.42 109.71710862.69105.073510913.5399.1250910945.8498.67706
#Mann= 3 , 0 , 0
9243.415  0.0447       09243.415  0.0447       010945.84  0.0447       0
#XS Ineff= 2 , 0
       0                               0
Bank Sta=9243.415,10945.84
Exp/Cntr=0.3,0.1

Type RM Length L Ch R = 1 ,4501.652,220.652000,220.652000,220.652000
XS GIS Cut Line= 6
803066.994706658844476.127917543803229.262634738844480.979525125
803423.514524015844558.489579088 803994.31569794845087.282277269
804181.262710956845200.085568657804389.407021263845272.579132412
#Sta/Elev= 30
9353.17889.426339471.40676.282199542.51272.340889594.57460.413279615.94758.37534
9719.35954.571649789.67135.775429868.31930.95795 9925.1220.463719953.46910.28744
10006.939.15268510033.54 11.271410056.359.200076   1010322.0075610116.9427.51216
 10144.851.1918810158.74  59.94110199.9568.1699210315.7172.5464410469.6573.00627
10485.9379.9819710519.2380.9037410555.9491.3596310638.44101.192110661.61109.0785
 10717.9112.999110737.17111.657710815.03123.432810889.68117.443710945.83105.0994
#Mann= 3 , 0 , 0
9353.178    0.04       09353.178    0.04       010945.83    0.04       0
#XS Ineff= 2 , 0
       0                               0
Bank Sta=9353.178,10945.83
Exp/Cntr=0.3,0.1

Type RM Length L Ch R = 1 ,    4281,0.000000,0.000000,0.000000
XS GIS Cut Line= 6
803002.360818116844575.678964235803177.209770942844627.515137697
803319.699181818844726.344329723803640.426402454845095.142003821
803856.799661598845292.521229594804206.984215835845456.045049444
#Sta/Elev= 30
 9416.49100.90329474.37698.327079586.43285.279839631.59684.117829643.34378.41777
9654.37770.390829667.29257.581319679.26749.737199699.139 42.68239739.63533.13817
9808.33630.227369894.31323.587229938.43317.203849964.06810.2128310020.627.882348
10040.719.39360210069.0315.3537310078.9319.7299410091.6735.0295210101.3141.25074
10148.3667.23477 10156.669.1581610193.9667.8302510236.2770.5779110404.3970.27363
10719.4775.18958 10829.172.4732210860.7875.3221610895.9569.6603910945.8468.13143
#Mann= 3 , 0 , 0
 9416.49    0.04       0 9416.49    0.04       010945.84    0.04       0
#XS Ineff= 2 , 0
       0                               0
Bank Sta=9416.49,10945.84
Exp/Cntr=0.3,0.1